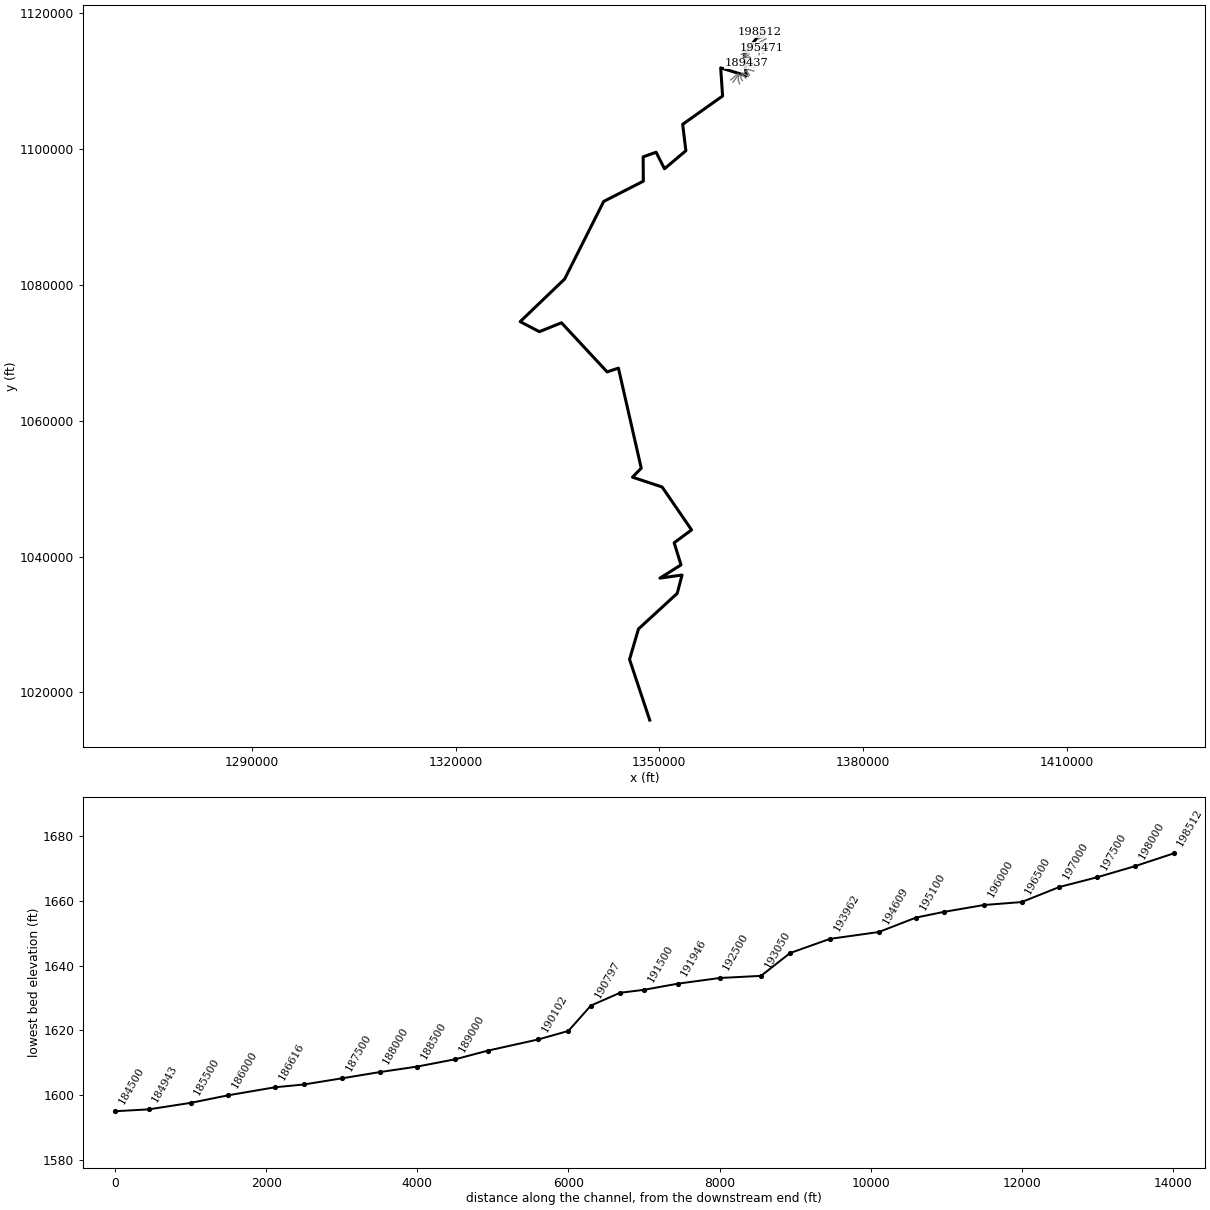
--- Chauga River.prj (project) ---

Proj Title=Chauga River Limited Detail Study
Current Plan=p01
Default Exp/Contr=0.3,0.1
English Units
Geom File=g01
Flow File=f01
Plan File=p01
Y Axis Title=Elevation
X Axis Title(PF)=Main Channel Distance
X Axis Title(XS)=Station
BEGIN DESCRIPTION:
Chauga River
END DESCRIPTION:
DSS Export Rating Curves= 0
DSS Export Rating Curve Sorted= 0
DSS Export Volume Flow Curves= 0
DXF OffsetX= 0
DXF OffsetY= 0
DXF ScaleX= 1
DXF ScaleY= 10

--- Chauga River.p01 (plan) ---

Plan Title=100-Year Single
Program Version=3.12
Short Identifier=100Year
Geom File=g01
Flow File=f01
Subcritical Flow
K Sum by GR= 0
Std Step Tol= 0.01
Critical Tol= 0.01
Num of Std Step Trials= 20
Max Error Tol= 0.3
Flow Tol Ratio= 0.001
Split Flow NTrial= 30
Split Flow Tol= 0.02
Split Flow Ratio= 0.02
Log Output Level= 0
Friction Slope Method= 1
Unsteady Friction Slope Method= 2
Unsteady Bridges Friction Slope Method= 1
Parabolic Critical Depth
Global Vel Dist= 0 , 0 , 0
Global Log Level= 0
CheckData=True
Encroach Param=-1 ,0,0, 0
BEGIN DESCRIPTION:
100Year Run
END DESCRIPTION:
Computation Interval=1HOUR
Output Interval=1HOUR
Run HTab= 0
Run UNet= 0
Run PostProcess= 0
UNET Theta= 1
UNET Theta Warmup= 1
UNET ZTol= 0.02
UNET ZSATol= 0.05
UNET MxIter= 20
UNET MaxInSteps= 0
UNET DtIC= 0
UNET DtMin= 0
UNET MaxCRTS= 20
UNET WFStab= 2
UNET SFStab= 1
UNET WFX= 1
UNET SFX= 1
UNET DSS MLevel= 4
UNET DZMax Abort= 100
UNET Convert EG Bridges=-1
UNET Use Existing IB Tables=-1
UNET Froude Reduction=False
UNET Froude Limit= 1
UNET Froude Power= 10
Instantaneous Interval=1HOUR
Write IC File= 0
Echo Input=False
Echo Output=False
Write Detailed= 0
Detailed Automatic Start=False, 10

--- Chauga River.f01 (steady flow) ---

Flow Title=100-year Single
Number of Profiles=1
Profile Names=100-year
River Rch & RM= Chauga River,Reach-1,198512
     843
River Rch & RM= Chauga River,Reach-1,195100
    1009
River Rch & RM= Chauga River,Reach-1,192500
    1521
River Rch & RM= Chauga River,Reach-1,187000
    1778
River Rch & RM= Chauga River,Reach-1,181909
    2199
River Rch & RM= Chauga River,Reach-1,177500
    2296
River Rch & RM= Chauga River,Reach-1,173803
    2329
River Rch & RM= Chauga River,Reach-1,171500
    2522
River Rch & RM= Chauga River,Reach-1,168500
    3147
River Rch & RM= Chauga River,Reach-1,166500
    4066
River Rch & RM= Chauga River,Reach-1,159840
    5117
River Rch & RM= Chauga River,Reach-1,157575
    5325
River Rch & RM= Chauga River,Reach-1,153125
    5481
River Rch & RM= Chauga River,Reach-1,149534
    5620
River Rch & RM= Chauga River,Reach-1,144956
    5689
River Rch & RM= Chauga River,Reach-1,141550
    5936
River Rch & RM= Chauga River,Reach-1,137458
    5983
River Rch & RM= Chauga River,Reach-1,136500
    6447
River Rch & RM= Chauga River,Reach-1,133000
    6481
River Rch & RM= Chauga River,Reach-1,132500
    6663
River Rch & RM= Chauga River,Reach-1,127709
    6845
River Rch & RM= Chauga River,Reach-1,124500
    6885
River Rch & RM= Chauga River,Reach-1,122927
    7166
River Rch & RM= Chauga River,Reach-1,121105
    7230
River Rch & RM= Chauga River,Reach-1,119391
    7283
River Rch & RM= Chauga River,Reach-1,116500
    7459
River Rch & RM= Chauga River,Reach-1,112000
    7594
River Rch & RM= Chauga River,Reach-1,109336
    7929
River Rch & RM= Chauga River,Reach-1,105949
    7991
River Rch & RM= Chauga River,Reach-1,105111
    8051
River Rch & RM= Chauga River,Reach-1,101411
    8093
River Rch & RM= Chauga River,Reach-1,100500
    8235
River Rch & RM= Chauga River,Reach-1,94830
    8896
River Rch & RM= Chauga River,Reach-1,93500
    9003
River Rch & RM= Chauga River,Reach-1,89500
    9031
River Rch & RM= Chauga River,Reach-1,87000
    9170
River Rch & RM= Chauga River,Reach-1,84371
    9360
River Rch & RM= Chauga River,Reach-1,80564
    9417
River Rch & RM= Chauga River,Reach-1,77500
    9470
River Rch & RM= Chauga River,Reach-1,74000
    9481
River Rch & RM= Chauga River,Reach-1,73500
    9718
River Rch & RM= Chauga River,Reach-1,70500
    9743
River Rch & RM= Chauga River,Reach-1,68500
    9800
River Rch & RM= Chauga River,Reach-1,66000
   10413
River Rch & RM= Chauga River,Reach-1,62146
   10469
River Rch & RM= Chauga River,Reach-1,59000
   10471
River Rch & RM= Chauga River,Reach-1,58000
   10585
River Rch & RM= Chauga River,Reach-1,56318
   10615
River Rch & RM= Chauga River,Reach-1,55942
   10664
River Rch & RM= Chauga River,Reach-1,54000
   10717
River Rch & RM= Chauga River,Reach-1,49000
   10724
River Rch & RM= Chauga River,Reach-1,47824
   11554
River Rch & RM= Chauga River,Reach-1,43460
   11572
River Rch & RM= Chauga River,Reach-1,42383
   11737
River Rch & RM= Chauga River,Reach-1,36340
   11772
River Rch & RM= Chauga River,Reach-1,32500
   12024
River Rch & RM= Chauga River,Reach-1,29467
   12113
River Rch & RM= Chauga River,Reach-1,26500
   12147
River Rch & RM= Chauga River,Reach-1,23947
   12343
River Rch & RM= Chauga River,Reach-1,20230
   12392
River Rch & RM= Chauga River,Reach-1,14500
   14607
River Rch & RM= Chauga River,Reach-1,11842
   14637
River Rch & RM= Chauga River,Reach-1,10000
   14674
River Rch & RM= Chauga River,Reach-1,8000
   14976
River Rch & RM= Chauga River,Reach-1,5356
   15120
Boundary for River Rch & Prof#=Chauga River,Reach-1,1
Up Type=0
Dn Type=3
Dn Slope=0.0002

--- Chauga River.g01 (geometry) ---

Geom Title=Existing Conditions

River Reach=Chauga River,Reach-1
Reach XY= 30
      1365132.68      1117309.29      1362512.74      1114064.30
      1362817.27      1110810.28      1359046.64      1111971.63
      1359327.00      1107826.86      1353449.52      1103657.33
      1353921.64      1099771.74      1350771.32      1097112.07
      1349536.18      1099547.99      1347629.77      1098862.76
      1347653.83      1095281.55      1341818.75      1092302.06
      1336068.15      1080874.16      1329518.86      1074599.88
      1332346.15      1073123.66      1335603.07      1074433.77
      1342326.78      1067197.52      1343986.49      1067758.74
      1347349.44      1053018.32      1346061.28      1051696.75
      1350424.94      1050249.47      1354759.37      1043931.01
      1352197.50      1042035.55      1353204.99      1038778.88
      1350099.82      1036830.74      1353355.56      1037288.13
      1352645.91      1034581.47      1346941.08      1029346.24
      1345626.15      1024863.00      1348598.82      1015924.48

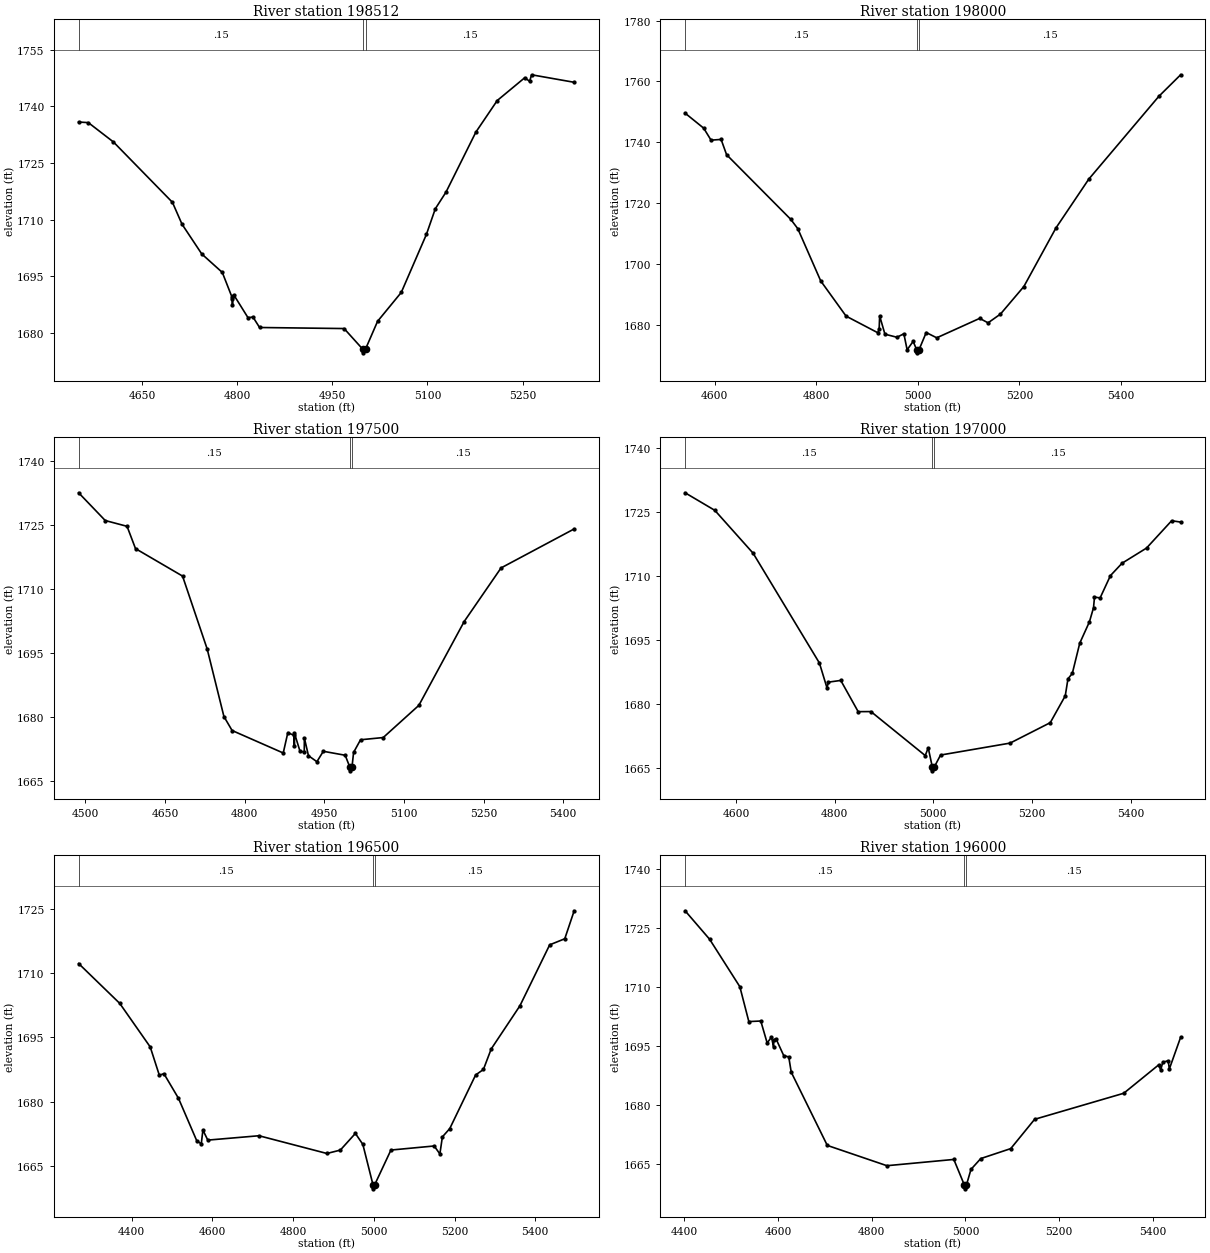
Type RM Length L Ch R = 1,198512,512,512,512
BEGIN DESCRIPTION:
Chauga River 397.0
END DESCRIPTION:
XS GIS Cut Line= 3
      1365583.45      1117289.87      1365133.06      1117292.88
      1364803.24      1117259.51
#Sta/Elev= 30
  4549.6 1735.83  4564.9 1735.67  4604.5 1730.55  4697.6 1714.57  4712.7 1708.78
  4743.9 1700.89  4776.3 1696.00  4791.3 1689.58  4792.1 1689.04  4792.3 1687.28
  4792.8 1689.80  4794.7 1689.98  4816.8 1684.03  4824.7 1684.19  4835.1 1681.42
  4968.5 1681.14  4997.7 1675.71  4998.2 1674.71  5002.3 1675.71  5021.3 1683.06
  5058.7 1690.71  5098.3 1706.05  5112.4 1712.86  5129.3 1717.28  5176.4 1733.16
  5210.1 1741.52  5253.6 1747.57  5261.2 1746.60  5264.3 1748.34  5331.5 1746.35
#Mann=3,-1,0
  4549.6    0.15       0  4997.7    0.05       0  5002.3    0.15       0
Bank Sta=4997.7,5002.3
XS Rating Curve= 0
Exp/Cntr=0.3,0.1

Type RM Length L Ch R = 1,198000,500,500,500
BEGIN DESCRIPTION:
Chauga River 396.0
END DESCRIPTION:
XS GIS Cut Line= 3
      1365528.80      1116711.26      1365078.05      1116794.11
      1364566.47      1116872.15
#Sta/Elev= 30
  4541.7 1749.55  4578.3 1744.61  4592.8 1740.67  4612.6 1740.91  4623.4 1735.89
  4749.7 1714.65  4763.6 1711.58  4808.8 1694.39  4858.7 1682.83  4921.1 1677.37
  4923.8 1678.48  4924.8 1682.91  4935.2 1676.89  4958.9 1675.88  4972.5 1677.03
  4978.9 1671.76  4990.8 1674.53  4997.7 1671.76  4998.2 1670.76  5002.3 1671.76
  5016.5 1677.44  5037.2 1675.70  5121.8 1682.09  5138.3 1680.62  5162.7 1683.50
  5208.8 1692.56  5271.9 1711.79  5336.5 1727.83  5474.6 1755.08  5517.5 1762.16
#Mann=3,-1,0
  4541.7    0.15       0  4997.7    0.05       0  5002.3    0.15       0
Bank Sta=4997.7,5002.3
XS Rating Curve= 0
Exp/Cntr=0.3,0.1

Type RM Length L Ch R = 1,197500,500,500,500
BEGIN DESCRIPTION:
Chauga River 395.0
END DESCRIPTION:
XS GIS Cut Line= 3
      1365437.70      1116568.60      1364958.53      1116386.53
      1364572.52      1116219.49
#Sta/Elev= 30
  4487.4 1732.49  4537.5 1725.99  4578.6 1724.63  4594.5 1719.41  4683.1 1712.97
  4729.5 1695.88  4761.0 1680.07  4776.4 1676.79  4872.7 1671.52  4881.4 1676.30
  4893.1 1675.63  4893.7 1673.12  4893.9 1676.14  4904.2 1671.96  4912.3 1671.74
  4912.5 1675.04  4920.2 1670.89  4936.1 1669.48  4948.2 1671.92  4989.4 1670.99
  4997.7 1668.34  4998.2 1667.34  5002.3 1668.34  5005.2 1671.66  5018.3 1674.62
  5061.0 1675.14  5128.1 1682.68  5213.5 1702.33  5282.9 1714.88  5420.6 1724.02
#Mann=3,-1,0
  4487.4    0.15       0  4997.7    0.05       0  5002.3    0.15       0
Bank Sta=4997.7,5002.3
XS Rating Curve= 0
Exp/Cntr=0.3,0.1

Type RM Length L Ch R = 1,197000,500,500,500
BEGIN DESCRIPTION:
Chauga River 394.0
END DESCRIPTION:
XS GIS Cut Line= 3
      1365740.08      1116262.92      1365297.75      1116022.38
      1364850.56      1115795.39
#Sta/Elev= 30
  4496.5 1729.50  4556.8 1725.38  4634.4 1715.34  4768.9 1689.60  4784.2 1683.80
  4787.3 1685.12  4812.2 1685.52  4847.5 1678.20  4873.4 1678.22  4983.5 1667.91
  4989.6 1669.72  4997.7 1665.33  4998.2 1664.33  5002.3 1665.33  5014.6 1668.03
  5155.6 1670.83  5237.1 1675.62  5267.5 1681.91  5273.0 1685.90  5281.8 1687.16
  5296.9 1694.25  5316.5 1699.25  5324.8 1702.55  5326.8 1705.05  5338.2 1704.86
  5359.1 1710.08  5382.7 1712.99  5432.3 1716.54  5483.3 1722.95  5501.5 1722.63
#Mann=3,-1,0
  4496.5    0.15       0  4997.7    0.05       0  5002.3    0.15       0
Bank Sta=4997.7,5002.3
XS Rating Curve= 0
Exp/Cntr=0.3,0.1

Type RM Length L Ch R = 1,196500,500,500,500
BEGIN DESCRIPTION:
Chauga River 393.0
END DESCRIPTION:
XS GIS Cut Line= 3
      1366113.46      1115497.90      1365389.08      1115600.41
      1364893.04      1115619.33
#Sta/Elev= 30
  4268.4 1712.23  4370.3 1702.93  4445.8 1692.77  4468.3 1686.19  4479.8 1686.52
  4515.8 1680.79  4561.3 1670.84  4572.3 1670.17  4576.4 1673.36  4588.5 1671.03
  4715.3 1672.05  4883.6 1667.91  4916.9 1668.70  4954.2 1672.59  4972.7 1670.04
  4997.7 1660.66  4998.2 1659.66  5002.3 1660.66  5042.3 1668.71  5149.5 1669.66
  5163.6 1667.80  5169.8 1671.78  5188.1 1673.72  5252.2 1686.23  5271.5 1687.51
  5290.8 1692.30  5361.9 1702.36  5435.7 1716.59  5473.1 1718.01  5496.4 1724.54
#Mann=3,-1,0
  4268.4    0.15       0  4997.7    0.05       0  5002.3    0.15       0
Bank Sta=4997.7,5002.3
XS Rating Curve= 0
Exp/Cntr=0.3,0.1

Type RM Length L Ch R = 1,196000,529,529,529
BEGIN DESCRIPTION:
Chauga River 392.0
END DESCRIPTION:
XS GIS Cut Line= 3
      1366024.98      1115075.00      1365429.24      1115128.12
      1364975.01      1115196.16
#Sta/Elev= 30
  4401.9 1729.30  4454.3 1722.06  4518.7 1710.04  4537.9 1701.19  4563.4 1701.33
  4577.0 1695.76  4586.2 1697.25  4590.8 1694.71  4591.1 1696.46  4596.0 1696.78
  4612.3 1692.57  4623.1 1692.21  4628.4 1688.34  4705.3 1669.77  4832.5 1664.62
  4975.3 1666.21  4997.7 1659.75  4998.2 1658.75  5002.3 1659.75  5011.9 1663.68
  5032.8 1666.43  5096.8 1668.96  5147.7 1676.39  5337.9 1683.00  5412.2 1690.18
  5416.8 1688.91  5421.2 1690.88  5432.7 1691.25  5435.2 1689.17  5459.3 1697.21
#Mann=3,-1,0
  4401.9    0.15       0  4997.7    0.05       0  5002.3    0.15       0
Bank Sta=4997.7,5002.3
XS Rating Curve= 0
Exp/Cntr=0.3,0.1

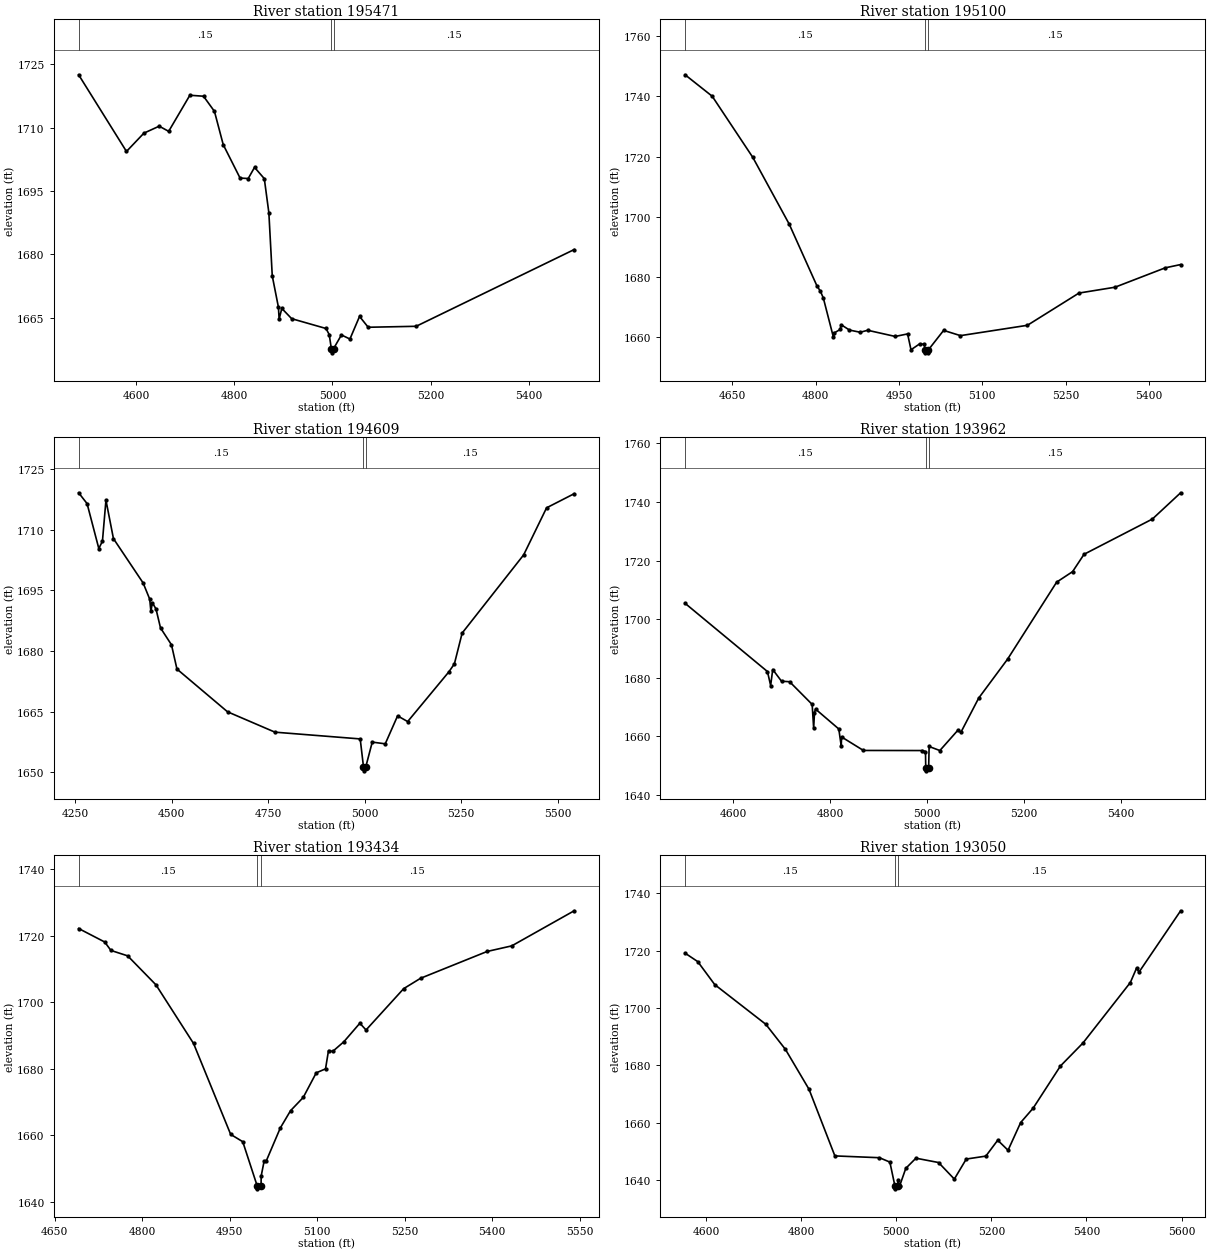
Type RM Length L Ch R = 1,195471,371,371,371
BEGIN DESCRIPTION:
Chauga River 391.0
END DESCRIPTION:
XS GIS Cut Line= 3
      1365964.69      1114555.62      1365461.09      1114673.89
      1365059.17      1114958.70
#Sta/Elev= 30
  4482.7 1722.51  4580.2 1704.34  4615.7 1708.68  4646.9 1710.33  4666.2 1709.11
  4709.4 1717.66  4737.2 1717.43  4759.5 1713.84  4777.4 1705.95  4811.7 1698.04
  4828.3 1697.93  4841.2 1700.57  4861.1 1697.90  4870.4 1689.80  4877.3 1674.87
  4889.9 1667.43  4891.3 1664.62  4896.8 1667.15  4916.9 1664.72  4986.8 1662.40
  4993.4 1660.96  4997.7 1657.63  4998.2 1656.63  5002.3 1657.63  5018.3 1660.87
  5035.6 1659.90  5055.2 1665.26  5072.8 1662.69  5170.6 1662.92  5492.6 1681.10
#Mann=3,-1,0
  4482.7    0.15       0  4997.7    0.05       0  5002.3    0.15       0
Bank Sta=4997.7,5002.3
XS Rating Curve= 0
Exp/Cntr=0.3,0.1

Type RM Length L Ch R = 1,195100,491,491,491
BEGIN DESCRIPTION:
Chauga River 390.0
END DESCRIPTION:
XS GIS Cut Line= 3
      1365277.98      1114138.14      1365184.51      1114562.67
      1365022.73      1114989.86
#Sta/Elev= 30
  4565.3 1747.14  4614.1 1740.01  4687.1 1719.73  4752.6 1697.57  4802.4 1677.11
  4808.8 1675.27  4814.0 1673.04  4832.1 1660.05  4834.0 1661.49  4844.4 1662.63
  4846.0 1664.19  4861.0 1662.41  4880.3 1661.68  4893.8 1662.34  4943.3 1660.29
  4965.6 1661.13  4971.7 1655.87  4987.3 1657.83  4995.6 1657.68  4997.0 1655.85
  4997.5 1654.85  5002.5 1654.85  5003.0 1655.85  5030.4 1662.30  5060.7 1660.56
  5181.1 1663.99  5273.9 1674.69  5338.7 1676.63  5429.2 1683.07  5456.8 1684.15
#Mann=3,-1,0
  4565.3    0.15       0  4997.0    0.05       0  5003.0    0.15       0
Bank Sta=4997,5003
XS Rating Curve= 0
Exp/Cntr=0.3,0.1

Type RM Length L Ch R = 1,194609,647,647,647
BEGIN DESCRIPTION:
Chauga River 389.0
END DESCRIPTION:
XS GIS Cut Line= 3
      1364713.98      1113906.58      1364710.94      1114647.78
      1364698.80      1115190.64
#Sta/Elev= 30
  4258.8 1719.14  4280.7 1716.46  4311.1 1705.36  4320.5 1707.18  4329.6 1717.30
  4349.0 1707.81  4425.9 1696.85  4443.0 1692.85  4446.0 1689.86  4450.0 1691.93
  4459.3 1690.42  4471.0 1685.73  4499.4 1681.56  4513.6 1675.56  4644.6 1665.00
  4767.6 1659.96  4988.5 1658.29  4997.0 1651.40  4997.5 1650.40  5003.0 1651.40
  5019.7 1657.50  5053.4 1657.08  5085.4 1663.99  5111.5 1662.58  5218.2 1674.86
  5232.6 1676.85  5252.7 1684.46  5412.1 1703.79  5471.5 1715.42  5543.0 1718.91
#Mann=3,-1,0
  4258.8    0.15       0  4997.0    0.05       0  5003.0    0.15       0
Bank Sta=4997,5003
XS Rating Curve= 0
Exp/Cntr=0.3,0.1

Type RM Length L Ch R = 1,193962,528,528,528
BEGIN DESCRIPTION:
Chauga River 388.0
END DESCRIPTION:
XS GIS Cut Line= 3
      1364037.01      1114349.17      1364185.77      1114825.80
      1364267.72      1115341.83
#Sta/Elev= 30
  4500.8 1705.40  4670.6 1682.14  4677.2 1677.38  4681.5 1682.83  4699.6 1678.84
  4716.3 1678.67  4762.8 1670.93  4765.9 1662.83  4767.6 1668.17  4769.8 1669.34
  4817.7 1662.56  4822.7 1656.83  4823.5 1659.83  4868.5 1655.23  4990.3 1655.20
  4996.5 1654.83  4997.0 1649.28  4997.5 1648.28  5003.0 1649.28  5004.0 1656.58
  5026.1 1655.20  5062.9 1662.06  5069.7 1661.48  5106.2 1673.09  5165.8 1686.38
  5266.9 1712.62  5299.8 1716.21  5323.4 1722.12  5464.3 1734.14  5522.6 1743.10
#Mann=3,-1,0
  4500.8    0.15       0  4997.0    0.05       0  5003.0    0.15       0
Bank Sta=4997,5003
XS Rating Curve= 0
Exp/Cntr=0.3,0.1

Type RM Length L Ch R = 1,193434,384,384,384
BEGIN DESCRIPTION:
Chauga River 387.0
END DESCRIPTION:
XS GIS Cut Line= 4
      1363627.20      1114558.68      1363666.53      1114864.87
      1363712.20      1114956.33      1364030.93      1115256.85
#Sta/Elev= 30
  4691.3 1722.16  4736.0 1718.10  4746.6 1715.57  4775.3 1713.94  4823.8 1705.22
  4888.2 1687.59  4951.8 1660.26  4972.5 1658.06  4997.0 1644.89  4997.5 1643.89
  5003.0 1644.89  5003.9 1644.89  5004.0 1647.70  5009.2 1652.31  5012.6 1652.21
  5036.8 1662.18  5054.3 1667.37  5076.1 1671.37  5098.4 1678.77  5114.3 1679.96
  5119.4 1685.47  5126.5 1685.19  5145.7 1688.11  5173.1 1693.68  5183.7 1691.65
  5248.2 1704.08  5277.2 1707.20  5391.2 1715.26  5433.4 1716.94  5540.3 1727.49
#Mann=3,-1,0
  4691.3    0.15       0  4997.0    0.05       0  5003.0    0.15       0
Bank Sta=4997,5003
XS Rating Curve= 0
Exp/Cntr=0.3,0.1

Type RM Length L Ch R = 1,193050,550,550,550
BEGIN DESCRIPTION:
Chauga River 386.0
END DESCRIPTION:
XS GIS Cut Line= 3
      1363566.49      1114504.01      1363356.98      1114895.93
      1363197.79      1115472.45
#Sta/Elev= 30
  4555.6 1719.14  4582.2 1716.19  4618.0 1708.15  4725.4 1694.30  4766.6 1685.56
  4816.3 1671.61  4870.7 1648.34  4964.4 1647.71  4986.4 1646.18  4997.0 1637.84
  4997.5 1636.84  5003.0 1637.84  5003.5 1640.05  5006.9 1637.84  5019.9 1644.00
  5041.2 1647.54  5088.8 1646.03  5122.0 1640.25  5147.1 1647.24  5188.3 1648.27
  5213.3 1653.82  5235.0 1650.31  5261.6 1660.00  5287.8 1665.01  5345.3 1679.75
  5392.5 1687.75  5492.3 1708.89  5505.4 1713.93  5510.5 1712.52  5598.1 1733.94
#Mann=3,-1,0
  4555.6    0.15       0  4997.0    0.05       0  5003.0    0.15       0
Bank Sta=4997,5003
XS Rating Curve= 0
Exp/Cntr=0.3,0.1

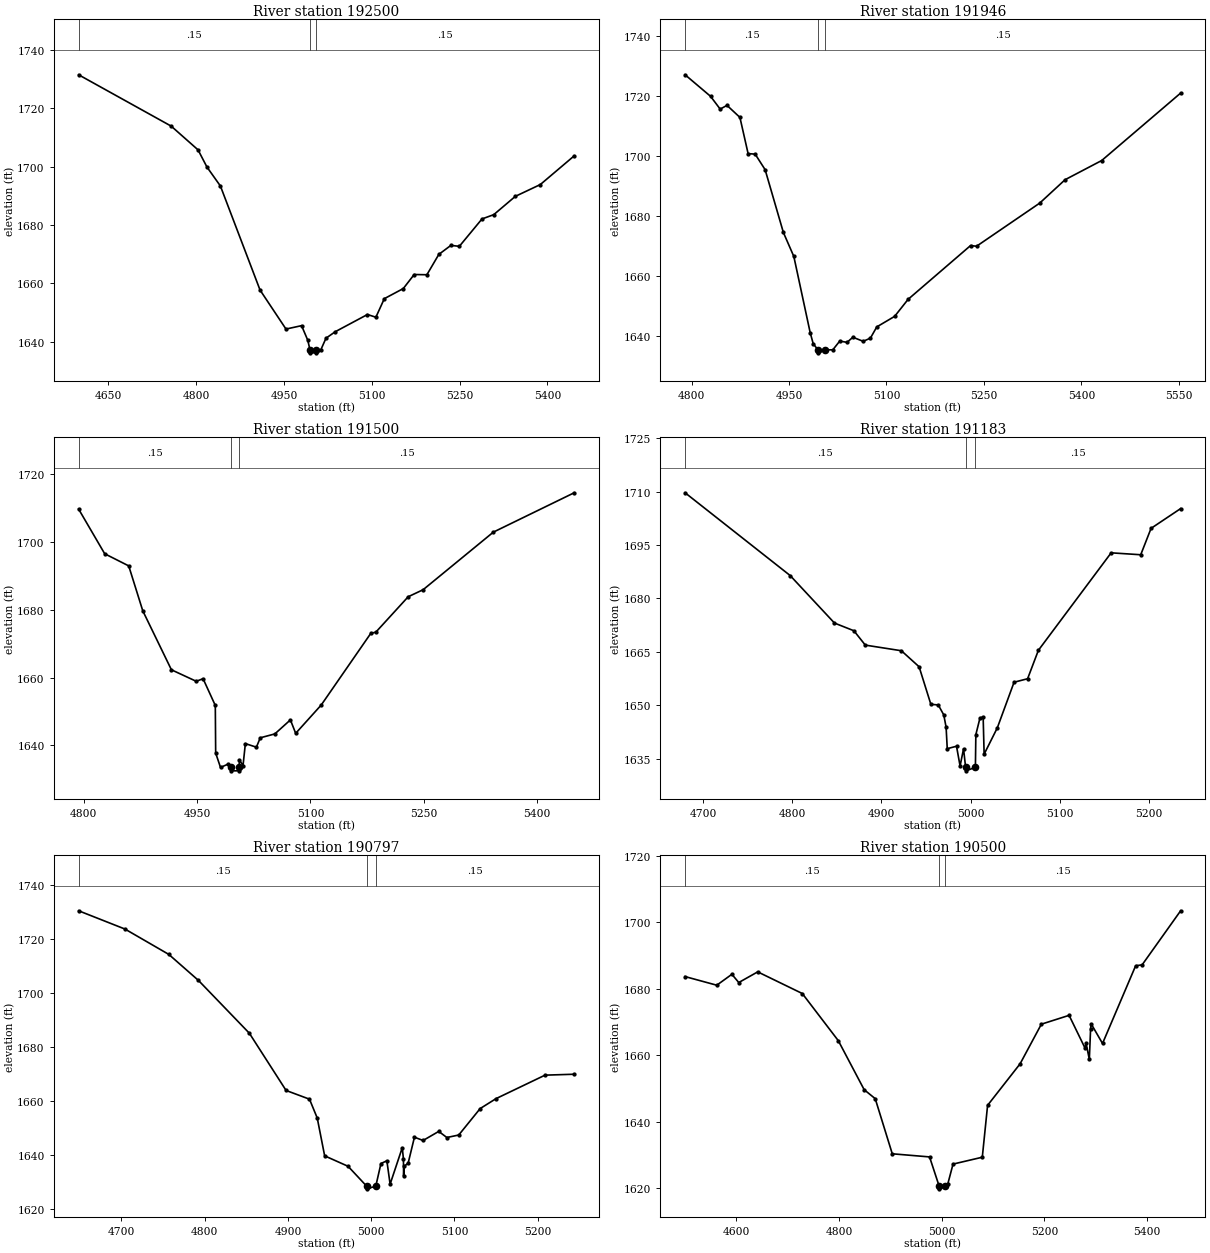
Type RM Length L Ch R = 1,192500,554,554,554
BEGIN DESCRIPTION:
Chauga River 385.0
END DESCRIPTION:
XS GIS Cut Line= 3
      1363268.96      1114194.42      1363089.38      1114552.51
      1362871.33      1114941.12
#Sta/Elev= 30
  4599.4 1731.49  4757.5 1713.88  4803.3 1705.75  4818.5 1699.87  4841.5 1693.36
  4909.2 1657.69  4953.5 1644.32  4980.1 1645.49  4990.7 1640.48  4994.5 1637.17
  4995.0 1636.17  5005.0 1636.17  5005.5 1637.17  5012.9 1637.17  5021.8 1641.19
  5037.8 1643.43  5092.6 1649.31  5107.0 1648.38  5121.4 1654.74  5153.8 1658.21
  5172.4 1663.02  5194.1 1662.94  5214.5 1669.92  5235.1 1673.01  5249.5 1672.68
  5288.2 1682.07  5308.3 1683.54  5345.1 1689.81  5387.8 1693.86  5445.6 1703.69
#Mann=3,-1,0
  4599.4    0.15       0  4994.5    0.05       0  5005.5    0.15       0
Bank Sta=4994.5,5005.5
XS Rating Curve= 0
Exp/Cntr=0.3,0.1

Type RM Length L Ch R = 1,191946,446,446,446
BEGIN DESCRIPTION:
Chauga River 384.0
END DESCRIPTION:
XS GIS Cut Line= 3
      1362928.96      1114110.61      1362756.52      1114230.46
      1362291.48      1114529.52
#Sta/Elev= 30
  4790.0 1726.94  4829.2 1719.77  4844.0 1715.52  4854.5 1716.76  4874.4 1712.76
  4887.0 1700.71  4897.9 1700.53  4913.2 1695.36  4941.3 1674.47  4957.4 1666.48
  4982.6 1641.10  4987.2 1637.47  4994.5 1635.41  4995.0 1634.41  5005.5 1635.41
  5017.4 1635.41  5028.1 1638.33  5039.3 1637.90  5048.3 1639.60  5064.2 1638.24
  5075.3 1639.31  5085.1 1643.04  5112.6 1646.55  5133.3 1652.21  5229.5 1670.11
  5238.7 1669.88  5335.9 1684.23  5375.0 1692.02  5431.4 1698.41  5552.9 1720.85
#Mann=3,-1,0
  4790.0    0.15       0  4994.5    0.05       0  5005.5    0.15       0
Bank Sta=4994.5,5005.5
XS Rating Curve= 0
Exp/Cntr=0.3,0.1

Type RM Length L Ch R = 1,191500,317,317,317
BEGIN DESCRIPTION:
Chauga River 383.0
END DESCRIPTION:
XS GIS Cut Line= 3
      1362746.86      1113992.20      1362540.15      1113986.35
      1362091.14      1113977.02
#Sta/Elev= 30
  4793.2 1709.78  4827.7 1696.60  4859.5 1693.02  4878.1 1679.76  4916.0 1662.35
  4948.9 1658.95  4957.9 1659.72  4974.1 1651.82  4974.6 1637.76  4981.0 1633.52
  4991.1 1634.52  4994.5 1633.52  4995.0 1632.52  5005.0 1632.52  5005.5 1633.52
  5006.1 1635.69  5010.8 1634.08  5013.9 1640.56  5028.5 1639.50  5033.6 1642.27
  5052.9 1643.42  5073.5 1647.56  5080.5 1643.59  5114.3 1651.95  5179.9 1673.10
  5186.6 1673.46  5229.4 1683.91  5249.2 1685.99  5342.1 1702.98  5449.1 1714.60
#Mann=3,-1,0
  4793.2    0.15       0  4994.5    0.05       0  5005.5    0.15       0
Bank Sta=4994.5,5005.5
XS Rating Curve= 0
Exp/Cntr=0.3,0.1

Type RM Length L Ch R = 1,191183,386,386,386
BEGIN DESCRIPTION:
Chauga River 382.5
END DESCRIPTION:
XS GIS Cut Line= 3
      1362762.04      1113944.85      1362538.02      1113715.78
      1362349.14      1113574.46
#Sta/Elev= 30
  4679.6 1709.67  4797.6 1686.42  4847.3 1673.09  4869.1 1670.93  4881.9 1666.90
  4922.4 1665.32  4942.3 1660.82  4955.5 1650.28  4963.8 1650.10  4970.0 1647.30
  4972.6 1643.86  4973.9 1637.82  4984.3 1638.51  4988.3 1632.96  4992.2 1637.80
  4994.5 1632.60  4995.0 1631.60  5005.5 1632.60  5006.0 1641.76  5010.6 1646.42
  5014.2 1646.73  5015.3 1636.28  5030.1 1643.67  5048.9 1656.48  5064.1 1657.46
  5076.2 1665.44  5157.9 1692.81  5191.1 1692.27  5202.7 1699.68  5235.9 1705.23
#Mann=3,-1,0
  4679.6    0.15       0  4994.5    0.05       0  5005.5    0.15       0
Bank Sta=4994.5,5005.5
XS Rating Curve= 0
Exp/Cntr=0.3,0.1

Type RM Length L Ch R = 1,190797,297,297,297
BEGIN DESCRIPTION:
Chauga River 382.0
END DESCRIPTION:
XS GIS Cut Line= 3
      1363162.71      1113893.22      1362865.93      1113705.24
      1362683.09      1113544.13
#Sta/Elev= 30
  4648.7 1730.61  4704.3 1723.85  4757.0 1714.45  4792.6 1704.81  4853.7 1685.26
  4897.8 1664.07  4925.9 1660.84  4935.2 1653.86  4944.1 1639.86  4972.2 1635.99
  4994.5 1628.64  4995.0 1627.64  5005.5 1628.64  5011.7 1637.02  5018.8 1638.02
  5022.7 1629.37  5037.3 1642.88  5038.7 1638.66  5038.9 1632.40  5039.6 1635.95
  5044.4 1637.21  5051.9 1646.76  5062.3 1645.55  5081.1 1648.91  5090.8 1646.65
  5105.1 1647.57  5130.8 1657.36  5149.9 1661.05  5208.7 1669.74  5243.7 1670.08
#Mann=3,-1,0
  4648.7    0.15       0  4994.5    0.05       0  5005.5    0.15       0
Bank Sta=4994.5,5005.5
XS Rating Curve= 0
Exp/Cntr=0.3,0.1

Type RM Length L Ch R = 1,190500,398,398,398
BEGIN DESCRIPTION:
Chauga River 381.0
END DESCRIPTION:
XS GIS Cut Line= 3
      1363332.77      1113571.46      1362852.63      1113432.67
      1362391.62      1113371.09
#Sta/Elev= 30
  4500.2 1683.71  4561.9 1681.11  4591.3 1684.40  4604.7 1681.92  4641.6 1685.13
  4728.4 1678.61  4798.5 1664.42  4848.9 1649.65  4870.4 1646.96  4903.6 1630.36
  4976.2 1629.42  4994.5 1620.81  4995.0 1619.81  5005.5 1620.81  5011.9 1621.39
  5021.9 1627.26  5078.9 1629.33  5089.2 1644.95  5152.5 1657.45  5193.9 1669.38
  5247.9 1672.04  5279.0 1662.16  5281.0 1663.63  5287.3 1658.80  5289.8 1668.04
  5290.9 1669.47  5313.0 1663.57  5377.5 1686.97  5390.1 1687.24  5465.1 1703.52
#Mann=3,-1,0
  4500.2    0.15       0  4994.5    0.05       0  5005.5    0.15       0
Bank Sta=4994.5,5005.5
XS Rating Curve= 0
Exp/Cntr=0.3,0.1

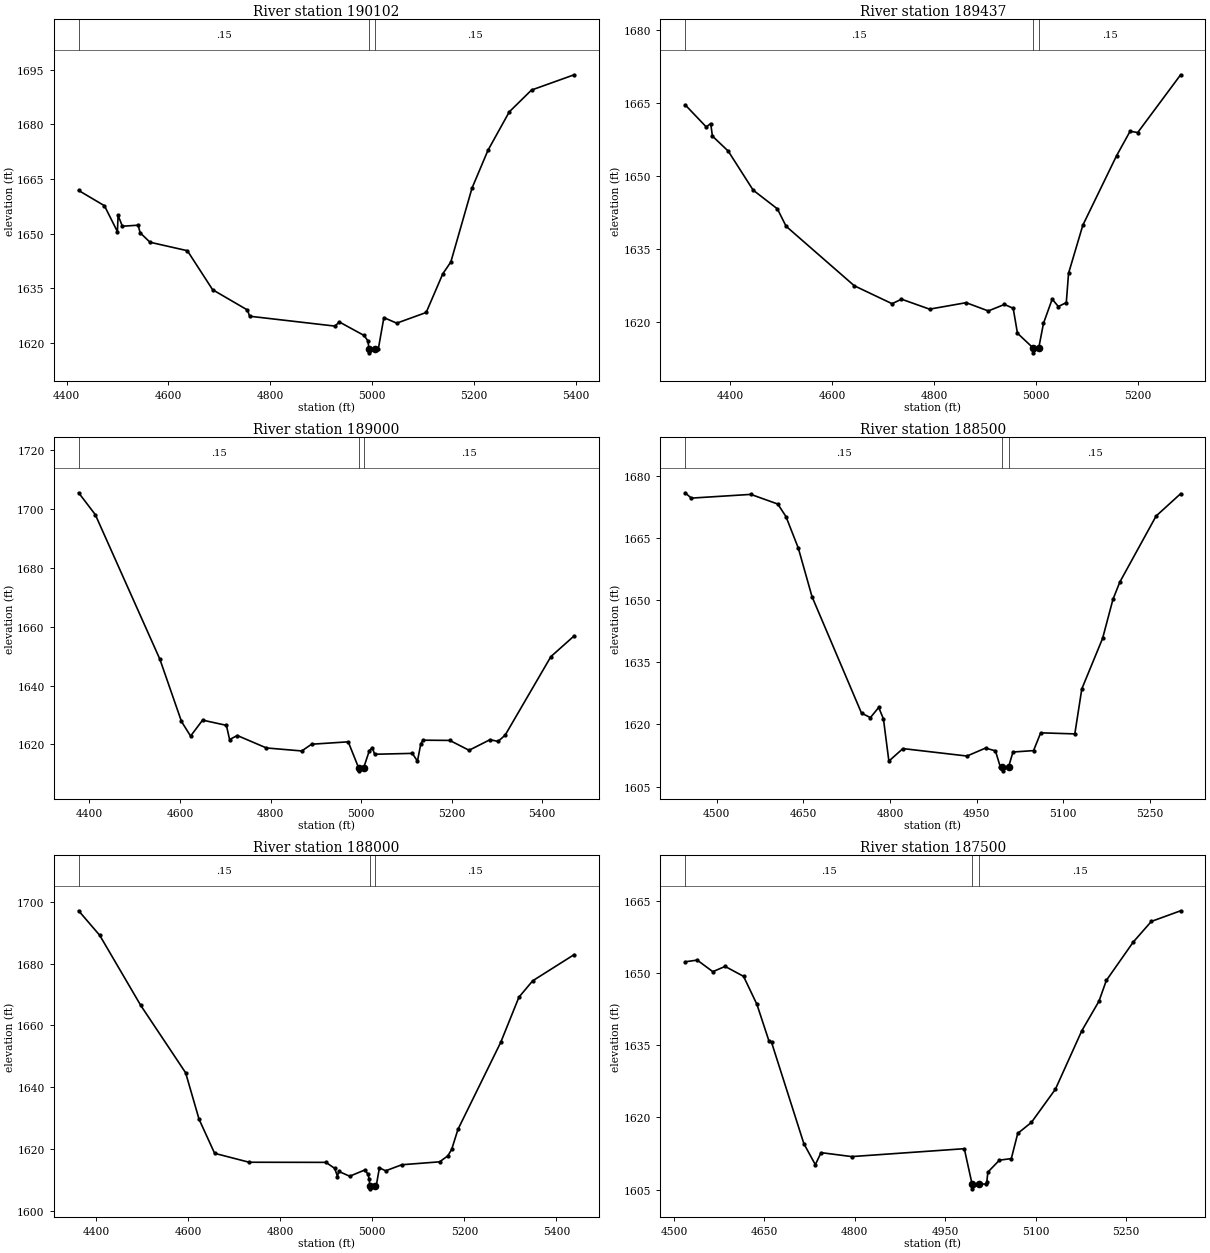
Type RM Length L Ch R = 1,190102,665,665,665
BEGIN DESCRIPTION:
Chauga River 380.0
END DESCRIPTION:
XS GIS Cut Line= 3
      1363431.19      1113424.80      1362957.53      1113096.69
      1362587.13      1112953.27
#Sta/Elev= 30
  4423.8 1661.84  4474.5 1657.64  4500.0 1650.51  4501.3 1654.99  4509.7 1652.00
  4540.7 1652.29  4544.6 1650.21  4564.0 1647.60  4637.4 1645.27  4687.0 1634.54
  4755.4 1628.96  4759.7 1627.25  4927.5 1624.53  4935.8 1625.68  4984.2 1621.98
  4991.7 1620.55  4994.5 1618.18  4995.0 1617.18  5005.5 1618.18  5012.4 1618.18
  5023.4 1626.87  5048.6 1625.34  5106.5 1628.28  5139.2 1638.94  5154.9 1642.16
  5196.5 1662.48  5227.9 1672.90  5269.7 1683.46  5313.4 1689.46  5397.2 1693.66
#Mann=3,-1,0
  4423.8    0.15       0  4994.5    0.05       0  5005.5    0.15       0
Bank Sta=4994.5,5005.5
XS Rating Curve= 0
Exp/Cntr=0.3,0.1

Type RM Length L Ch R = 1,189437,437,437,437
BEGIN DESCRIPTION:
Chauga River 379.0
END DESCRIPTION:
XS GIS Cut Line= 3
      1363740.40      1112990.26      1363108.58      1112715.69
      1362831.21      1112654.20
#Sta/Elev= 30
  4311.1 1664.73  4352.6 1660.17  4361.4 1660.87  4364.7 1658.29  4395.8 1655.20
  4444.7 1647.18  4492.3 1643.33  4509.4 1639.75  4643.3 1627.52  4717.5 1623.83
  4736.0 1624.76  4791.1 1622.71  4862.9 1624.04  4906.5 1622.34  4938.1 1623.68
  4955.3 1622.89  4963.7 1617.76  4994.5 1614.73  4995.0 1613.73  5005.5 1614.73
  5014.8 1619.80  5031.9 1624.77  5044.0 1623.25  5059.6 1624.06  5064.0 1630.08
  5092.1 1639.98  5158.3 1654.25  5184.9 1659.29  5199.8 1659.01  5284.1 1670.89
#Mann=3,-1,0
  4311.1    0.15       0  4994.5    0.05       0  5005.5    0.15       0
Bank Sta=4994.5,5005.5
XS Rating Curve= 0
Exp/Cntr=0.3,0.1

Type RM Length L Ch R = 1,189000,500,500,500
BEGIN DESCRIPTION:
Chauga River 378.0
END DESCRIPTION:
XS GIS Cut Line= 3
      1363942.93      1112446.42      1363319.18      1112453.80
      1362850.06      1112419.10
#Sta/Elev= 30
  4376.2 1705.45  4413.0 1698.03  4555.6 1648.93  4603.3 1627.79  4623.4 1622.83
  4649.9 1628.25  4702.5 1626.48  4709.5 1621.65  4726.5 1623.03  4790.9 1618.80
  4869.0 1617.78  4890.6 1620.07  4971.5 1620.88  4994.5 1612.03  4995.0 1611.03
  5005.5 1612.03  5018.1 1617.87  5024.8 1618.92  5029.7 1616.66  5112.9 1616.96
  5124.4 1614.33  5131.7 1620.20  5136.7 1621.44  5195.8 1621.36  5238.3 1618.01
  5284.6 1621.61  5302.3 1621.02  5318.0 1623.15  5419.0 1649.82  5470.4 1656.86
#Mann=3,-1,0
  4376.2    0.15       0  4994.5    0.05       0  5005.5    0.15       0
Bank Sta=4994.5,5005.5
XS Rating Curve= 0
Exp/Cntr=0.3,0.1

Type RM Length L Ch R = 1,188500,500,500,500
BEGIN DESCRIPTION:
Chauga River 377.0
END DESCRIPTION:
XS GIS Cut Line= 3
      1364006.66      1112048.75      1363454.52      1112104.02
      1363153.67      1112063.93
#Sta/Elev= 30
  4445.1 1676.01  4455.9 1674.72  4559.0 1675.62  4605.6 1673.29  4619.8 1670.27
  4641.2 1662.64  4665.0 1650.88  4750.7 1622.74  4766.1 1621.66  4780.5 1624.12
  4788.7 1621.33  4798.1 1611.14  4822.4 1614.17  4933.4 1612.37  4965.5 1614.29
  4982.7 1613.62  4991.0 1609.79  4994.5 1609.79  4995.0 1608.79  5005.5 1609.79
  5013.1 1613.34  5048.7 1613.68  5061.1 1617.98  5120.2 1617.72  5132.3 1628.60
  5168.3 1640.81  5186.3 1650.26  5198.2 1654.44  5261.0 1670.39  5303.5 1675.79
#Mann=3,-1,0
  4445.1    0.15       0  4994.5    0.05       0  5005.5    0.15       0
Bank Sta=4994.5,5005.5
XS Rating Curve= 0
Exp/Cntr=0.3,0.1

Type RM Length L Ch R = 1,188000,500,500,500
BEGIN DESCRIPTION:
Chauga River 376.0
END DESCRIPTION:
XS GIS Cut Line= 3
      1363925.40      1111504.31      1363309.26      1111670.28
      1362889.56      1111797.99
#Sta/Elev= 30
  4361.9 1697.10  4407.7 1689.16  4496.9 1666.45  4594.4 1644.65  4623.6 1629.60
  4657.4 1618.57  4732.4 1615.68  4899.3 1615.64  4918.4 1613.69  4924.4 1611.04
  4927.0 1612.73  4950.9 1611.15  4983.6 1613.17  4990.4 1611.90  4993.5 1610.17
  4994.5 1608.07  4995.0 1607.07  5005.5 1608.07  5008.6 1608.07  5015.5 1613.88
  5029.0 1612.91  5064.2 1614.87  5146.4 1615.82  5164.1 1617.74  5172.5 1619.83
  5186.2 1626.33  5279.1 1654.50  5318.6 1669.11  5348.5 1674.42  5438.7 1682.91
#Mann=3,-1,0
  4361.9    0.15       0  4994.5    0.05       0  5005.5    0.15       0
Bank Sta=4994.5,5005.5
XS Rating Curve= 0
Exp/Cntr=0.3,0.1

Type RM Length L Ch R = 1,187500,500,500,500
BEGIN DESCRIPTION:
Chauga River 375.0
END DESCRIPTION:
XS GIS Cut Line= 3
      1363289.77      1110925.94      1363009.21      1111317.50
      1362724.42      1111504.32
#Sta/Elev= 30
  4518.3 1652.31  4538.4 1652.66  4564.3 1650.26  4584.7 1651.35  4615.3 1649.29
  4637.5 1643.46  4657.3 1635.92  4661.8 1635.56  4715.4 1614.52  4734.4 1610.16
  4743.9 1612.66  4794.8 1611.84  4981.6 1613.48  4994.5 1606.14  4995.0 1605.14
  5005.5 1606.14  5016.8 1606.14  5018.9 1606.49  5020.7 1608.61  5039.9 1611.10
  5059.6 1611.42  5070.3 1616.66  5092.9 1618.93  5132.8 1625.84  5176.5 1637.96
  5205.1 1644.13  5217.3 1648.44  5262.0 1656.42  5292.0 1660.70  5340.6 1662.91
#Mann=3,-1,0
  4518.3    0.15       0  4994.5    0.05       0  5005.5    0.15       0
Bank Sta=4994.5,5005.5
XS Rating Curve= 0
Exp/Cntr=0.3,0.1

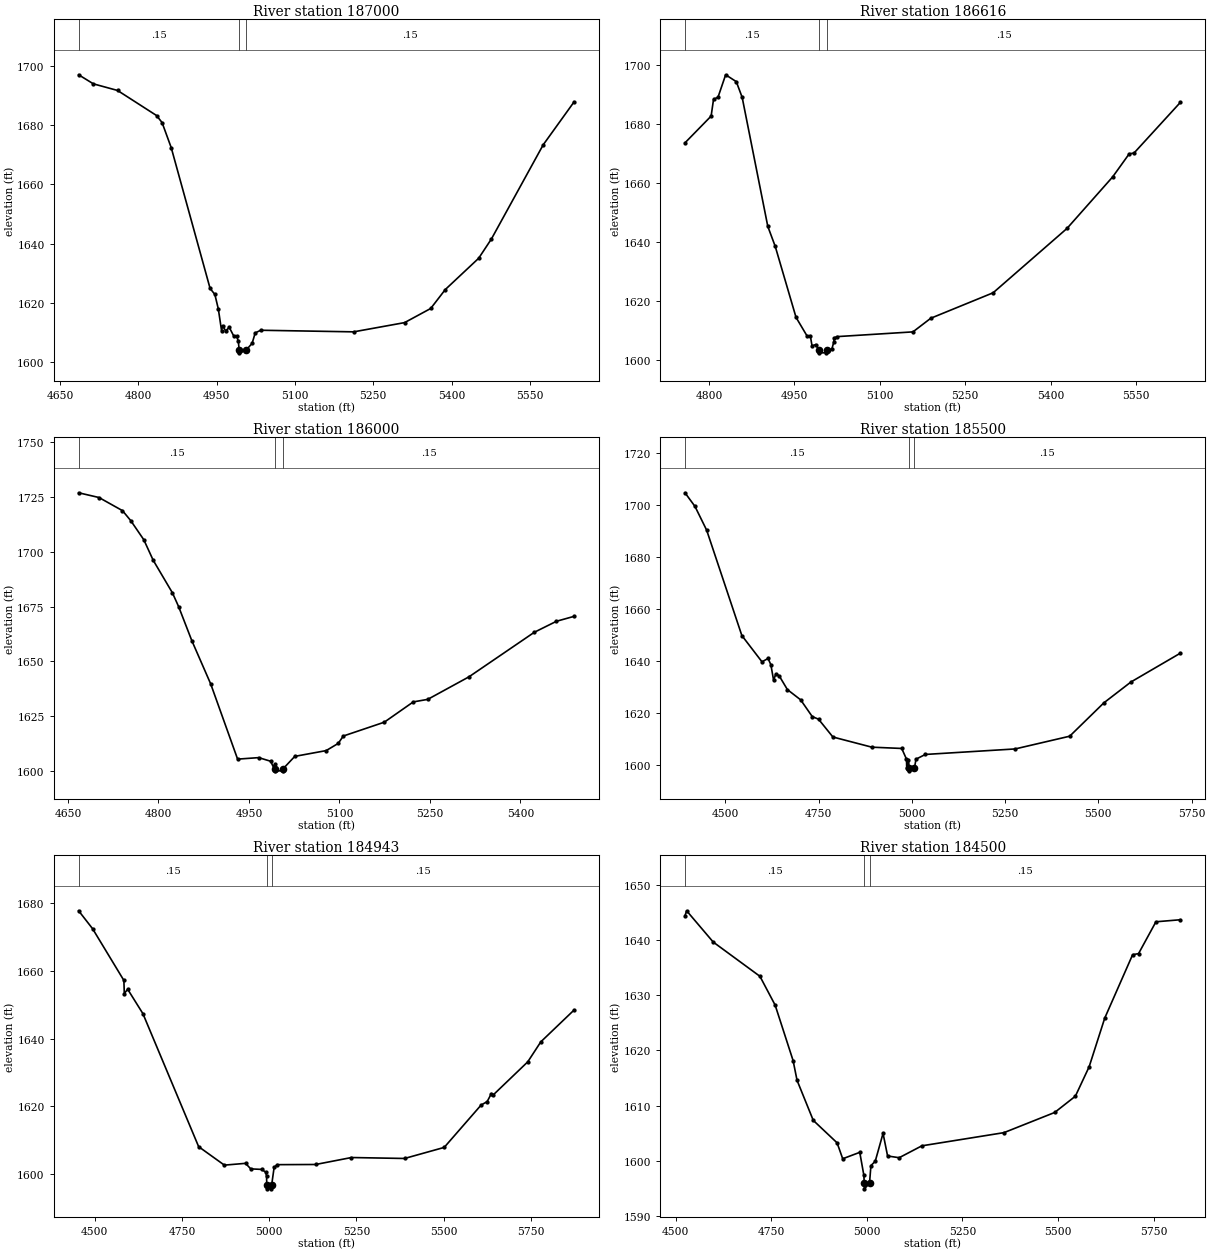
Type RM Length L Ch R = 1,187000,384,384,384
BEGIN DESCRIPTION:
Chauga River 374.0
END DESCRIPTION:
XS GIS Cut Line= 3
      1363150.56      1110749.48      1362859.02      1110866.91
      1362321.86      1111204.82
#Sta/Elev= 30
  4685.7 1696.91  4714.0 1693.85  4760.2 1691.63  4834.9 1683.19  4845.5 1680.82
  4863.0 1672.39  4937.5 1624.94  4946.6 1622.93  4953.3 1617.99  4959.5 1610.66
  4961.3 1612.42  4967.3 1610.65  4974.2 1611.84  4983.0 1608.83  4988.2 1608.82
  4991.6 1607.17  4993.1 1604.25  4993.6 1603.25  5006.9 1604.25  5018.0 1606.46
  5023.9 1609.96  5034.4 1610.86  5212.4 1610.32  5310.0 1613.43  5360.0 1618.19
  5388.0 1624.58  5451.9 1635.11  5476.4 1641.64  5575.5 1673.33  5634.6 1687.78
#Mann=3,-1,0
  4685.7    0.15       0  4993.1    0.05       0  5006.9    0.15       0
Bank Sta=4993.1,5006.9
XS Rating Curve= 0
Exp/Cntr=0.3,0.1

Type RM Length L Ch R = 1,186616,616,616,616
BEGIN DESCRIPTION:
Chauga River 373.0
END DESCRIPTION:
XS GIS Cut Line= 3
      1362762.04      1110458.03      1362579.55      1110616.97
      1362136.64      1111062.18
#Sta/Elev= 30
  4758.0 1673.60  4803.9 1682.67  4808.1 1688.33  4816.0 1689.08  4829.4 1696.68
  4848.1 1694.35  4858.4 1689.02  4903.4 1645.27  4916.5 1638.46  4953.0 1614.40
  4972.5 1608.05  4978.0 1608.21  4981.1 1604.75  4987.8 1605.19  4993.1 1603.38
  4993.6 1602.38  5006.4 1602.38  5006.9 1603.38  5015.8 1603.56  5019.5 1606.22
  5019.8 1607.44  5025.0 1607.88  5158.3 1609.49  5189.6 1614.11  5299.1 1622.75
  5428.8 1644.57  5509.0 1662.05  5538.1 1669.89  5546.4 1670.12  5628.0 1687.34
#Mann=3,-1,0
  4758.0    0.15       0  4993.1    0.05       0  5006.9    0.15       0
Bank Sta=4993.1,5006.9
XS Rating Curve= 0
Exp/Cntr=0.3,0.1

Type RM Length L Ch R = 1,186000,500,500,500
BEGIN DESCRIPTION:
Chauga River 372.0
END DESCRIPTION:
XS GIS Cut Line= 3
      1362224.71      1110105.90      1362062.34      1110395.72
      1361924.18      1110864.80
#Sta/Elev= 30
  4667.8 1727.01  4701.5 1724.85  4740.5 1718.84  4754.1 1714.31  4775.8 1705.56
  4791.4 1696.17  4823.3 1681.26  4833.7 1674.88  4855.4 1659.43  4886.7 1639.65
  4931.3 1605.27  4966.3 1605.96  4986.1 1604.30  4991.8 1600.92  4992.7 1602.89
  4993.1 1600.92  4993.6 1599.92  5006.4 1599.92  5006.9 1600.92  5026.1 1606.53
  5078.1 1609.17  5098.1 1612.46  5106.5 1615.83  5174.4 1622.15  5222.5 1631.43
  5246.4 1632.58  5314.8 1642.89  5423.1 1663.25  5459.8 1668.28  5489.0 1670.53
#Mann=3,-1,0
  4667.8    0.15       0  4993.1    0.05       0  5006.9    0.15       0
Bank Sta=4993.1,5006.9
XS Rating Curve= 0
Exp/Cntr=0.3,0.1

Type RM Length L Ch R = 1,185500,557,557,557
BEGIN DESCRIPTION:
Chauga River 371.0
END DESCRIPTION:
XS GIS Cut Line= 3
      1361825.01      1109624.96      1361624.26      1110198.97
      1361684.36      1110916.45
#Sta/Elev= 30
  4391.9 1704.76  4418.7 1699.50  4450.0 1690.34  4544.3 1649.73  4598.3 1639.59
  4614.5 1640.88  4622.1 1638.48  4629.4 1632.51  4635.6 1634.97  4644.5 1634.16
  4666.5 1628.87  4701.9 1624.94  4733.1 1618.47  4749.9 1617.47  4788.4 1610.60
  4892.9 1606.68  4972.9 1606.19  4985.6 1602.08  4986.3 1598.56  4990.9 1601.88
  4993.1 1598.56  4993.6 1597.56  5006.9 1598.56  5011.1 1602.06  5036.3 1603.88
  5276.8 1606.00  5423.1 1610.91  5514.8 1623.78  5587.3 1631.81  5720.0 1642.94
#Mann=3,-1,0
  4391.9    0.15       0  4993.1    0.05       0  5006.9    0.15       0
Bank Sta=4993.1,5006.9
XS Rating Curve= 0
Exp/Cntr=0.3,0.1

Type RM Length L Ch R = 1,184943,443,443,443
BEGIN DESCRIPTION:
Chauga River 370.0
END DESCRIPTION:
XS GIS Cut Line= 3
      1360849.51      1109853.90      1361175.56      1110292.48
      1361687.39      1111001.43
#Sta/Elev= 30
  4453.5 1677.78  4493.5 1672.48  4583.3 1657.18  4584.5 1653.30  4594.1 1654.58
  4637.8 1647.37  4797.7 1608.02  4871.5 1602.56  4932.2 1603.09  4947.2 1601.45
  4978.0 1601.30  4990.3 1600.47  4992.5 1599.25  4993.1 1596.55  4993.6 1595.55
  5006.4 1595.55  5006.9 1596.55  5014.2 1601.91  5023.4 1602.70  5133.1 1602.75
  5236.0 1604.81  5388.2 1604.53  5501.9 1607.80  5607.9 1620.34  5625.1 1621.34
  5637.3 1623.74  5641.2 1623.19  5741.6 1633.11  5779.0 1639.02  5874.4 1648.43
#Mann=3,-1,0
  4453.5    0.15       0  4993.1    0.05       0  5006.9    0.15       0
Bank Sta=4993.1,5006.9
XS Rating Curve= 0
Exp/Cntr=0.3,0.1

Type RM Length L Ch R = 1,184500,500,500,500
BEGIN DESCRIPTION:
Chauga River 369.0
END DESCRIPTION:
XS GIS Cut Line= 3
      1360512.61      1110197.00      1360882.06      1110496.67
      1361490.10      1111046.99
#Sta/Elev= 30
  4524.3 1644.35  4528.6 1645.25  4598.2 1639.59  4720.3 1633.40  4760.1 1628.19
  4807.0 1618.17  4817.4 1614.59  4859.8 1607.35  4922.1 1603.29  4936.8 1600.41
  4981.4 1601.57  4992.2 1597.39  4993.1 1595.97  4993.6 1594.97  5006.9 1595.97
  5010.6 1599.17  5021.9 1599.96  5042.3 1605.00  5054.2 1600.91  5084.5 1600.60
  5143.9 1602.75  5358.5 1605.13  5491.2 1608.78  5545.3 1611.72  5581.3 1617.04
  5622.1 1625.84  5695.0 1637.30  5710.6 1637.51  5756.0 1643.26  5820.1 1643.63
#Mann=3,-1,0
  4524.3    0.15       0  4993.1    0.05       0  5006.9    0.15       0
Bank Sta=4993.1,5006.9
XS Rating Curve= 0
Exp/Cntr=0.3,0.1