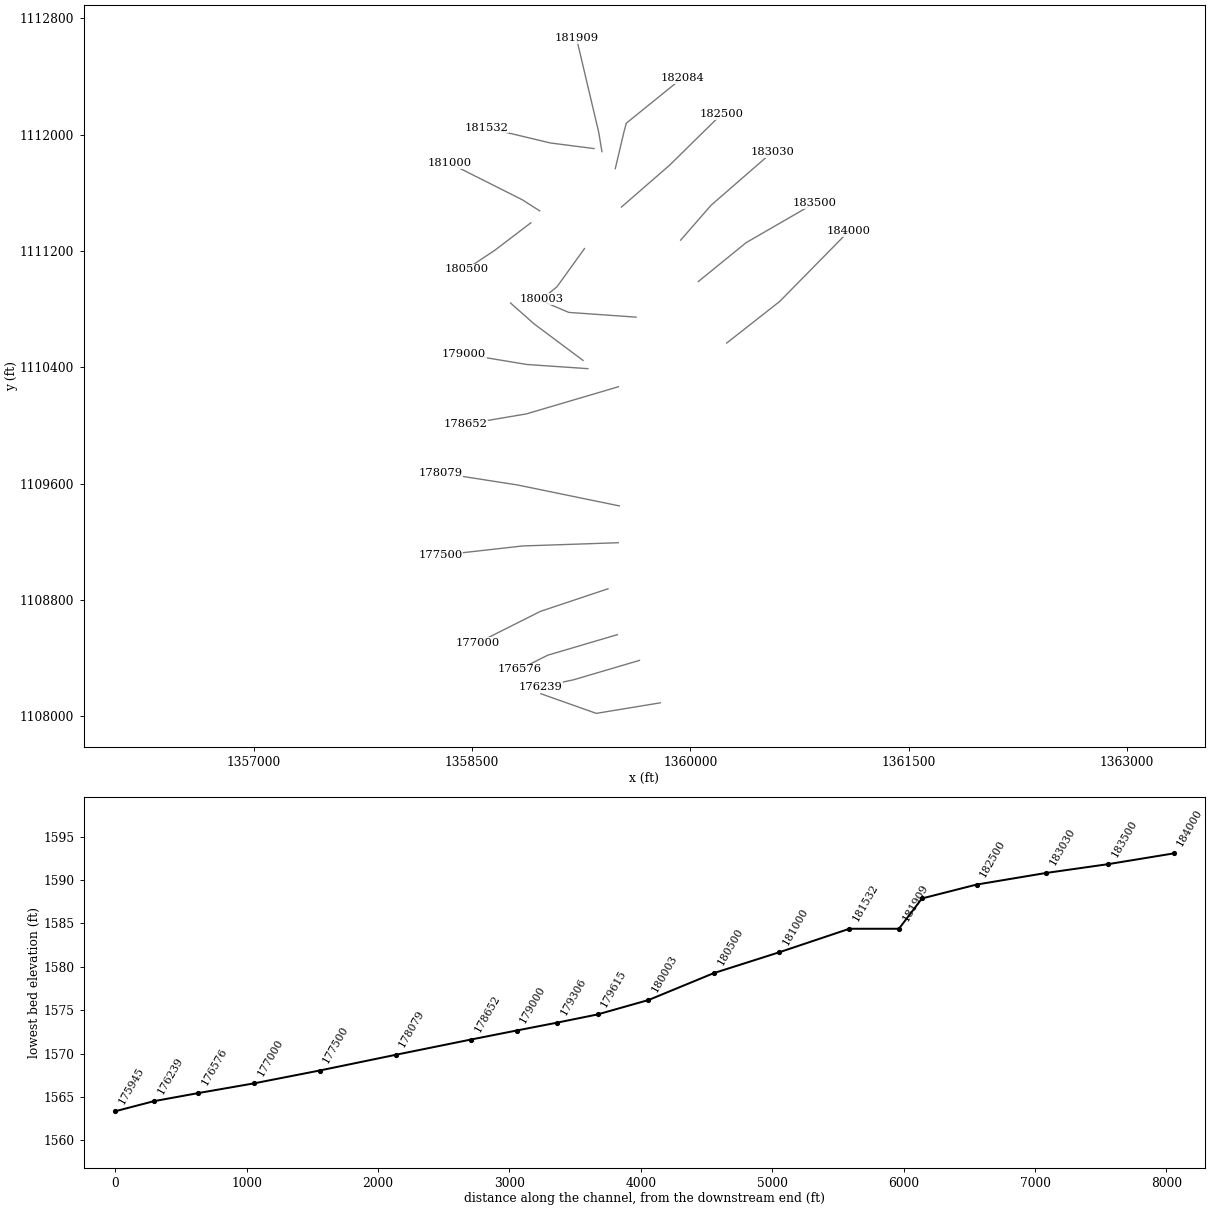
HEC-RAS study Chauga River.prj: Chauga River Limited Detail Study

--- Chauga River.g01 (geometry) --- (continued)

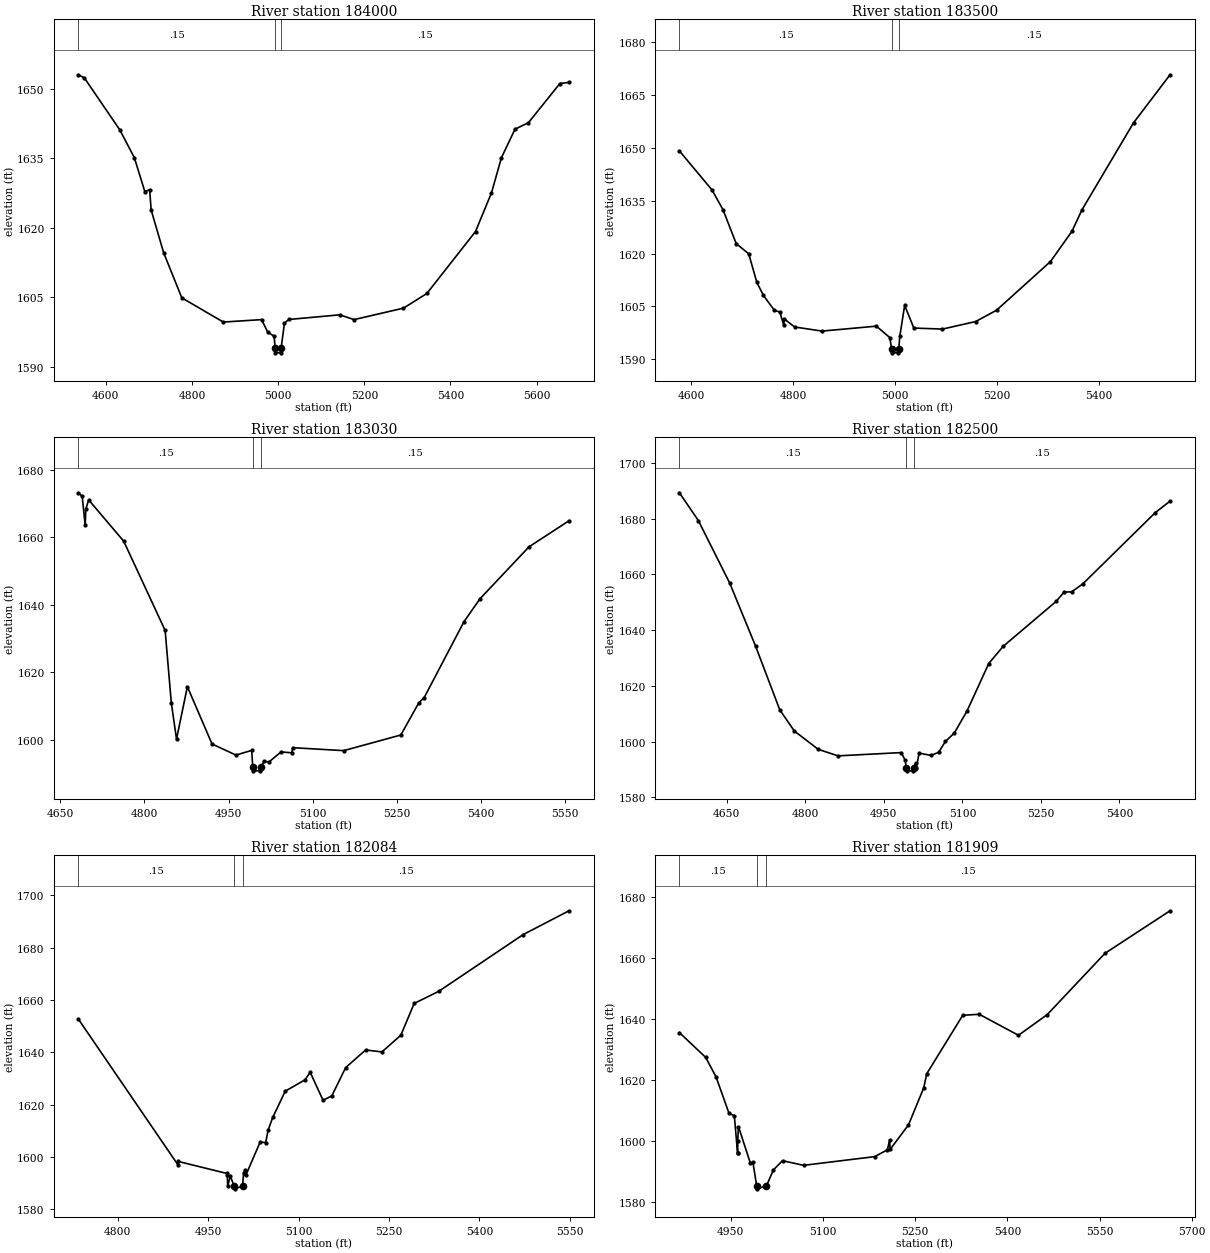
Type RM Length L Ch R = 1,184000,500,500,500
BEGIN DESCRIPTION:
Chauga River 368.0
END DESCRIPTION:
XS GIS Cut Line= 3
      1360248.50      1110567.35      1360613.12      1110853.83
      1361086.30      1111335.34
#Sta/Elev= 30
  4536.3 1652.97  4550.0 1652.32  4632.2 1641.13  4666.1 1635.14  4690.5 1627.81
  4701.7 1628.22  4705.2 1623.84  4734.2 1614.63  4776.4 1604.91  4872.7 1599.69
  4961.6 1600.22  4975.9 1597.50  4990.6 1596.64  4993.1 1594.06  4993.6 1593.06
  5006.4 1593.06  5006.9 1594.06  5014.6 1599.46  5024.8 1600.25  5143.2 1601.25
  5176.2 1600.22  5290.9 1602.69  5345.2 1605.85  5458.1 1619.20  5495.2 1627.53
  5518.2 1635.09  5549.8 1641.25  5580.9 1642.64  5654.0 1651.09  5675.1 1651.33
#Mann=3,-1,0
  4536.3    0.15       0  4993.1    0.05       0  5006.9    0.15       0
Bank Sta=4993.1,5006.9
XS Rating Curve= 0
Exp/Cntr=0.3,0.1

Type RM Length L Ch R = 1,183500,470,470,470
BEGIN DESCRIPTION:
Chauga River 367.0
END DESCRIPTION:
XS GIS Cut Line= 3
      1360054.19      1110990.81      1360382.63      1111258.17
      1360849.51      1111528.11
#Sta/Elev= 30
  4576.5 1649.11  4640.6 1638.00  4661.9 1632.46  4687.9 1622.83  4712.5 1619.91
  4728.4 1611.82  4741.2 1608.15  4762.8 1603.89  4773.6 1603.37  4781.0 1599.78
  4782.7 1601.38  4802.5 1599.16  4856.3 1597.99  4962.9 1599.39  4989.3 1596.16
  4993.1 1592.82  4993.6 1591.82  5006.4 1591.82  5006.9 1592.82  5008.9 1596.46
  5018.5 1605.29  5036.5 1598.85  5092.7 1598.56  5157.9 1600.70  5198.8 1603.91
  5304.6 1617.71  5346.8 1626.30  5366.4 1632.38  5467.6 1657.07  5539.3 1670.71
#Mann=3,-1,0
  4576.5    0.15       0  4993.1    0.05       0  5006.9    0.15       0
Bank Sta=4993.1,5006.9
XS Rating Curve= 0
Exp/Cntr=0.3,0.1

Type RM Length L Ch R = 1,183030,530,530,530
BEGIN DESCRIPTION:
Chauga River 366.0
END DESCRIPTION:
XS GIS Cut Line= 3
      1359932.75      1111275.24      1360141.22      1111514.98
      1360561.17      1111880.28
#Sta/Elev= 30
  4682.3 1673.13  4689.1 1672.05  4694.4 1663.49  4695.6 1668.31  4700.6 1671.03
  4763.0 1658.82  4836.9 1632.38  4847.9 1610.93  4857.2 1600.20  4876.5 1615.73
  4920.5 1598.75  4963.1 1595.48  4991.1 1596.86  4993.1 1591.81  4993.6 1590.81
  5006.4 1590.81  5006.9 1591.81  5013.2 1593.60  5022.1 1593.46  5043.5 1596.41
  5062.7 1596.15  5064.1 1597.67  5155.1 1596.79  5256.9 1601.42  5289.1 1610.98
  5298.6 1612.52  5369.4 1634.95  5398.0 1641.76  5485.5 1657.15  5556.6 1664.84
#Mann=3,-1,0
  4682.3    0.15       0  4993.1    0.05       0  5006.9    0.15       0
Bank Sta=4993.1,5006.9
XS Rating Curve= 0
Exp/Cntr=0.3,0.1

Type RM Length L Ch R = 1,182500,416,416,416
BEGIN DESCRIPTION:
Chauga River 365.0
END DESCRIPTION:
XS GIS Cut Line= 3
      1359525.96      1111502.91      1359858.08      1111792.13
      1360212.05      1112140.43
#Sta/Elev= 30
  4559.6 1689.29  4595.7 1679.33  4655.6 1656.89  4705.0 1634.26  4751.1 1611.43
  4778.9 1603.79  4824.7 1597.19  4862.4 1594.85  4983.2 1596.02  4990.5 1593.36
  4993.1 1590.47  4993.6 1589.47  5006.4 1589.47  5006.9 1590.47  5010.6 1592.23
  5012.0 1590.50  5017.4 1595.82  5040.2 1595.01  5054.8 1596.14  5067.6 1600.03
  5084.7 1603.07  5109.1 1611.04  5150.3 1627.97  5178.0 1634.18  5279.3 1650.33
  5294.3 1653.67  5308.5 1653.70  5329.8 1656.55  5468.1 1682.11  5496.6 1686.29
#Mann=3,-1,0
  4559.6    0.15       0  4993.1    0.05       0  5006.9    0.15       0
Bank Sta=4993.1,5006.9
XS Rating Curve= 0
Exp/Cntr=0.3,0.1

Type RM Length L Ch R = 1,182084,175,175,175
BEGIN DESCRIPTION:
Chauga River 364.5
END DESCRIPTION:
XS GIS Cut Line= 4
      1359483.49      1111767.08      1359544.57      1112025.36
      1359559.37      1112079.71      1359941.91      1112389.38
#Sta/Elev= 30
  4734.6 1652.73  4900.0 1596.96  4900.3 1598.34  4980.9 1593.75  4981.6 1593.33
  4982.3 1588.87  4986.6 1592.79  4993.1 1588.87  4993.6 1587.87  5006.9 1588.87
  5008.7 1593.92  5010.9 1594.95  5012.3 1593.04  5036.2 1605.77  5045.2 1605.52
  5049.5 1610.39  5057.0 1615.14  5077.8 1625.20  5110.3 1629.50  5119.2 1632.40
  5140.5 1621.71  5155.0 1623.39  5178.1 1634.24  5211.2 1640.94  5238.2 1640.20
  5269.5 1646.58  5291.7 1658.73  5332.2 1663.33  5472.4 1685.03  5548.5 1694.14
#Mann=3,-1,0
  4734.6    0.15       0  4993.1    0.05       0  5006.9    0.15       0
Bank Sta=4993.1,5006.9
XS Rating Curve= 0
Exp/Cntr=0.3,0.1

Type RM Length L Ch R = 1,181909,377,377,377
BEGIN DESCRIPTION:
Chauga River 364.0
END DESCRIPTION:
XS GIS Cut Line= 3
      1359391.68      1111884.17      1359369.98      1112016.09
      1359217.14      1112663.09
#Sta/Elev= 30
  4866.3 1635.58  4908.9 1627.48  4925.9 1621.07  4947.1 1609.07  4955.6 1608.37
  4961.0 1596.05  4961.1 1596.21  4961.2 1600.14  4962.4 1604.77  4981.7 1592.84
  4985.9 1593.10  4992.0 1585.38  4992.5 1584.38  5008.0 1585.38  5019.3 1590.61
  5034.1 1593.60  5068.4 1592.08  5184.2 1594.94  5204.9 1597.19  5208.3 1600.38
  5209.3 1597.33  5239.1 1605.33  5263.9 1617.47  5268.8 1622.09  5327.4 1641.25
  5354.3 1641.58  5418.1 1634.70  5465.0 1641.49  5559.0 1661.57  5664.8 1675.50
#Mann=3,-1,0
  4866.3    0.15       0  4992.0    0.05       0  5008.0    0.15       0
Bank Sta=4992,5008
XS Rating Curve= 0
Exp/Cntr=0.3,0.1

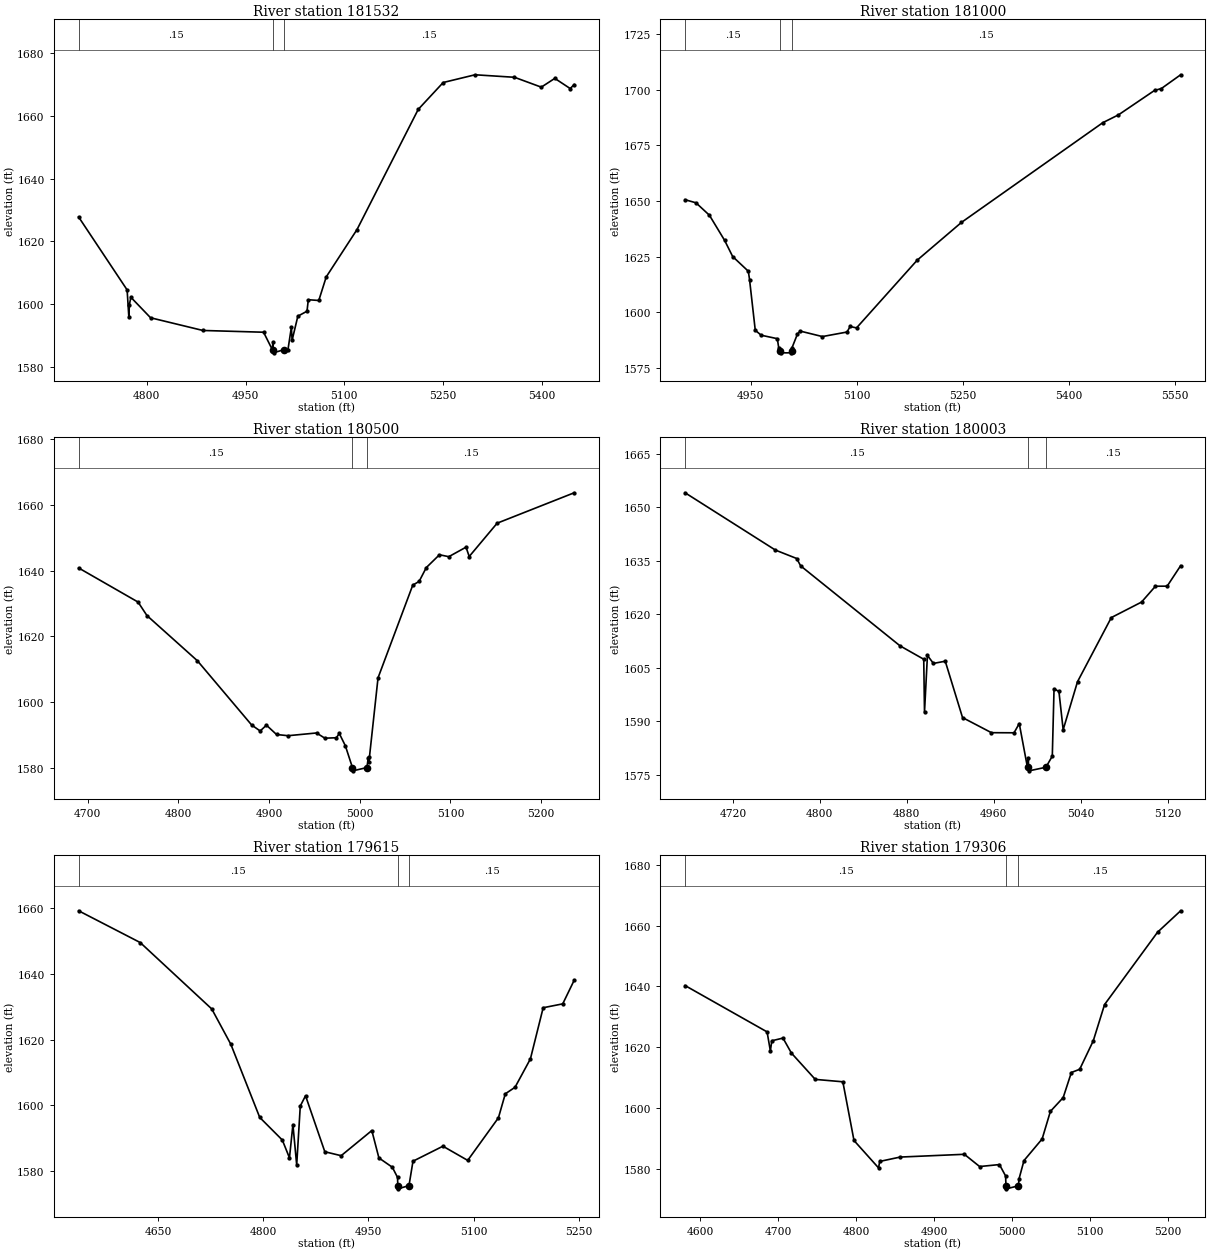
Type RM Length L Ch R = 1,181532,532,532,532
BEGIN DESCRIPTION:
Chauga River 363.0
END DESCRIPTION:
XS GIS Cut Line= 3
      1359336.97      1111904.98      1359036.17      1111943.83
      1358599.69      1112048.27
#Sta/Elev= 30
  4696.7 1627.73  4770.3 1604.46  4772.9 1595.83  4773.7 1599.77  4776.0 1602.11
  4805.9 1595.57  4885.3 1591.52  4977.4 1590.96  4990.7 1585.38  4991.5 1587.75
  4992.0 1585.38  4992.5 1584.38  5008.0 1585.38  5014.4 1585.38  5019.6 1592.57
  5020.7 1588.39  5029.4 1596.08  5043.3 1597.66  5045.3 1601.33  5061.2 1601.09
  5072.5 1608.62  5119.2 1623.72  5212.1 1662.07  5250.0 1670.65  5298.4 1673.12
  5358.2 1672.32  5398.9 1669.17  5419.4 1671.97  5442.8 1668.72  5448.8 1670.01
#Mann=3,-1,0
  4696.7    0.15       0  4992.0    0.05       0  5008.0    0.15       0
Bank Sta=4992,5008
XS Rating Curve= 0
Exp/Cntr=0.3,0.1

Type RM Length L Ch R = 1,181000,500,500,500
BEGIN DESCRIPTION:
Chauga River 362.0
END DESCRIPTION:
XS GIS Cut Line= 3
      1358964.40      1111476.50      1358844.05      1111553.36
      1358345.13      1111804.35
#Sta/Elev= 30
  4857.2 1650.53  4872.6 1649.15  4891.6 1643.56  4913.1 1632.27  4924.5 1625.00
  4946.7 1618.37  4948.4 1614.65  4956.5 1591.82  4964.9 1589.60  4987.7 1588.05
  4989.7 1583.95  4989.8 1582.94  4992.0 1582.68  4992.5 1581.68  5007.5 1581.68
  5008.0 1582.68  5008.5 1583.95  5016.2 1590.14  5020.2 1591.45  5051.5 1589.00
  5086.4 1591.04  5090.7 1593.53  5099.8 1592.89  5185.7 1623.36  5248.3 1640.33
  5448.4 1685.19  5470.5 1688.69  5521.6 1699.69  5531.2 1700.52  5558.5 1706.72
#Mann=3,-1,0
  4857.2    0.15       0  4992.0    0.05       0  5008.0    0.15       0
Bank Sta=4992,5008
XS Rating Curve= 0
Exp/Cntr=0.3,0.1

Type RM Length L Ch R = 1,180500,497,497,497
BEGIN DESCRIPTION:
Chauga River 361.0
END DESCRIPTION:
XS GIS Cut Line= 3
      1358903.66      1111394.56      1358657.31      1111206.71
      1358460.46      1111075.81
#Sta/Elev= 30
  4690.2 1640.77  4755.7 1630.43  4765.5 1626.34  4821.1 1612.64  4880.9 1593.17
  4890.3 1591.35  4897.2 1593.12  4908.3 1590.29  4921.0 1589.92  4952.4 1590.75
  4961.6 1589.17  4974.3 1589.30  4977.5 1590.60  4984.2 1586.86  4992.0 1580.27
  4992.5 1579.27  5008.0 1580.27  5009.3 1583.02  5009.9 1583.43  5010.2 1582.06
  5020.2 1607.45  5058.5 1635.57  5065.5 1636.69  5073.4 1640.88  5087.9 1644.77
  5098.2 1644.19  5117.2 1647.07  5120.7 1644.24  5151.5 1654.34  5236.4 1663.56
#Mann=3,-1,0
  4690.2    0.15       0  4992.0    0.05       0  5008.0    0.15       0
Bank Sta=4992,5008
XS Rating Curve= 0
Exp/Cntr=0.3,0.1

Type RM Length L Ch R = 1,180003,388,388,388
BEGIN DESCRIPTION:
Chauga River 360.0
END DESCRIPTION:
XS GIS Cut Line= 3
      1359271.88      1111217.26      1359082.65      1110954.26
      1358980.30      1110870.90
#Sta/Elev= 30
  4676.0 1654.01  4759.1 1637.97  4778.7 1635.61  4782.3 1633.56  4873.8 1611.16
  4895.6 1607.41  4896.3 1592.60  4899.0 1608.48  4904.5 1606.24  4915.4 1606.86
  4931.3 1591.08  4957.9 1586.85  4978.7 1586.82  4983.5 1589.41  4991.0 1577.19
  4991.4 1577.17  4991.9 1579.87  4992.0 1577.17  4992.5 1576.17  5008.0 1577.17
  5013.9 1580.28  5015.5 1599.11  5020.0 1598.40  5023.9 1587.68  5037.1 1601.12
  5068.2 1619.07  5096.0 1623.41  5108.8 1627.85  5119.6 1627.87  5132.0 1633.60
#Mann=3,-1,0
  4676.0    0.15       0  4992.0    0.05       0  5008.0    0.15       0
Bank Sta=4992,5008
XS Rating Curve= 0
Exp/Cntr=0.3,0.1

Type RM Length L Ch R = 1,179615,309,309,309
BEGIN DESCRIPTION:
Chauga River 359.5
END DESCRIPTION:
XS GIS Cut Line= 3
      1359626.17      1110745.83      1359164.31      1110778.40
      1358940.08      1110873.33
#Sta/Elev= 30
  4537.0 1659.23  4624.8 1649.55  4726.8 1629.32  4754.0 1618.55  4795.2 1596.27
  4827.4 1589.38  4837.6 1583.95  4842.5 1594.08  4847.9 1581.79  4853.0 1599.73
  4860.5 1602.88  4888.0 1585.81  4911.3 1584.61  4955.0 1592.27  4965.1 1583.93
  4984.3 1581.08  4991.7 1577.98  4992.0 1575.51  4992.5 1574.51  5008.0 1575.51
  5013.7 1582.93  5056.4 1587.50  5091.7 1583.18  5135.5 1596.15  5145.3 1603.46
  5159.2 1605.46  5181.1 1614.10  5199.3 1629.69  5227.2 1630.87  5243.5 1638.06
#Mann=3,-1,0
  4537.0    0.15       0  4992.0    0.05       0  5008.0    0.15       0
Bank Sta=4992,5008
XS Rating Curve= 0
Exp/Cntr=0.3,0.1

Type RM Length L Ch R = 1,179306,306,306,306
BEGIN DESCRIPTION:
Chauga River 359.0
END DESCRIPTION:
XS GIS Cut Line= 3
      1359261.87      1110448.33      1358925.65      1110699.55
      1358764.01      1110842.97
#Sta/Elev= 30
  4580.3 1640.29  4685.5 1625.08  4689.7 1618.84  4691.6 1622.17  4705.9 1623.05
  4716.7 1618.13  4747.3 1609.49  4782.7 1608.70  4797.0 1589.43  4828.5 1580.44
  4830.0 1582.56  4856.2 1583.99  4938.6 1584.90  4958.2 1580.88  4983.6 1581.53
  4991.5 1577.80  4992.0 1574.56  4992.5 1573.56  5008.0 1574.56  5008.7 1576.78
  5015.1 1582.84  5038.4 1589.94  5049.0 1598.99  5065.4 1603.52  5075.9 1611.75
  5086.6 1612.81  5104.0 1622.15  5118.5 1634.06  5186.5 1657.81  5216.1 1664.84
#Mann=3,-1,0
  4580.3    0.15       0  4992.0    0.05       0  5008.0    0.15       0
Bank Sta=4992,5008
XS Rating Curve= 0
Exp/Cntr=0.3,0.1

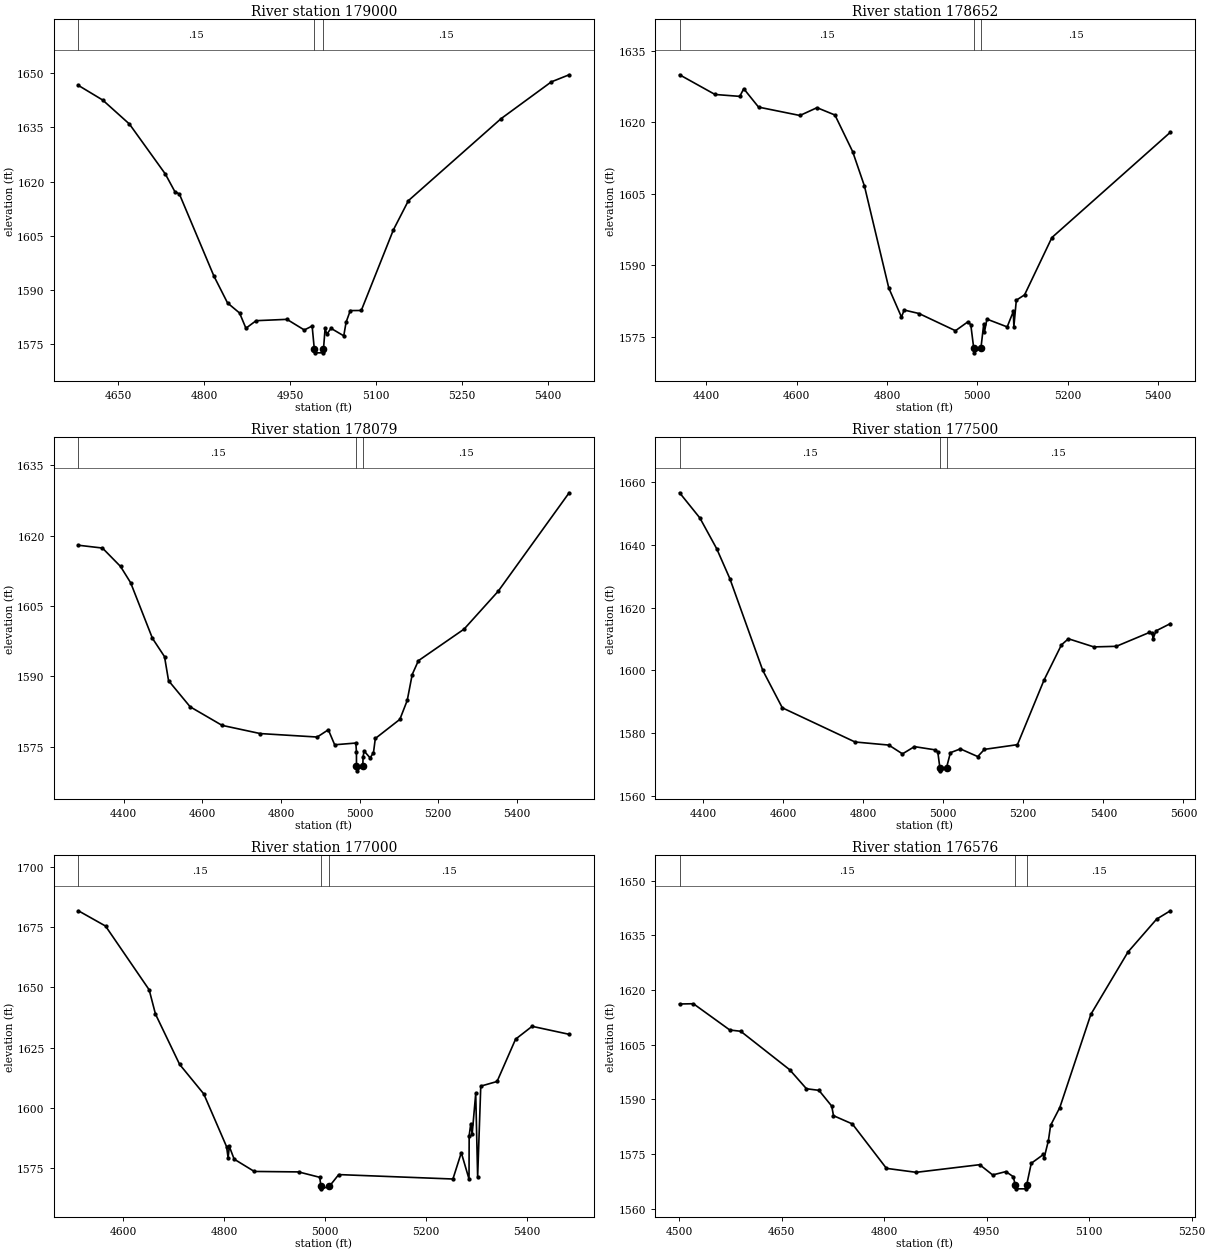
Type RM Length L Ch R = 1,179000,348,348,348
BEGIN DESCRIPTION:
Chauga River 358.0
END DESCRIPTION:
XS GIS Cut Line= 3
      1359295.22      1110391.56      1358876.30      1110420.28
      1358445.28      1110491.74
#Sta/Elev= 30
  4580.1 1646.59  4622.5 1642.55  4669.2 1635.91  4731.8 1622.12  4748.6 1617.21
  4756.4 1616.57  4816.6 1593.92  4840.5 1586.45  4861.5 1583.67  4872.6 1579.46
  4890.4 1581.55  4944.2 1581.92  4974.5 1578.98  4988.2 1580.07  4992.0 1573.66
  4992.5 1572.66  5007.5 1572.66  5008.0 1573.66  5010.8 1579.39  5013.8 1577.83
  5021.2 1579.43  5043.4 1577.36  5047.5 1581.14  5054.8 1584.34  5074.0 1584.37
  5130.1 1606.67  5156.3 1614.74  5317.8 1637.37  5405.8 1647.57  5436.9 1649.53
#Mann=3,-1,0
  4580.1    0.15       0  4992.0    0.05       0  5008.0    0.15       0
Bank Sta=4992,5008
XS Rating Curve= 0
Exp/Cntr=0.3,0.1

Type RM Length L Ch R = 1,178652,573,573,573
BEGIN DESCRIPTION:
Chauga River 357.0
END DESCRIPTION:
XS GIS Cut Line= 3
      1359504.75      1110267.10      1358872.63      1110080.45
      1358451.34      1110009.06
#Sta/Elev= 30
  4340.9 1629.94  4419.3 1625.81  4474.2 1625.41  4482.9 1627.02  4515.7 1623.16
  4607.3 1621.40  4645.1 1623.04  4684.8 1621.50  4724.0 1613.83  4750.1 1606.61
  4804.0 1585.22  4832.1 1579.12  4838.0 1580.60  4870.8 1579.87  4951.6 1576.26
  4978.6 1578.09  4985.5 1577.55  4992.0 1572.62  4992.5 1571.62  5008.0 1572.62
  5014.2 1577.70  5015.6 1575.89  5021.3 1578.69  5066.1 1577.06  5079.7 1580.30
  5080.9 1577.09  5086.3 1582.66  5104.6 1583.78  5165.1 1595.80  5427.3 1617.88
#Mann=3,-1,0
  4340.9    0.15       0  4992.0    0.05       0  5008.0    0.15       0
Bank Sta=4992,5008
XS Rating Curve= 0
Exp/Cntr=0.3,0.1

Type RM Length L Ch R = 1,178079,579,579,579
BEGIN DESCRIPTION:
Chauga River 356.0
END DESCRIPTION:
XS GIS Cut Line= 3
      1359511.53      1109447.81      1358811.00      1109591.92
      1358284.55      1109673.93
#Sta/Elev= 30
  4284.8 1617.98  4346.0 1617.38  4392.0 1613.45  4417.7 1609.98  4473.1 1598.13
  4503.8 1594.22  4514.1 1589.09  4569.0 1583.52  4650.2 1579.56  4747.2 1577.81
  4892.1 1577.07  4920.4 1578.62  4936.5 1575.42  4990.4 1575.79  4991.9 1573.86
  4992.0 1570.86  4992.5 1569.86  5008.0 1570.86  5008.8 1572.81  5011.2 1574.10
  5026.7 1572.62  5035.2 1573.74  5039.9 1576.76  5102.3 1580.84  5121.0 1584.87
  5133.7 1590.40  5149.4 1593.35  5265.6 1600.09  5352.4 1608.17  5532.8 1629.17
#Mann=3,-1,0
  4284.8    0.15       0  4992.0    0.05       0  5008.0    0.15       0
Bank Sta=4992,5008
XS Rating Curve= 0
Exp/Cntr=0.3,0.1

Type RM Length L Ch R = 1,177500,500,500,500
BEGIN DESCRIPTION:
Chauga River 355.0
END DESCRIPTION:
XS GIS Cut Line= 3
      1359503.75      1109194.60      1358845.73      1109172.23
      1358281.90      1109108.63
#Sta/Elev= 30
  4341.6 1656.52  4392.3 1648.50  4434.3 1638.72  4467.1 1629.22  4549.3 1600.03
  4598.2 1588.10  4779.8 1577.23  4864.2 1576.25  4898.3 1573.45  4928.2 1575.75
  4980.3 1574.72  4986.6 1574.02  4991.7 1569.05  4992.2 1568.05  5008.3 1569.05
  5018.1 1573.83  5042.9 1575.03  5086.3 1572.59  5103.0 1574.88  5185.5 1576.38
  5252.0 1596.96  5295.4 1608.13  5312.8 1610.07  5376.3 1607.48  5432.5 1607.67
  5515.3 1612.09  5522.5 1611.88  5524.1 1610.05  5531.7 1612.59  5567.4 1614.89
#Mann=3,-1,0
  4341.6    0.15       0  4991.7    0.05       0  5008.3    0.15       0
Bank Sta=4991.7,5008.3
XS Rating Curve= 0
Exp/Cntr=0.3,0.1

Type RM Length L Ch R = 1,177000,424,424,424
BEGIN DESCRIPTION:
Chauga River 354.0
END DESCRIPTION:
XS GIS Cut Line= 3
      1359433.33      1108877.80      1358969.51      1108722.59
      1358537.25      1108505.30
#Sta/Elev= 30
  4510.9 1681.70  4564.7 1675.38  4651.2 1648.98  4663.7 1638.93  4711.6 1618.09
  4759.4 1605.89  4804.7 1584.02  4807.7 1579.38  4810.1 1584.13  4819.7 1578.86
  4859.6 1573.77  4947.3 1573.58  4989.4 1571.34  4991.7 1567.57  4992.2 1566.57
  5008.3 1567.57  5027.0 1572.47  5253.4 1570.64  5270.0 1581.54  5285.3 1570.64
  5285.6 1588.59  5288.8 1593.54  5291.5 1589.16  5298.6 1606.06  5302.4 1571.47
  5308.6 1609.09  5340.9 1611.02  5377.6 1628.54  5410.4 1633.86  5483.8 1630.55
#Mann=3,-1,0
  4510.9    0.15       0  4991.7    0.05       0  5008.3    0.15       0
Bank Sta=4991.7,5008.3
XS Rating Curve= 0
Exp/Cntr=0.3,0.1

Type RM Length L Ch R = 1,176576,337,337,337
BEGIN DESCRIPTION:
Chauga River 353.0
END DESCRIPTION:
XS GIS Cut Line= 3
      1359498.48      1108562.58      1359019.24      1108421.05
      1358823.79      1108322.93
#Sta/Elev= 30
  4500.3 1616.18  4520.5 1616.25  4573.8 1609.04  4589.8 1608.69  4661.5 1598.13
  4686.0 1592.92  4704.3 1592.48  4723.0 1588.16  4725.6 1585.53  4753.2 1583.26
  4803.1 1571.07  4846.7 1569.98  4939.6 1572.08  4958.6 1569.26  4977.9 1570.18
  4988.8 1568.78  4991.7 1566.45  4992.2 1565.45  5007.8 1565.45  5008.3 1566.45
  5015.1 1572.46  5033.0 1574.89  5034.0 1573.97  5040.2 1578.69  5043.4 1582.86
  5056.9 1587.77  5102.4 1613.36  5156.7 1630.45  5198.6 1639.47  5218.7 1641.76
#Mann=3,-1,0
  4500.3    0.15       0  4991.7    0.05       0  5008.3    0.15       0
Bank Sta=4991.7,5008.3
XS Rating Curve= 0
Exp/Cntr=0.3,0.1

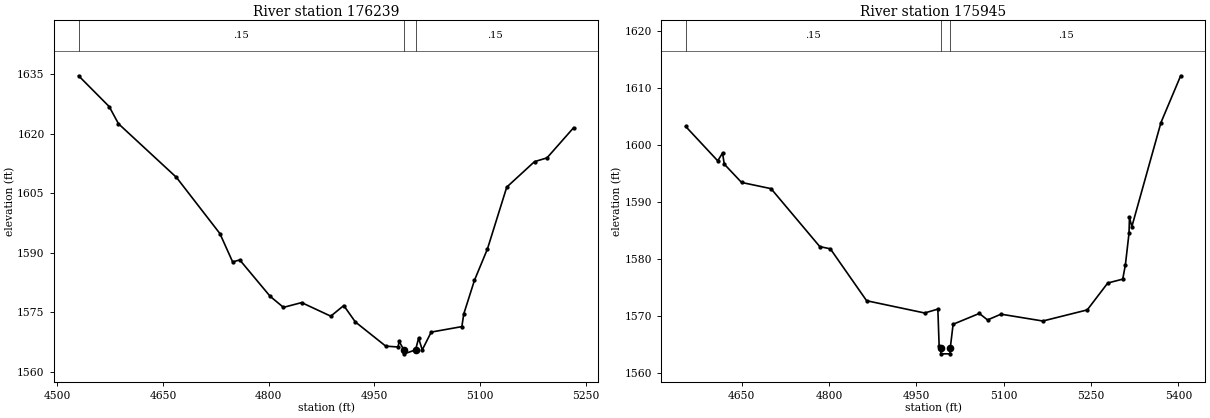
Type RM Length L Ch R = 1,176239,294,294,294
BEGIN DESCRIPTION:
Chauga River 352.5
END DESCRIPTION:
XS GIS Cut Line= 3
      1359649.63      1108385.45      1359198.91      1108252.58
      1358971.66      1108203.43
#Sta/Elev= 30
  4530.1 1634.58  4573.5 1626.82  4586.7 1622.49  4668.9 1608.99  4730.6 1594.83
  4748.7 1587.68  4758.8 1588.18  4801.9 1579.02  4820.8 1576.23  4846.6 1577.43
  4888.0 1574.01  4906.4 1576.69  4922.8 1572.56  4966.0 1566.46  4983.4 1566.25
  4985.0 1567.64  4991.7 1565.52  4992.2 1564.52  5008.3 1565.52  5012.6 1568.46
  5017.8 1565.52  5030.5 1570.00  5074.0 1571.38  5076.7 1574.57  5091.9 1583.06
  5110.3 1590.95  5137.7 1606.53  5177.1 1612.95  5194.8 1613.89  5232.5 1621.48
#Mann=3,-1,0
  4530.1    0.15       0  4991.7    0.05       0  5008.3    0.15       0
Bank Sta=4991.7,5008.3
XS Rating Curve= 0
Exp/Cntr=0.3,0.1

Type RM Length L Ch R = 1,175945,670,670,670
BEGIN DESCRIPTION:
Chauga River 352.0
END DESCRIPTION:
XS GIS Cut Line= 3
      1359792.85      1108093.66      1359352.90      1108021.08
      1358972.26      1108156.19
#Sta/Elev= 30
  4554.1 1603.26  4609.1 1597.23  4617.3 1598.60  4620.3 1596.65  4650.0 1593.44
  4700.6 1592.35  4784.3 1582.18  4802.4 1581.79  4864.7 1572.68  4964.3 1570.53
  4987.0 1571.21  4989.2 1564.76  4991.7 1564.36  4992.2 1563.36  5007.8 1563.36
  5008.3 1564.36  5013.2 1568.55  5058.2 1570.45  5072.3 1569.31  5095.4 1570.32
  5167.2 1569.12  5243.5 1571.07  5278.7 1575.79  5304.4 1576.47  5309.0 1578.98
  5315.2 1584.53  5316.0 1587.29  5320.1 1585.69  5370.1 1603.96  5403.9 1612.16
#Mann=3,-1,0
  4554.1    0.15       0  4991.7    0.05       0  5008.3    0.15       0
Bank Sta=4991.7,5008.3
XS Rating Curve= 0
Exp/Cntr=0.3,0.1