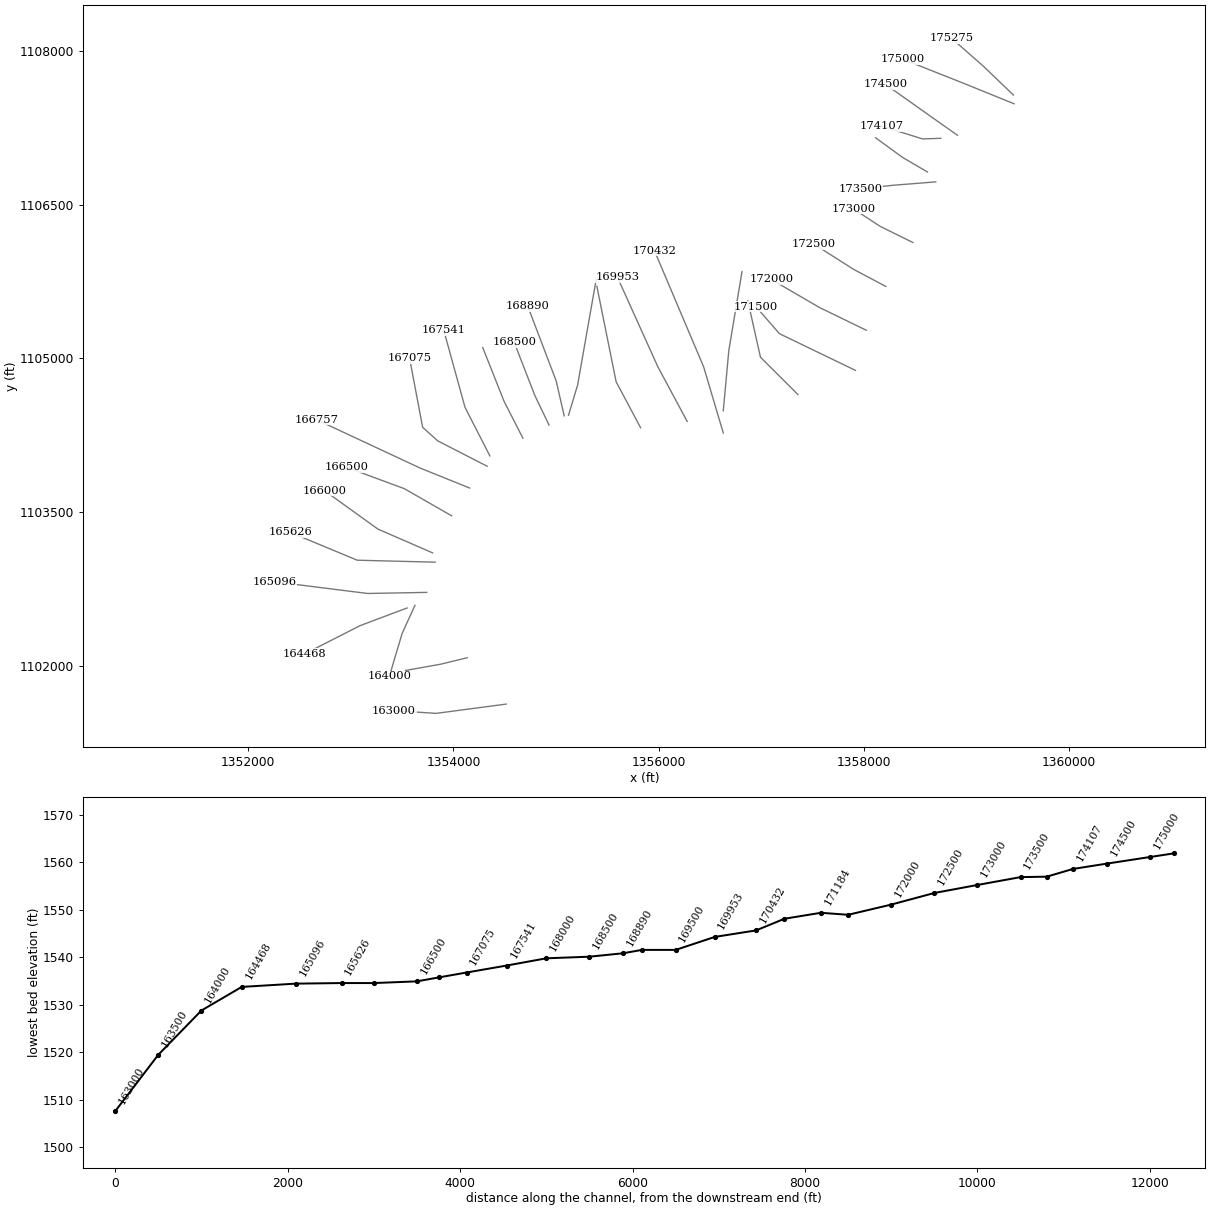
HEC-RAS study Chauga River.prj: Chauga River Limited Detail Study

--- Chauga River.g01 (geometry) --- (continued)

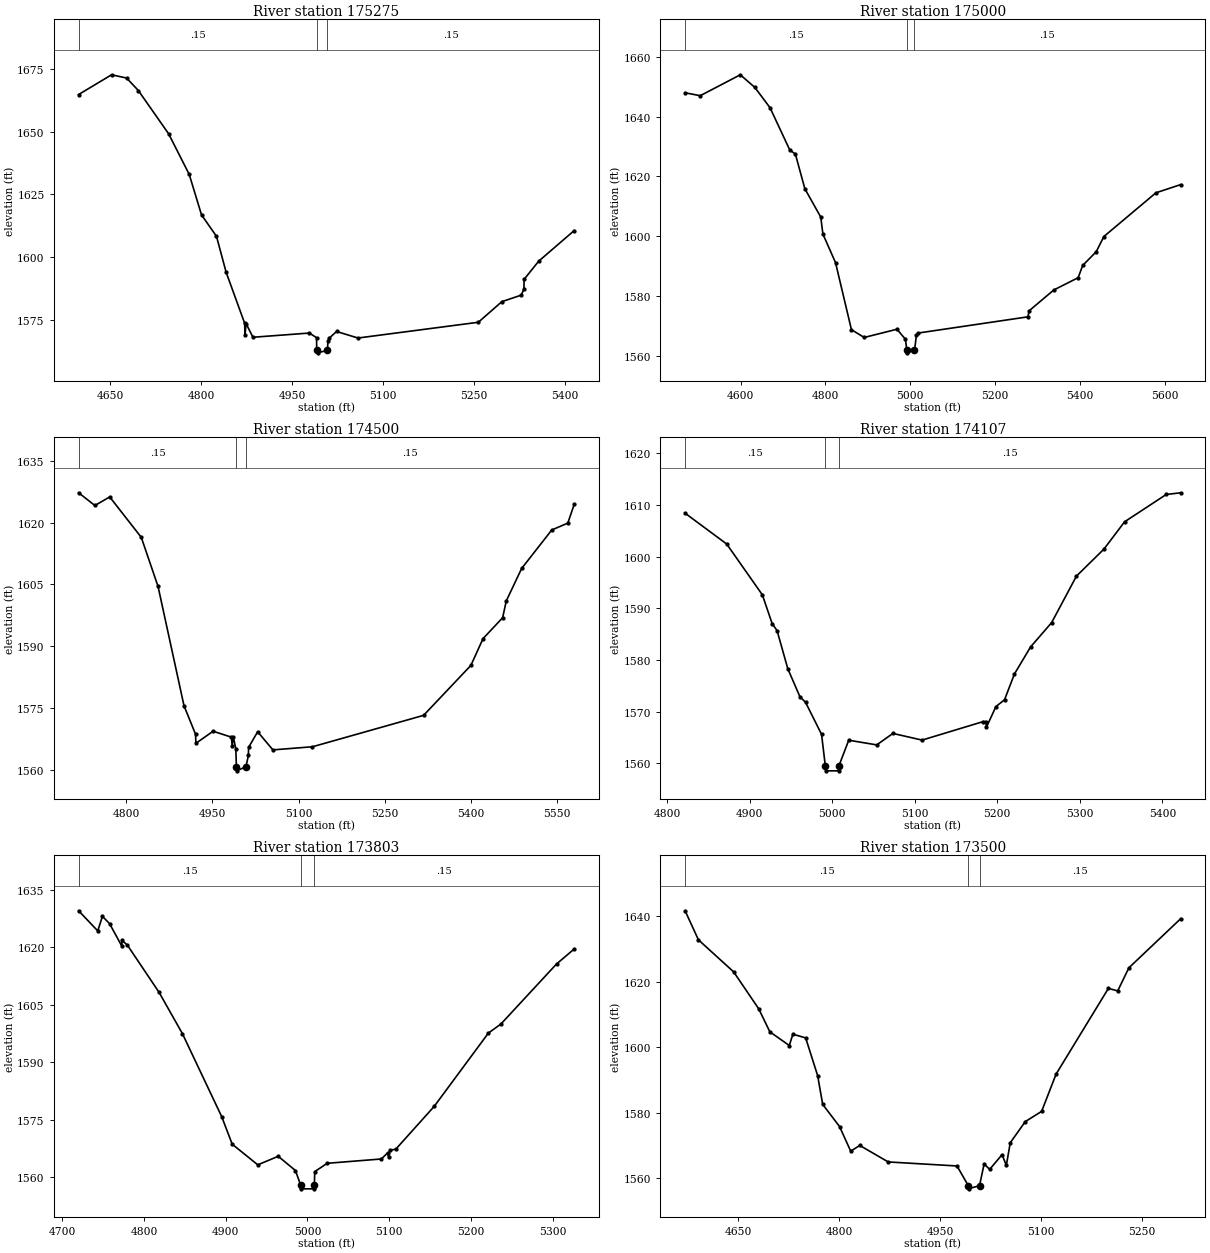
Type RM Length L Ch R = 1,175275,275,275,275
BEGIN DESCRIPTION:
Chauga River 351.0
END DESCRIPTION:
XS GIS Cut Line= 3
      1359459.44      1107567.41      1359169.59      1107845.82
      1358857.66      1108119.69
#Sta/Elev= 30
  4598.1 1664.81  4652.4 1672.68  4677.2 1671.38  4696.6 1666.39  4746.4 1649.18
  4780.4 1632.98  4800.7 1616.83  4825.4 1608.27  4841.3 1593.94  4871.8 1573.64
  4872.3 1568.94  4874.2 1573.47  4885.5 1568.04  4978.5 1569.72  4990.3 1567.87
  4990.7 1562.85  4991.7 1562.83  4992.2 1561.83  5008.3 1562.83  5009.2 1566.55
  5010.8 1567.57  5023.3 1570.34  5058.7 1567.74  5257.1 1574.02  5295.9 1582.24
  5327.9 1584.84  5332.3 1587.30  5332.5 1591.12  5356.6 1598.37  5415.1 1610.57
#Mann=3,-1,0
  4598.1    0.15       0  4991.7    0.05       0  5008.3    0.15       0
Bank Sta=4991.7,5008.3
XS Rating Curve= 0
Exp/Cntr=0.3,0.1

Type RM Length L Ch R = 1,175000,500,500,500
BEGIN DESCRIPTION:
Chauga River 350.0
END DESCRIPTION:
XS GIS Cut Line= 3
      1359466.51      1107481.84      1358974.84      1107681.33
      1358382.73      1107915.95
#Sta/Elev= 30
  4469.4 1647.96  4505.1 1646.99  4599.5 1653.98  4633.8 1649.74  4669.5 1642.97
  4716.2 1628.80  4729.2 1627.51  4751.6 1615.88  4789.0 1606.44  4794.1 1600.74
  4823.8 1591.22  4861.3 1568.81  4891.3 1566.21  4968.5 1568.95  4988.5 1565.63
  4991.7 1562.07  4992.2 1561.07  5008.3 1562.07  5010.1 1562.07  5014.3 1566.87
  5018.3 1567.68  5277.1 1573.10  5280.0 1575.13  5337.9 1582.06  5395.4 1586.18
  5406.2 1590.28  5438.1 1594.87  5456.1 1599.94  5578.6 1614.54  5636.9 1617.28
#Mann=3,-1,0
  4469.4    0.15       0  4991.7    0.05       0  5008.3    0.15       0
Bank Sta=4991.7,5008.3
XS Rating Curve= 0
Exp/Cntr=0.3,0.1

Type RM Length L Ch R = 1,174500,393,393,393
BEGIN DESCRIPTION:
Chauga River 349.0
END DESCRIPTION:
XS GIS Cut Line= 3
      1358913.99      1107175.24      1358682.76      1107338.24
      1358209.69      1107673.11
#Sta/Elev= 30
  4717.1 1627.24  4745.4 1624.15  4771.2 1626.23  4826.1 1616.42  4855.3 1604.49
  4900.5 1575.50  4920.6 1568.57  4921.2 1566.37  4951.2 1569.30  4983.1 1567.86
  4984.3 1565.78  4986.3 1567.96  4990.7 1565.00  4991.7 1560.68  4992.2 1559.68
  5008.3 1560.68  5012.6 1563.44  5012.9 1565.38  5028.7 1569.18  5055.2 1564.77
  5124.1 1565.53  5317.5 1573.16  5399.9 1585.31  5421.0 1591.81  5455.1 1596.88
  5461.4 1600.96  5488.2 1608.86  5540.6 1618.20  5568.5 1619.87  5579.6 1624.40
#Mann=3,-1,0
  4717.1    0.15       0  4991.7    0.05       0  5008.3    0.15       0
Bank Sta=4991.7,5008.3
XS Rating Curve= 0
Exp/Cntr=0.3,0.1

Type RM Length L Ch R = 1,174107,304,304,304
BEGIN DESCRIPTION:
Chauga River 348.5
END DESCRIPTION:
XS GIS Cut Line= 3
      1358752.11      1107145.40      1358574.11      1107139.38
      1358171.21      1107265.23
#Sta/Elev= 30
  4821.9 1608.43  4872.3 1602.46  4915.5 1592.62  4927.3 1587.07  4933.3 1585.70
  4946.3 1578.32  4960.9 1572.93  4967.8 1571.82  4987.2 1565.61  4991.7 1559.56
  4992.2 1558.56  5007.8 1558.56  5008.3 1559.56  5020.1 1564.49  5054.0 1563.58
  5073.6 1565.80  5108.9 1564.51  5183.1 1568.10  5186.4 1568.08  5186.8 1566.98
  5198.4 1571.00  5208.8 1572.32  5220.8 1577.31  5240.3 1582.53  5265.9 1587.26
  5295.9 1596.25  5329.2 1601.48  5354.2 1606.76  5404.6 1612.05  5422.1 1612.38
#Mann=3,-1,0
  4821.9    0.15       0  4991.7    0.05       0  5008.3    0.15       0
Bank Sta=4991.7,5008.3
XS Rating Curve= 0
Exp/Cntr=0.3,0.1

Type RM Length L Ch R = 1,173803,303,303,303
BEGIN DESCRIPTION:
Chauga River 348.0
END DESCRIPTION:
XS GIS Cut Line= 3
      1358621.90      1106817.13      1358380.14      1106958.39
      1358116.47      1107150.61
#Sta/Elev= 30
  4720.0 1629.56  4743.4 1624.30  4749.1 1628.11  4757.9 1626.19  4772.9 1620.30
  4773.1 1621.84  4779.7 1620.57  4818.5 1608.23  4846.9 1597.50  4895.0 1575.81
  4907.9 1568.59  4939.2 1563.20  4964.2 1565.43  4985.3 1561.71  4991.6 1557.93
  4992.1 1556.93  5007.9 1556.93  5008.4 1557.93  5008.9 1561.43  5024.1 1563.60
  5090.4 1564.73  5098.0 1566.32  5099.3 1565.15  5100.6 1566.99  5108.1 1567.30
  5155.0 1578.46  5221.4 1597.63  5236.6 1599.96  5304.7 1615.66  5326.3 1619.57
#Mann=3,-1,0
  4720.0    0.15       0  4991.6    0.05       0  5008.4    0.15       0
Bank Sta=4991.6,5008.4
XS Rating Curve= 0
Exp/Cntr=0.3,0.1

Type RM Length L Ch R = 1,173500,500,500,500
BEGIN DESCRIPTION:
Chauga River 347.0
END DESCRIPTION:
XS GIS Cut Line= 3
      1358702.67      1106720.76      1358275.02      1106686.82
      1357969.91      1106651.89
#Sta/Elev= 30
  4571.0 1641.70  4590.8 1632.83  4643.1 1623.06  4680.4 1611.77  4696.9 1604.76
  4725.8 1600.58  4731.1 1604.04  4750.1 1602.90  4767.9 1591.38  4775.4 1582.61
  4800.4 1575.86  4817.0 1568.34  4830.5 1570.08  4872.7 1565.05  4974.9 1563.82
  4991.6 1557.84  4992.1 1556.84  5008.4 1557.84  5015.2 1564.46  5023.4 1562.77
  5041.8 1567.27  5048.2 1564.01  5054.0 1570.90  5076.3 1577.36  5100.6 1580.48
  5122.1 1591.86  5199.8 1618.02  5213.6 1617.24  5230.2 1624.29  5307.1 1639.27
#Mann=3,-1,0
  4571.0    0.15       0  4991.6    0.05       0  5008.4    0.15       0
Bank Sta=4991.6,5008.4
XS Rating Curve= 0
Exp/Cntr=0.3,0.1

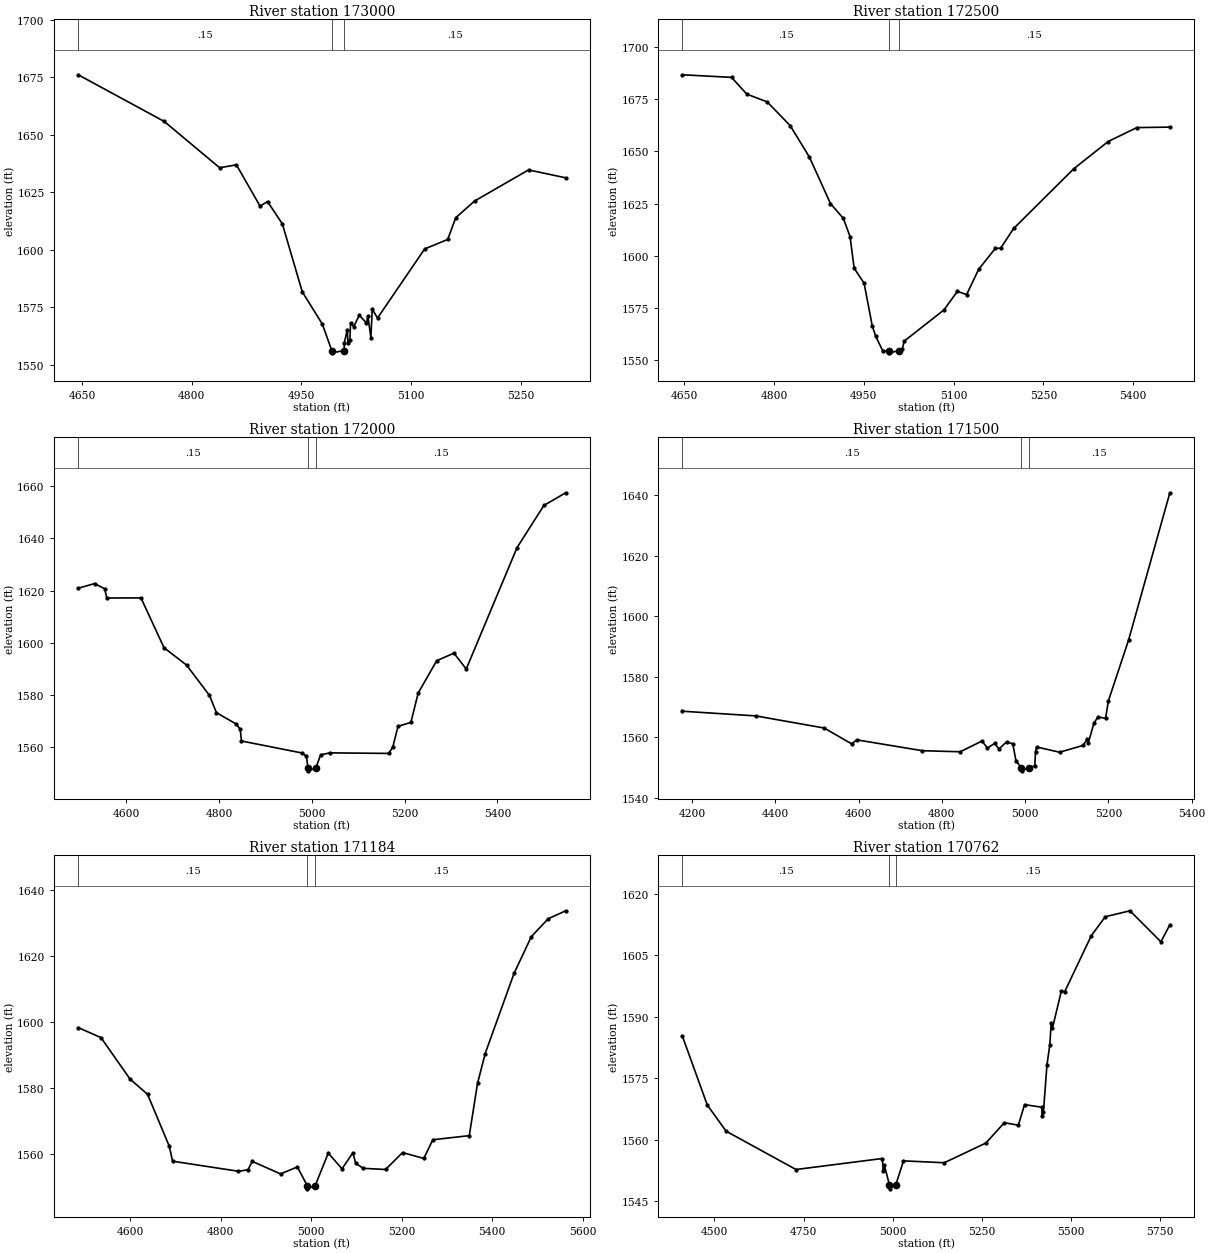
Type RM Length L Ch R = 1,173000,500,500,500
BEGIN DESCRIPTION:
Chauga River 346.0
END DESCRIPTION:
XS GIS Cut Line= 3
      1358479.83      1106129.77      1358161.01      1106287.04
      1357900.02      1106457.63
#Sta/Elev= 30
  4644.5 1676.07  4762.2 1655.79  4838.1 1635.65  4861.0 1636.93  4893.4 1618.97
  4903.6 1620.96  4923.9 1611.27  4951.2 1581.70  4978.6 1567.71  4991.6 1556.19
  4992.1 1555.19  5008.4 1556.19  5008.8 1559.59  5012.8 1565.28  5013.7 1559.49
  5016.4 1560.95  5017.3 1568.22  5021.8 1566.63  5029.2 1571.58  5039.0 1568.14
  5041.0 1571.17  5045.1 1561.85  5047.0 1574.19  5054.2 1570.31  5118.7 1600.35
  5150.2 1604.47  5161.3 1613.94  5187.1 1621.19  5260.9 1634.71  5311.8 1631.28
#Mann=3,-1,0
  4644.5    0.15       0  4991.6    0.05       0  5008.4    0.15       0
Bank Sta=4991.6,5008.4
XS Rating Curve= 0
Exp/Cntr=0.3,0.1

Type RM Length L Ch R = 1,172500,500,500,500
BEGIN DESCRIPTION:
Chauga River 345.0
END DESCRIPTION:
XS GIS Cut Line= 3
      1358215.79      1105701.71      1357903.74      1105867.16
      1357514.52      1106114.58
#Sta/Elev= 30
  4646.8 1686.69  4729.0 1685.45  4754.4 1677.41  4788.4 1673.72  4826.8 1662.38
  4859.0 1647.27  4894.2 1625.02  4915.8 1617.85  4926.9 1609.22  4933.8 1594.01
  4950.4 1586.85  4963.9 1566.57  4969.6 1561.55  4981.5 1554.50  4991.6 1554.50
  4992.1 1553.50  5008.4 1554.50  5014.2 1555.40  5017.5 1559.14  5083.7 1574.03
  5106.2 1582.93  5121.7 1581.42  5141.8 1593.50  5169.6 1603.54  5178.4 1603.61
  5200.3 1613.09  5300.8 1641.70  5358.2 1654.73  5406.0 1661.39  5461.2 1661.62
#Mann=3,-1,0
  4646.8    0.15       0  4991.6    0.05       0  5008.4    0.15       0
Bank Sta=4991.6,5008.4
XS Rating Curve= 0
Exp/Cntr=0.3,0.1

Type RM Length L Ch R = 1,172000,500,500,500
BEGIN DESCRIPTION:
Chauga River 344.0
END DESCRIPTION:
XS GIS Cut Line= 3
      1358025.02      1105274.99      1357571.81      1105495.03
      1357098.62      1105770.03
#Sta/Elev= 30
  4496.2 1620.91  4531.5 1622.71  4553.1 1620.71  4557.9 1617.18  4631.5 1617.21
  4681.2 1598.15  4729.8 1591.51  4779.2 1579.91  4794.2 1573.32  4837.1 1568.93
  4845.4 1566.96  4848.2 1562.47  4979.6 1557.86  4988.2 1556.58  4991.6 1552.06
  4992.1 1551.06  5008.4 1552.06  5018.9 1557.18  5039.2 1557.94  5166.0 1557.72
  5174.7 1560.31  5185.7 1568.08  5213.5 1569.60  5229.2 1580.81  5269.1 1593.19
  5306.4 1596.08  5332.8 1590.01  5442.4 1636.47  5500.3 1652.59  5547.3 1657.43
#Mann=3,-1,0
  4496.2    0.15       0  4991.6    0.05       0  5008.4    0.15       0
Bank Sta=4991.6,5008.4
XS Rating Curve= 0
Exp/Cntr=0.3,0.1

Type RM Length L Ch R = 1,171500,316,316,316
BEGIN DESCRIPTION:
Chauga River 343.0
END DESCRIPTION:
XS GIS Cut Line= 3
      1357919.79      1104883.62      1357178.73      1105241.38
      1356950.71      1105503.61
#Sta/Elev= 30
  4177.1 1568.61  4353.3 1567.06  4517.4 1563.06  4583.4 1557.83  4596.2 1559.14
  4753.4 1555.56  4844.3 1555.21  4896.4 1558.76  4909.5 1556.44  4926.5 1557.95
  4937.3 1556.15  4955.3 1558.47  4970.4 1557.85  4978.0 1552.26  4991.1 1549.91
  4991.6 1548.91  5008.9 1549.91  5023.2 1550.54  5025.0 1555.23  5027.5 1556.80
  5082.6 1555.06  5139.2 1557.30  5149.5 1559.49  5151.7 1558.12  5165.3 1564.73
  5175.0 1566.71  5193.1 1566.25  5200.0 1572.07  5248.3 1592.08  5347.5 1640.78
#Mann=3,-1,0
  4177.1    0.15       0  4991.1    0.05       0  5008.9    0.15       0
Bank Sta=4991.1,5008.9
XS Rating Curve= 0
Exp/Cntr=0.3,0.1

Type RM Length L Ch R = 1,171184,422,422,422
BEGIN DESCRIPTION:
Chauga River 342.5
END DESCRIPTION:
XS GIS Cut Line= 3
      1357357.83      1104649.19      1356993.45      1105012.43
      1356870.70      1105560.96
#Sta/Elev= 30
  4485.5 1598.25  4535.7 1595.22  4599.9 1582.63  4638.7 1578.00  4686.8 1562.18
  4693.8 1557.72  4839.3 1554.66  4860.3 1555.10  4869.9 1557.65  4932.5 1553.86
  4969.5 1555.98  4991.1 1550.33  4991.6 1549.33  5008.9 1550.33  5037.7 1560.17
  5068.1 1555.42  5092.1 1560.26  5098.2 1557.09  5115.1 1555.55  5164.2 1555.20
  5201.7 1560.33  5248.6 1558.56  5268.7 1564.22  5349.1 1565.47  5367.4 1581.34
  5384.3 1590.39  5448.0 1614.69  5486.2 1625.85  5523.5 1631.28  5562.1 1633.69
#Mann=3,-1,0
  4485.5    0.15       0  4991.1    0.05       0  5008.9    0.15       0
Bank Sta=4991.1,5008.9
XS Rating Curve= 0
Exp/Cntr=0.3,0.1

Type RM Length L Ch R = 1,170762,330,330,330
BEGIN DESCRIPTION:
Chauga River 342.0
END DESCRIPTION:
XS GIS Cut Line= 3
      1356631.03      1104490.25      1356685.15      1105077.66
      1356813.39      1105844.92
#Sta/Elev= 30
  4410.1 1585.30  4479.9 1568.52  4532.8 1562.13  4728.9 1552.79  4970.9 1555.47
  4974.0 1552.35  4976.5 1553.89  4991.1 1549.08  4991.6 1548.08  5008.9 1549.08
  5030.5 1554.90  5144.9 1554.44  5261.6 1559.24  5313.5 1564.20  5352.8 1563.59
  5370.2 1568.60  5418.5 1567.98  5419.7 1565.91  5423.2 1566.87  5433.0 1578.24
  5441.0 1583.11  5445.0 1588.49  5448.6 1587.29  5473.4 1596.28  5483.1 1596.16
  5557.4 1609.77  5596.7 1614.40  5666.0 1615.85  5752.8 1608.29  5777.9 1612.44
#Mann=3,-1,0
  4410.1    0.15       0  4991.1    0.05       0  5008.9    0.15       0
Bank Sta=4991.1,5008.9
XS Rating Curve= 0
Exp/Cntr=0.3,0.1

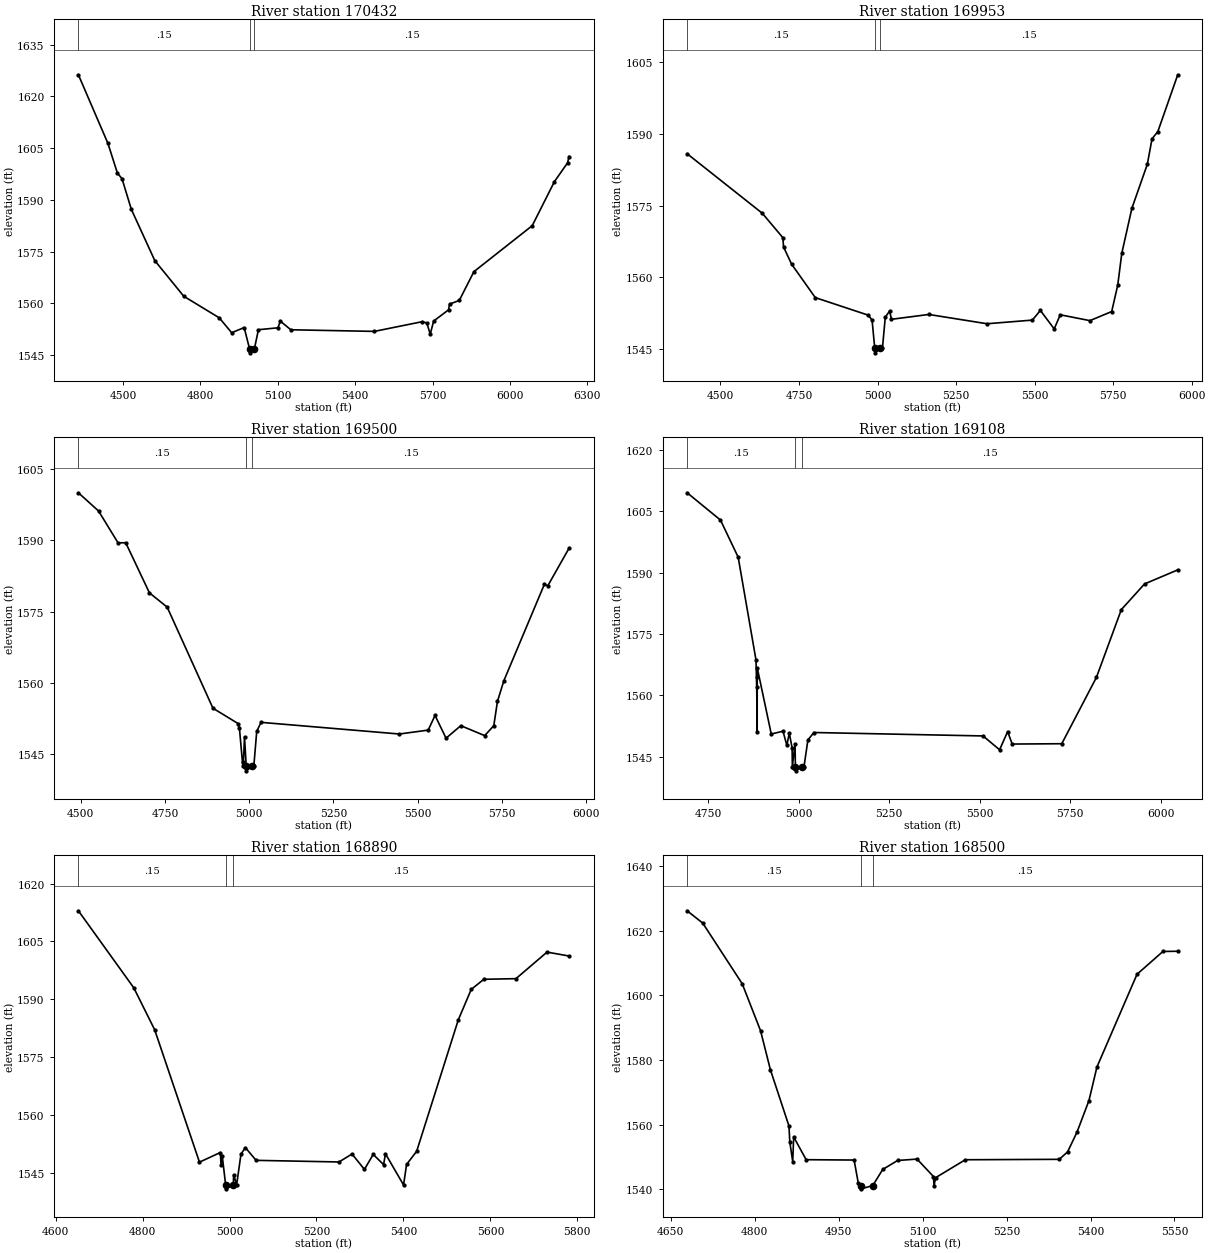
Type RM Length L Ch R = 1,170432,479,479,479
BEGIN DESCRIPTION:
Chauga River 341.0
END DESCRIPTION:
XS GIS Cut Line= 3
      1356631.13      1104273.46      1356439.70      1104918.35
      1355960.25      1106049.32
#Sta/Elev= 30
  4327.3 1626.26  4441.9 1606.34  4478.7 1597.70  4496.2 1596.16  4532.5 1587.23
  4623.6 1572.34  4735.7 1562.03  4873.1 1555.78  4921.3 1551.46  4969.7 1552.95
  4991.1 1546.62  4991.6 1545.62  5008.9 1546.62  5024.9 1552.33  5100.6 1552.88
  5109.9 1554.82  5150.5 1552.31  5474.1 1551.84  5659.9 1554.66  5677.5 1554.27
  5690.8 1551.02  5703.9 1554.84  5761.5 1558.08  5765.5 1559.75  5803.3 1560.82
  5859.9 1569.16  6086.0 1582.50  6172.0 1595.28  6223.0 1600.74  6228.4 1602.55
#Mann=3,-1,0
  4327.3    0.15       0  4991.1    0.05       0  5008.9    0.15       0
Bank Sta=4991.1,5008.9
XS Rating Curve= 0
Exp/Cntr=0.3,0.1

Type RM Length L Ch R = 1,169953,453,453,453
BEGIN DESCRIPTION:
Chauga River 340.0
END DESCRIPTION:
XS GIS Cut Line= 3
      1356278.99      1104386.38      1355992.43      1104920.46
      1355599.02      1105791.54
#Sta/Elev= 30
  4393.9 1585.86  4633.3 1573.41  4698.6 1568.32  4700.9 1566.37  4726.3 1562.80
  4801.9 1555.79  4971.1 1552.11  4982.7 1551.06  4991.1 1545.25  4991.6 1544.25
  5008.9 1545.25  5015.8 1545.32  5024.7 1551.71  5038.5 1552.98  5044.4 1551.26
  5163.4 1552.27  5348.6 1550.33  5492.9 1551.09  5518.5 1553.11  5562.5 1549.25
  5581.7 1552.20  5676.2 1550.98  5745.5 1552.88  5764.7 1558.38  5777.7 1565.06
  5809.8 1574.46  5859.0 1583.67  5873.9 1588.97  5892.4 1590.49  5955.8 1602.36
#Mann=3,-1,0
  4393.9    0.15       0  4991.1    0.05       0  5008.9    0.15       0
Bank Sta=4991.1,5008.9
XS Rating Curve= 0
Exp/Cntr=0.3,0.1

Type RM Length L Ch R = 1,169500,392,392,392
BEGIN DESCRIPTION:
Chauga River 339.0
END DESCRIPTION:
XS GIS Cut Line= 3
      1355825.01      1104324.98      1355586.46      1104772.69
      1355398.65      1105703.53
#Sta/Elev= 30
  4492.7 1599.95  4552.5 1596.13  4610.5 1589.43  4633.3 1589.45  4703.6 1578.93
  4756.4 1575.92  4892.3 1554.68  4966.8 1551.46  4970.9 1550.49  4981.0 1542.52
  4982.9 1543.41  4986.0 1548.68  4991.1 1542.52  4991.6 1541.52  5008.9 1542.52
  5013.7 1542.52  5022.3 1549.82  5035.2 1551.71  5445.9 1549.26  5531.5 1550.08
  5551.8 1553.16  5584.5 1548.38  5628.4 1551.01  5699.3 1548.92  5726.3 1551.01
  5737.2 1556.13  5756.4 1560.49  5876.3 1580.68  5886.8 1580.42  5949.6 1588.28
#Mann=3,-1,0
  4492.7    0.15       0  4991.1    0.05       0  5008.9    0.15       0
Bank Sta=4991.1,5008.9
XS Rating Curve= 0
Exp/Cntr=0.3,0.1

Type RM Length L Ch R = 1,169108,218,218,218
BEGIN DESCRIPTION:
Chauga River 338.5
END DESCRIPTION:
XS GIS Cut Line= 3
      1355122.42      1104446.81      1355211.11      1104741.76
      1355392.57      1105773.32
#Sta/Elev= 30
  4692.0 1609.50  4784.1 1602.83  4833.0 1593.75  4882.2 1568.64  4884.2 1561.92
  4885.5 1551.12  4885.6 1564.57  4885.7 1566.71  4924.4 1550.52  4956.8 1551.21
  4967.5 1547.74  4974.2 1550.77  4982.0 1547.11  4982.7 1542.52  4990.1 1548.17
  4991.1 1542.52  4991.6 1541.52  5008.9 1542.52  5014.8 1542.52  5025.7 1549.09
  5042.3 1550.89  5509.5 1550.05  5555.2 1546.67  5577.5 1551.12  5590.0 1548.07
  5727.0 1548.15  5822.7 1564.36  5891.5 1580.93  5955.6 1587.21  6047.4 1590.65
#Mann=3,-1,0
  4692.0    0.15       0  4991.1    0.05       0  5008.9    0.15       0
Bank Sta=4991.1,5008.9
XS Rating Curve= 0
Exp/Cntr=0.3,0.1

Type RM Length L Ch R = 1,168890,390,390,390
BEGIN DESCRIPTION:
Chauga River 338.0
END DESCRIPTION:
XS GIS Cut Line= 3
      1355079.90      1104440.68      1355002.37      1104779.53
      1354724.71      1105509.29
#Sta/Elev= 30
  4652.4 1612.94  4779.8 1592.96  4827.8 1582.09  4930.9 1547.73  4978.8 1550.23
  4980.6 1547.03  4983.4 1549.23  4991.1 1541.81  4991.6 1540.81  5008.9 1541.81
  5009.4 1544.47  5016.5 1541.93  5026.3 1549.78  5036.4 1551.52  5061.1 1548.20
  5251.9 1547.78  5281.8 1549.85  5310.3 1545.85  5330.5 1549.74  5354.4 1547.09
  5358.7 1549.90  5400.3 1541.81  5407.2 1547.13  5430.4 1550.54  5526.1 1584.61
  5555.9 1592.54  5585.0 1595.17  5658.8 1595.33  5730.3 1602.22  5780.8 1601.21
#Mann=3,-1,0
  4652.4    0.15       0  4991.1    0.05       0  5008.9    0.15       0
Bank Sta=4991.1,5008.9
XS Rating Curve= 0
Exp/Cntr=0.3,0.1

Type RM Length L Ch R = 1,168500,500,500,500
BEGIN DESCRIPTION:
Chauga River 337.0
END DESCRIPTION:
XS GIS Cut Line= 3
      1354932.39      1104350.50      1354793.58      1104639.82
      1354592.37      1105158.03
#Sta/Elev= 30
  4679.1 1626.22  4707.0 1622.40  4777.5 1603.62  4810.3 1589.07  4827.9 1576.97
  4861.1 1559.55  4862.5 1554.71  4867.8 1548.52  4869.5 1556.16  4891.8 1549.12
  4977.5 1549.01  4984.9 1541.93  4989.2 1541.09  4989.7 1540.09  5010.8 1541.09
  5028.6 1546.09  5055.2 1548.87  5090.0 1549.31  5119.3 1543.90  5120.4 1541.09
  5123.2 1543.55  5176.2 1549.10  5344.1 1549.23  5359.0 1551.53  5376.0 1557.71
  5397.2 1567.43  5411.5 1577.84  5483.1 1606.55  5529.4 1613.62  5555.9 1613.68
#Mann=3,-1,0
  4679.1    0.15       0  4989.2    0.05       0  5010.8    0.15       0
Bank Sta=4989.2,5010.8
XS Rating Curve= 0
Exp/Cntr=0.3,0.1

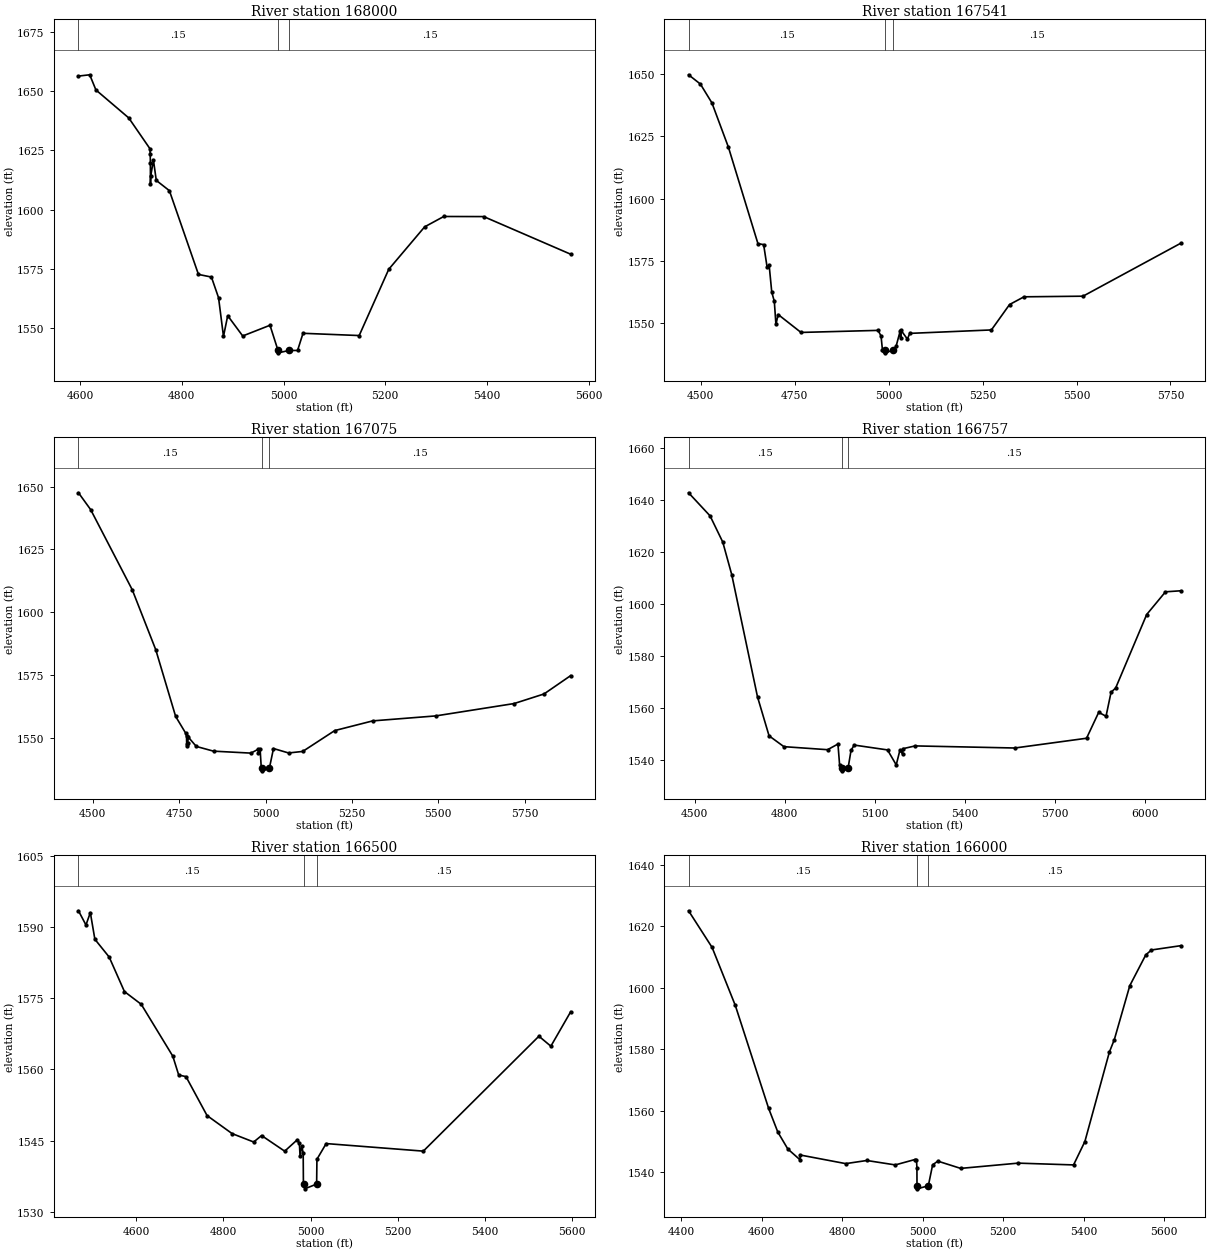
Type RM Length L Ch R = 1,168000,459,459,459
BEGIN DESCRIPTION:
Chauga River 336.0
END DESCRIPTION:
XS GIS Cut Line= 3
      1354677.39      1104222.99      1354493.97      1104581.83
      1354285.76      1105106.42
#Sta/Elev= 30
  4597.0 1656.28  4619.1 1656.83  4631.3 1650.44  4695.8 1638.67  4737.2 1625.78
  4738.0 1623.64  4738.3 1619.81  4738.5 1610.69  4739.0 1614.28  4744.4 1620.84
  4749.9 1612.36  4775.7 1608.03  4832.8 1572.77  4858.3 1571.66  4872.3 1562.97
  4882.0 1546.67  4890.3 1555.39  4919.8 1546.85  4973.4 1551.36  4989.2 1540.75
  4989.7 1539.75  5010.8 1540.75  5027.6 1540.75  5038.3 1547.98  5148.7 1547.03
  5206.8 1574.93  5277.3 1592.79  5314.9 1597.16  5393.4 1597.12  5564.4 1581.27
#Mann=3,-1,0
  4597.0    0.15       0  4989.2    0.05       0  5010.8    0.15       0
Bank Sta=4989.2,5010.8
XS Rating Curve= 0
Exp/Cntr=0.3,0.1

Type RM Length L Ch R = 1,167541,466,466,466
BEGIN DESCRIPTION:
Chauga River 335.0
END DESCRIPTION:
XS GIS Cut Line= 3
      1354355.58      1104050.00      1354112.86      1104523.85
      1353906.30      1105273.41
#Sta/Elev= 30
  4467.6 1649.55  4499.1 1645.83  4529.8 1638.28  4573.7 1620.54  4652.2 1581.96
  4667.4 1581.55  4676.7 1572.45  4682.1 1573.25  4689.0 1562.53  4695.8 1558.85
  4700.1 1549.60  4706.0 1553.57  4766.8 1546.40  4971.8 1547.22  4979.8 1544.99
  4983.6 1539.28  4989.2 1539.23  4989.7 1538.23  5010.8 1539.23  5019.9 1540.86
  5030.7 1546.96  5032.0 1544.20  5033.2 1547.22  5049.9 1543.74  5056.2 1546.02
  5273.5 1547.40  5321.8 1557.57  5360.2 1560.66  5517.3 1560.91  5777.5 1582.12
#Mann=3,-1,0
  4467.6    0.15       0  4989.2    0.05       0  5010.8    0.15       0
Bank Sta=4989.2,5010.8
XS Rating Curve= 0
Exp/Cntr=0.3,0.1

Type RM Length L Ch R = 1,167075,318,318,318
BEGIN DESCRIPTION:
Chauga River 334.5
END DESCRIPTION:
XS GIS Cut Line= 4
      1354328.26      1103949.82      1353846.31      1104197.12
      1353699.88      1104329.28      1353572.38      1105003.17
#Sta/Elev= 30
  4458.3 1647.52  4493.5 1640.83  4614.0 1608.88  4682.0 1585.01  4739.6 1558.42
  4768.4 1551.82  4771.1 1550.68  4771.5 1547.51  4772.3 1546.75  4774.7 1547.84
  4775.9 1550.23  4799.4 1546.48  4849.2 1544.60  4957.4 1543.82  4977.9 1545.31
  4979.3 1543.74  4984.1 1545.36  4987.5 1537.80  4989.2 1537.76  4989.7 1536.76
  5010.8 1537.76  5022.8 1545.65  5066.5 1543.88  5107.4 1544.49  5200.1 1552.80
  5310.1 1556.66  5492.5 1558.64  5719.2 1563.56  5805.8 1567.38  5883.1 1574.70
#Mann=3,-1,0
  4458.3    0.15       0  4989.2    0.05       0  5010.8    0.15       0
Bank Sta=4989.2,5010.8
XS Rating Curve= 0
Exp/Cntr=0.3,0.1

Type RM Length L Ch R = 1,166757,257,257,257
BEGIN DESCRIPTION:
Chauga River 334.0
END DESCRIPTION:
XS GIS Cut Line= 3
      1354158.25      1103737.03      1353675.61      1103931.64
      1352661.70      1104404.86
#Sta/Elev= 30
  4479.6 1642.91  4551.2 1634.01  4593.5 1623.91  4623.3 1611.40  4709.2 1564.25
  4747.7 1549.23  4797.1 1545.06  4942.6 1543.89  4977.1 1546.07  4982.7 1537.92
  4989.2 1536.74  4989.7 1535.74  5010.8 1536.74  5020.7 1543.66  5031.3 1545.67
  5142.2 1543.80  5171.2 1538.03  5183.4 1543.68  5193.0 1542.10  5193.3 1544.27
  5234.3 1545.35  5566.1 1544.54  5805.0 1548.30  5845.5 1558.29  5869.9 1556.78
  5886.6 1566.01  5902.0 1567.68  6005.3 1595.99  6067.9 1604.74  6118.9 1605.14
#Mann=3,-1,0
  4479.6    0.15       0  4989.2    0.05       0  5010.8    0.15       0
Bank Sta=4989.2,5010.8
XS Rating Curve= 0
Exp/Cntr=0.3,0.1

Type RM Length L Ch R = 1,166500,500,500,500
BEGIN DESCRIPTION:
Chauga River 333.0
END DESCRIPTION:
XS GIS Cut Line= 3
      1353982.59      1103466.64      1353521.03      1103731.18
      1352961.40      1103937.64
#Sta/Elev= 30
  4468.0 1593.38  4485.2 1590.39  4495.2 1593.00  4505.6 1587.39  4538.4 1583.65
  4573.4 1576.39  4611.9 1573.71  4684.3 1562.80  4697.8 1558.84  4714.5 1558.50
  4762.8 1550.31  4820.2 1546.52  4869.7 1544.75  4887.8 1546.11  4940.8 1542.82
  4970.0 1545.25  4974.5 1544.44  4976.0 1541.82  4979.8 1543.88  4983.2 1542.48
  4983.7 1535.90  4986.0 1535.90  4986.5 1534.90  5014.0 1535.90  5014.7 1541.12
  5035.9 1544.42  5258.6 1542.83  5523.6 1567.00  5551.0 1564.90  5596.5 1572.15
#Mann=3,-1,0
  4468.0    0.15       0  4986.0    0.05       0  5014.0    0.15       0
Bank Sta=4986,5014
XS Rating Curve= 0
Exp/Cntr=0.3,0.1

Type RM Length L Ch R = 1,166000,374,374,374
BEGIN DESCRIPTION:
Chauga River 332.0
END DESCRIPTION:
XS GIS Cut Line= 3
      1353797.03      1103105.29      1353263.84      1103336.86
      1352743.64      1103711.21
#Sta/Elev= 30
  4418.7 1624.98  4477.1 1613.07  4534.8 1594.18  4617.5 1560.71  4640.3 1553.01
  4665.2 1547.49  4695.3 1544.01  4696.1 1545.54  4808.9 1542.74  4861.3 1543.76
  4931.9 1542.32  4980.9 1544.08  4984.6 1543.81  4985.7 1541.45  4985.9 1535.54
  4986.0 1535.54  4986.5 1534.54  5014.0 1535.54  5024.7 1542.35  5037.6 1543.55
  5094.3 1541.19  5236.9 1542.90  5374.6 1542.32  5402.7 1549.92  5463.5 1579.01
  5475.9 1583.10  5514.3 1600.64  5554.0 1610.65  5568.1 1612.23  5640.9 1613.63
#Mann=3,-1,0
  4418.7    0.15       0  4986.0    0.05       0  5014.0    0.15       0
Bank Sta=4986,5014
XS Rating Curve= 0
Exp/Cntr=0.3,0.1

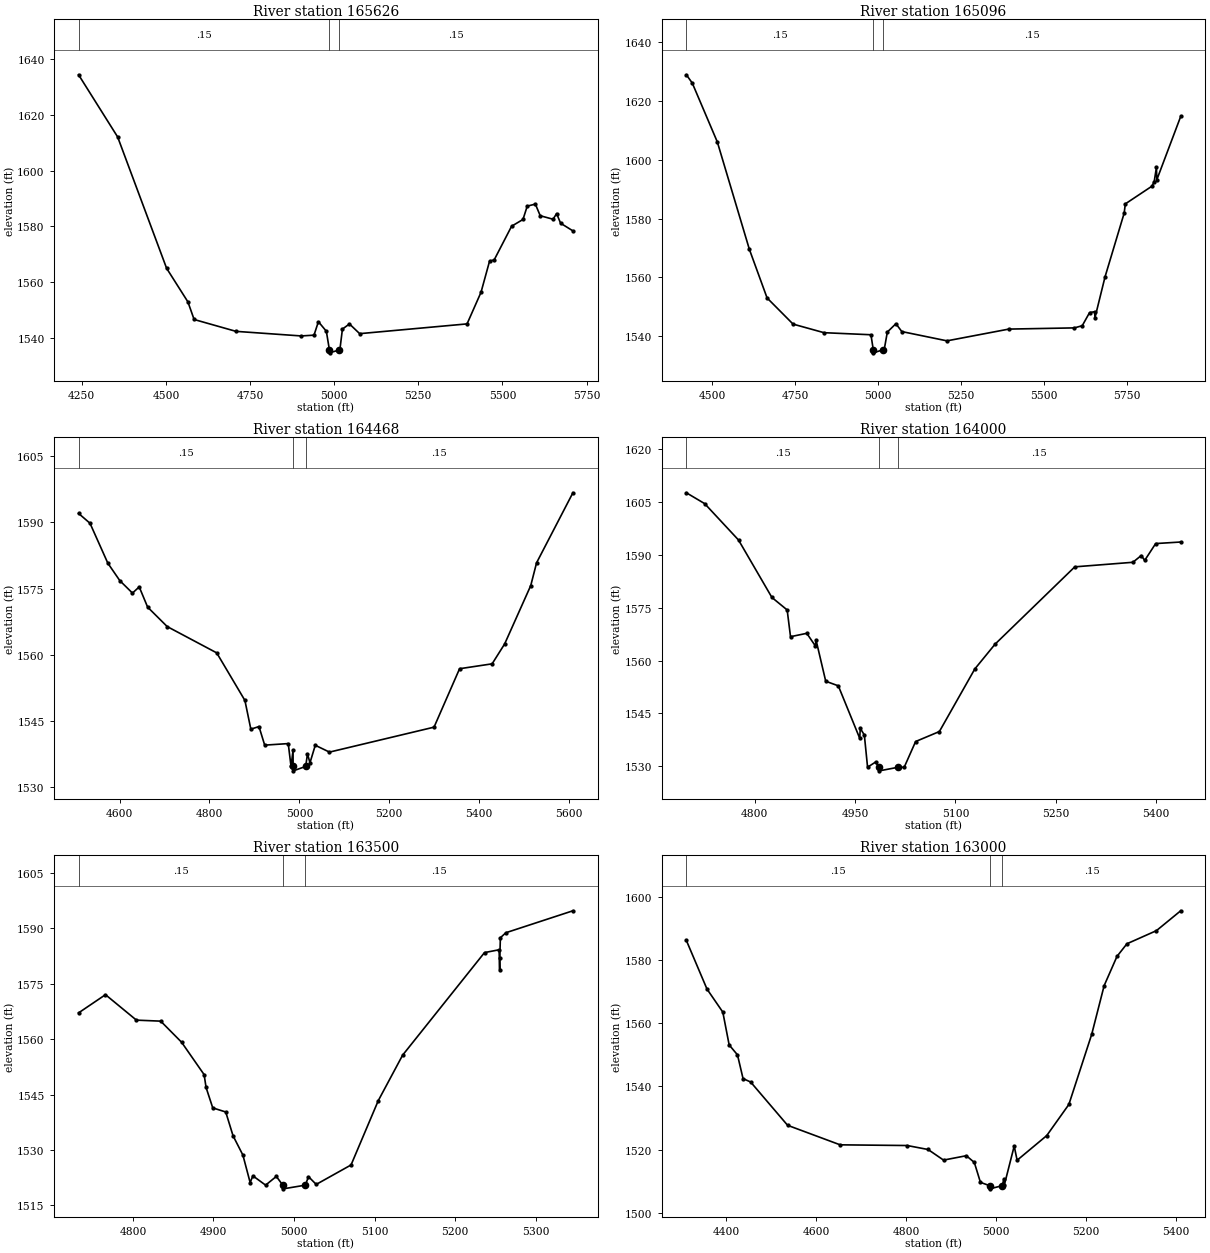
Type RM Length L Ch R = 1,165626,530,530,530
BEGIN DESCRIPTION:
Chauga River 331.0
END DESCRIPTION:
XS GIS Cut Line= 3
      1353821.90      1103014.53      1353062.54      1103033.65
      1352407.27      1103305.96
#Sta/Elev= 30
  4240.4 1634.44  4356.6 1612.09  4502.1 1564.90  4565.3 1552.86  4583.8 1546.52
  4708.2 1542.26  4902.0 1540.61  4940.1 1540.89  4953.2 1545.72  4976.8 1542.30
  4986.0 1535.54  4986.5 1534.54  5014.0 1535.54  5016.9 1535.54  5024.6 1543.08
  5045.5 1544.92  5075.8 1541.43  5395.0 1544.94  5436.5 1556.30  5461.8 1567.45
  5475.7 1567.95  5527.4 1580.03  5561.2 1582.46  5573.9 1587.25  5598.0 1587.98
  5612.5 1583.80  5650.6 1582.54  5661.2 1584.58  5673.0 1581.11  5709.6 1578.36
#Mann=3,-1,0
  4240.4    0.15       0  4986.0    0.05       0  5014.0    0.15       0
Bank Sta=4986,5014
XS Rating Curve= 0
Exp/Cntr=0.3,0.1

Type RM Length L Ch R = 1,165096,628,628,628
BEGIN DESCRIPTION:
Chauga River 330.0
END DESCRIPTION:
XS GIS Cut Line= 3
      1353739.97      1102720.06      1353162.86      1102709.52
      1352257.89      1102823.28
#Sta/Elev= 30
  4422.8 1628.81  4440.6 1626.00  4516.1 1606.00  4612.7 1569.53  4666.0 1553.05
  4744.3 1544.17  4837.5 1541.26  4978.9 1540.56  4986.0 1535.42  4986.5 1534.42
  5014.0 1535.42  5018.9 1535.54  5028.3 1541.48  5054.1 1544.31  5071.9 1541.64
  5207.9 1538.49  5394.2 1542.48  5591.8 1542.89  5615.5 1543.63  5637.5 1548.07
  5652.8 1548.40  5653.8 1546.34  5684.2 1560.23  5741.8 1581.85  5745.3 1584.99
  5825.7 1591.01  5832.3 1592.57  5839.0 1597.39  5840.2 1593.19  5912.1 1614.66
#Mann=3,-1,0
  4422.8    0.15       0  4986.0    0.05       0  5014.0    0.15       0
Bank Sta=4986,5014
XS Rating Curve= 0
Exp/Cntr=0.3,0.1

Type RM Length L Ch R = 1,164468,468,468,468
BEGIN DESCRIPTION:
Chauga River 329.0
END DESCRIPTION:
XS GIS Cut Line= 3
      1353548.07      1102568.27      1353088.37      1102395.20
      1352546.29      1102118.98
#Sta/Elev= 30
  4508.8 1592.02  4534.2 1589.79  4573.9 1580.75  4600.6 1576.79  4628.7 1573.98
  4643.7 1575.38  4662.4 1570.80  4705.9 1566.40  4816.1 1560.44  4878.8 1549.67
  4892.0 1543.16  4910.1 1543.76  4922.8 1539.55  4975.2 1539.90  4981.4 1534.73
  4985.9 1538.38  4986.0 1534.73  4986.5 1533.73  5014.0 1534.73  5018.0 1537.59
  5023.5 1535.54  5035.3 1539.52  5066.9 1537.97  5299.5 1543.62  5356.3 1556.85
  5428.7 1557.96  5456.6 1562.47  5514.6 1575.67  5527.6 1580.84  5608.4 1596.69
#Mann=3,-1,0
  4508.8    0.15       0  4986.0    0.05       0  5014.0    0.15       0
Bank Sta=4986,5014
XS Rating Curve= 0
Exp/Cntr=0.3,0.1

Type RM Length L Ch R = 1,164000,500,500,500
BEGIN DESCRIPTION:
Chauga River 328.0
END DESCRIPTION:
XS GIS Cut Line= 3
      1353624.57      1102593.74      1353499.61      1102318.92
      1353375.07      1101900.46
#Sta/Elev= 30
  4698.1 1607.49  4725.5 1604.41  4776.0 1594.12  4825.9 1577.85  4848.7 1574.31
  4853.7 1566.74  4878.0 1567.70  4890.9 1564.10  4891.8 1565.82  4906.3 1554.13
  4925.1 1552.83  4957.1 1537.97  4957.9 1540.80  4964.0 1538.90  4968.8 1529.79
  4980.7 1531.24  4986.0 1529.76  4986.5 1528.76  5014.0 1529.76  5023.5 1529.76
  5040.6 1537.06  5076.1 1539.89  5129.0 1557.60  5159.3 1564.63  5278.4 1586.52
  5365.2 1587.81  5377.7 1589.73  5382.8 1588.34  5399.2 1593.11  5436.6 1593.55
#Mann=3,-1,0
  4698.1    0.15       0  4986.0    0.05       0  5014.0    0.15       0
Bank Sta=4986,5014
XS Rating Curve= 0
Exp/Cntr=0.3,0.1

Type RM Length L Ch R = 1,163500,500,500,500
BEGIN DESCRIPTION:
Chauga River 327.0
END DESCRIPTION:
XS GIS Cut Line= 3
      1354133.99      1102083.18      1353874.18      1102019.91
      1353533.52      1101959.32
#Sta/Elev= 30
  4732.6 1567.13  4766.0 1572.06  4804.4 1565.16  4834.5 1564.89  4860.4 1559.18
  4888.4 1550.39  4890.8 1546.92  4899.1 1541.38  4915.2 1540.27  4924.3 1533.81
  4936.5 1528.59  4945.5 1521.14  4948.9 1522.96  4964.7 1520.44  4978.0 1522.81
  4986.0 1520.44  4986.5 1519.44  5014.0 1520.44  5017.9 1522.74  5027.5 1520.64
  5070.7 1525.91  5104.5 1543.35  5134.7 1555.67  5236.3 1583.47  5254.4 1584.23
  5255.1 1578.87  5255.3 1582.12  5256.0 1587.49  5262.8 1588.85  5346.0 1594.80
#Mann=3,-1,0
  4732.6    0.15       0  4986.0    0.05       0  5014.0    0.15       0
Bank Sta=4986,5014
XS Rating Curve= 0
Exp/Cntr=0.3,0.1

Type RM Length L Ch R = 1,163000,278,278,278
BEGIN DESCRIPTION:
Chauga River 326.0
END DESCRIPTION:
XS GIS Cut Line= 3
      1354514.02      1101631.46      1353831.39      1101541.00
      1353421.16      1101567.72
#Sta/Elev= 30
  4311.4 1586.30  4357.3 1570.88  4392.5 1563.58  4406.6 1553.18  4425.1 1550.03
  4437.5 1542.51  4454.4 1541.42  4536.6 1527.70  4653.5 1521.51  4802.6 1521.29
  4849.1 1520.03  4883.5 1516.67  4934.3 1518.06  4952.0 1515.92  4965.6 1509.62
  4986.0 1508.56  4986.5 1507.56  5014.0 1508.56  5017.9 1510.74  5018.6 1508.70
  5040.7 1521.11  5047.2 1516.62  5113.1 1524.44  5162.3 1534.30  5213.1 1556.52
  5240.8 1571.97  5269.4 1581.25  5291.5 1585.24  5357.1 1589.40  5411.1 1595.70
#Mann=3,-1,0
  4311.4    0.15       0  4986.0    0.05       0  5014.0    0.15       0
Bank Sta=4986,5014
XS Rating Curve= 0
Exp/Cntr=0.3,0.1