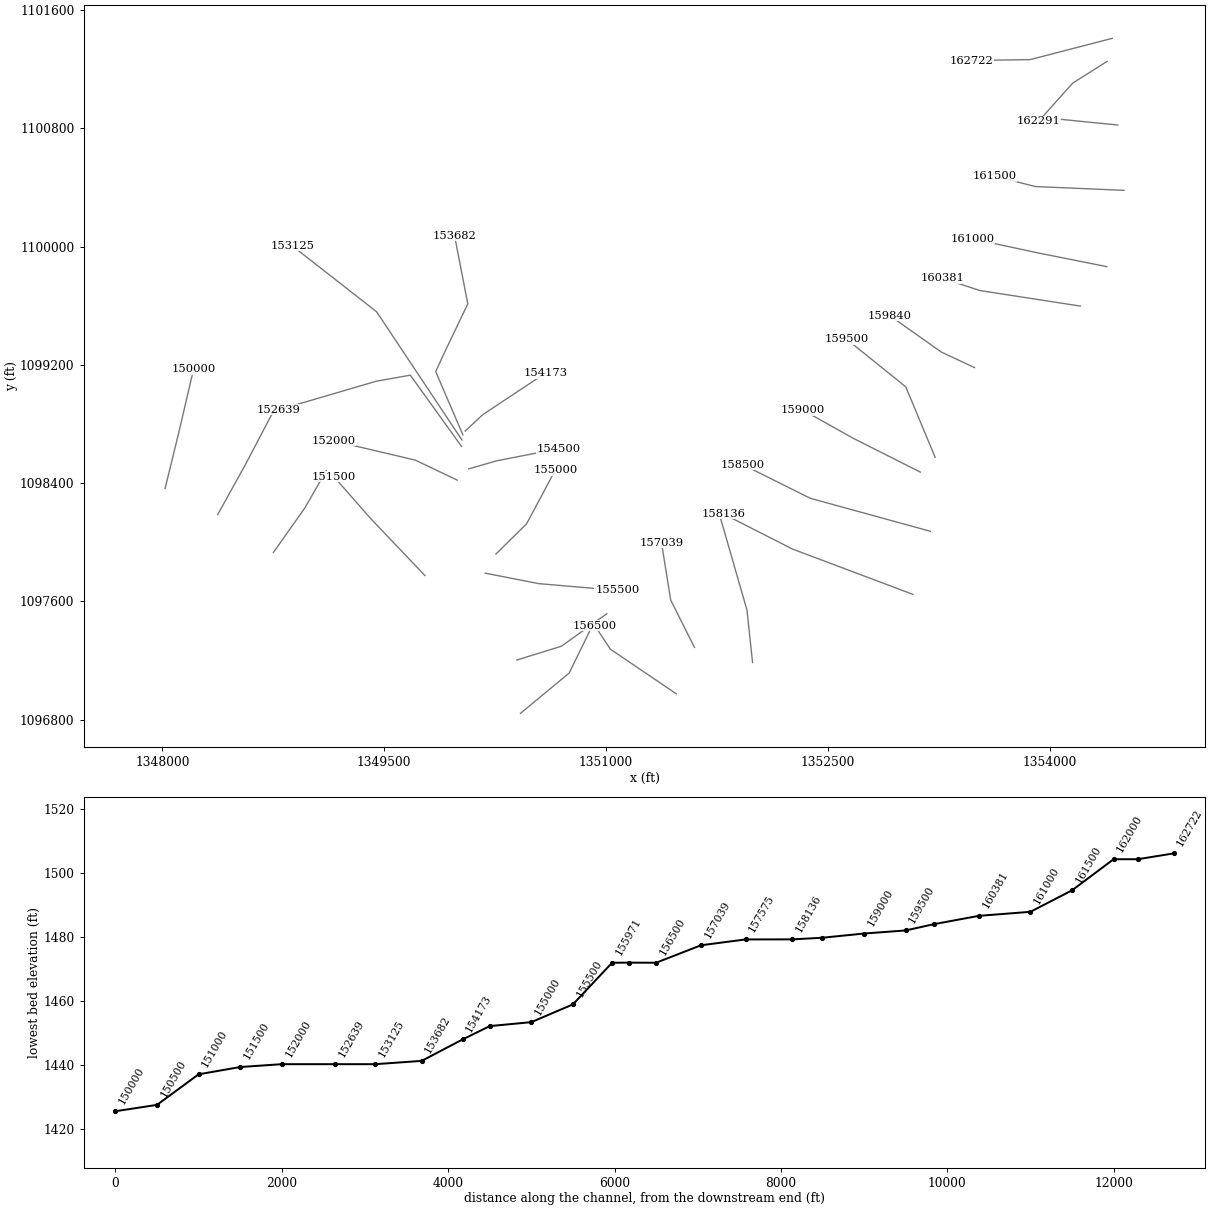
HEC-RAS study Chauga River.prj: Chauga River Limited Detail Study

--- Chauga River.g01 (geometry) --- (continued)

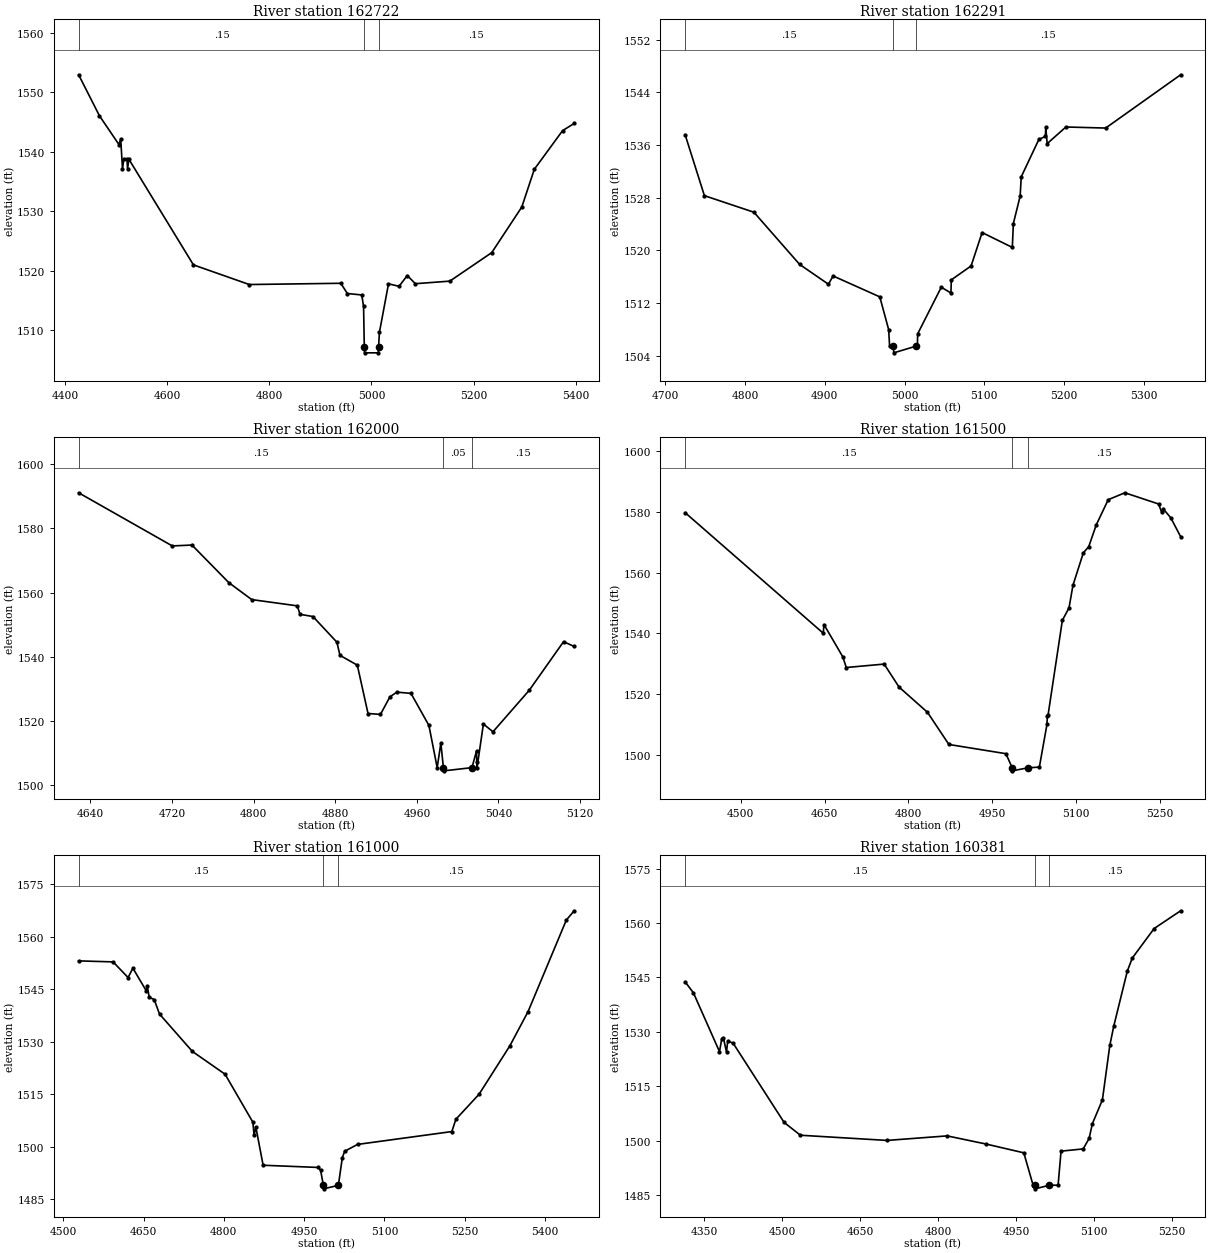
Type RM Length L Ch R = 1,162722,431,431,431
BEGIN DESCRIPTION:
Chauga River 325.0
END DESCRIPTION:
XS GIS Cut Line= 3
      1354422.96      1101409.04      1353867.89      1101265.24
      1353470.94      1101258.98
#Sta/Elev= 30
  4426.6 1552.92  4467.4 1546.03  4505.5 1541.21  4509.0 1542.14  4512.5 1537.13
  4515.1 1538.78  4521.3 1538.73  4522.4 1537.14  4525.0 1538.74  4651.4 1521.00
  4760.8 1517.70  4940.0 1517.91  4952.8 1516.19  4981.0 1515.95  4984.6 1514.02
  4986.0 1507.23  4986.5 1506.23  5013.5 1506.23  5014.0 1507.23  5015.6 1509.66
  5033.4 1517.82  5054.0 1517.40  5070.2 1519.21  5086.0 1517.84  5153.5 1518.27
  5235.6 1523.06  5294.4 1530.71  5319.0 1537.06  5374.4 1543.55  5397.0 1544.75
#Mann=3,-1,0
  4426.6    0.15       0  4986.0    0.05       0  5014.0    0.15       0
Bank Sta=4986,5014
XS Rating Curve= 0
Exp/Cntr=0.3,0.1

Type RM Length L Ch R = 1,162291,291,291,291
BEGIN DESCRIPTION:
Chauga River 324.5
END DESCRIPTION:
XS GIS Cut Line= 3
      1354387.99      1101253.34      1354155.39      1101106.27
      1353924.48      1100848.19
#Sta/Elev= 30
  4724.8 1537.59  4749.0 1528.31  4811.1 1525.79  4868.4 1517.86  4904.6 1514.84
  4910.4 1516.10  4969.0 1512.92  4980.1 1507.94  4981.3 1505.41  4986.0 1505.41
  4986.5 1504.41  5014.0 1505.41  5016.1 1505.41  5016.5 1507.30  5046.1 1514.39
  5058.2 1513.51  5058.7 1515.51  5083.5 1517.62  5097.3 1522.70  5135.2 1520.44
  5136.5 1524.07  5145.0 1528.23  5146.4 1531.18  5168.5 1536.86  5176.7 1537.32
  5177.1 1538.76  5178.9 1536.22  5202.4 1538.75  5252.3 1538.59  5346.3 1546.69
#Mann=3,-1,0
  4724.8    0.15       0  4986.0    0.05       0  5014.0    0.15       0
Bank Sta=4986,5014
XS Rating Curve= 0
Exp/Cntr=0.3,0.1

Type RM Length L Ch R = 1,162000,500,500,500
BEGIN DESCRIPTION:
Chauga River 324.0
END DESCRIPTION:
XS GIS Cut Line= 3
      1354459.37      1100822.76      1354089.61      1100859.65
      1353976.17      1100872.84
#Sta/Elev= 30
  4628.4 1591.12  4720.2 1574.55  4739.5 1574.82  4775.6 1563.11  4798.1 1557.81
  4842.8 1555.86  4845.4 1553.22  4858.1 1552.53  4881.6 1544.52  4884.6 1540.42
  4901.6 1537.37  4912.1 1522.29  4924.3 1522.01  4933.6 1527.51  4940.4 1528.95
  4954.2 1528.57  4971.8 1518.57  4979.9 1505.41  4983.5 1513.05  4986.0 1505.41
  4986.5 1504.41  5014.0 1505.41  5018.5 1510.66  5018.7 1507.12  5019.0 1505.41
  5025.2 1519.01  5034.6 1516.59  5070.1 1529.51  5103.8 1544.69  5114.2 1543.19
#Mann=3,-1,0
  4628.4    0.15       0  4986.0    0.05       0  5014.0    0.15       0
Bank Sta=4986,5014
XS Rating Curve= 0
Exp/Cntr=0.3,0.1

Type RM Length L Ch R = 1,161500,500,500,500
BEGIN DESCRIPTION:
Chauga River 323.0
END DESCRIPTION:
XS GIS Cut Line= 3
      1354501.86      1100380.76      1353902.61      1100406.47
      1353624.02      1100477.89
#Sta/Elev= 30
  4400.2 1579.77  4647.6 1540.03  4648.9 1542.88  4682.6 1532.25  4688.8 1528.73
  4756.7 1529.86  4783.3 1522.29  4834.2 1513.98  4872.6 1503.37  4974.7 1500.33
  4986.0 1495.68  4986.5 1494.68  5014.0 1495.68  5034.6 1495.91  5048.2 1509.96
  5048.9 1512.80  5050.1 1512.96  5075.8 1544.28  5087.7 1548.39  5094.8 1555.83
  5113.3 1566.50  5123.0 1568.55  5136.5 1575.73  5157.9 1584.03  5187.7 1586.31
  5248.1 1582.62  5253.6 1579.89  5256.9 1580.93  5270.0 1578.03  5287.6 1571.86
#Mann=3,-1,0
  4400.2    0.15       0  4986.0    0.05       0  5014.0    0.15       0
Bank Sta=4986,5014
XS Rating Curve= 0
Exp/Cntr=0.3,0.1

Type RM Length L Ch R = 1,161000,619,619,619
BEGIN DESCRIPTION:
Chauga River 322.0
END DESCRIPTION:
XS GIS Cut Line= 3
      1354385.93      1099864.69      1353923.75      1099956.92
      1353479.24      1100052.21
#Sta/Elev= 30
  4528.7 1553.07  4593.1 1552.78  4621.1 1548.32  4630.1 1550.98  4655.4 1544.43
  4656.8 1546.00  4660.6 1542.66  4669.9 1542.03  4679.8 1537.89  4741.2 1527.21
  4802.3 1520.70  4854.3 1506.98  4856.5 1503.29  4859.9 1505.55  4873.4 1494.70
  4976.3 1494.07  4980.8 1493.27  4986.0 1488.96  4986.5 1487.96  5014.0 1488.96
  5021.4 1496.86  5025.8 1498.70  5049.9 1500.65  5226.0 1504.32  5233.6 1507.83
  5276.9 1514.98  5334.4 1528.80  5368.5 1538.60  5439.9 1564.72  5454.6 1567.38
#Mann=3,-1,0
  4528.7    0.15       0  4986.0    0.05       0  5014.0    0.15       0
Bank Sta=4986,5014
XS Rating Curve= 0
Exp/Cntr=0.3,0.1

Type RM Length L Ch R = 1,160381,541,541,541
BEGIN DESCRIPTION:
Chauga River 321.0
END DESCRIPTION:
XS GIS Cut Line= 3
      1354207.46      1099597.85      1353528.24      1099702.92
      1353274.84      1099785.77
#Sta/Elev= 30
  4312.7 1543.79  4328.7 1540.75  4378.9 1524.54  4383.4 1528.15  4386.4 1528.36
  4392.4 1524.43  4394.7 1527.36  4404.8 1526.94  4503.3 1505.01  4534.7 1501.48
  4701.4 1500.05  4817.1 1501.30  4892.2 1499.05  4964.7 1496.63  4982.6 1487.70
  4986.0 1487.70  4986.5 1486.70  5014.0 1487.70  5030.7 1487.70  5036.4 1497.09
  5079.0 1497.71  5090.4 1500.59  5096.6 1504.63  5116.0 1511.23  5130.3 1526.28
  5138.0 1531.65  5164.0 1546.76  5173.5 1550.33  5215.6 1558.48  5266.6 1563.37
#Mann=3,-1,0
  4312.7    0.15       0  4986.0    0.05       0  5014.0    0.15       0
Bank Sta=4986,5014
XS Rating Curve= 0
Exp/Cntr=0.3,0.1

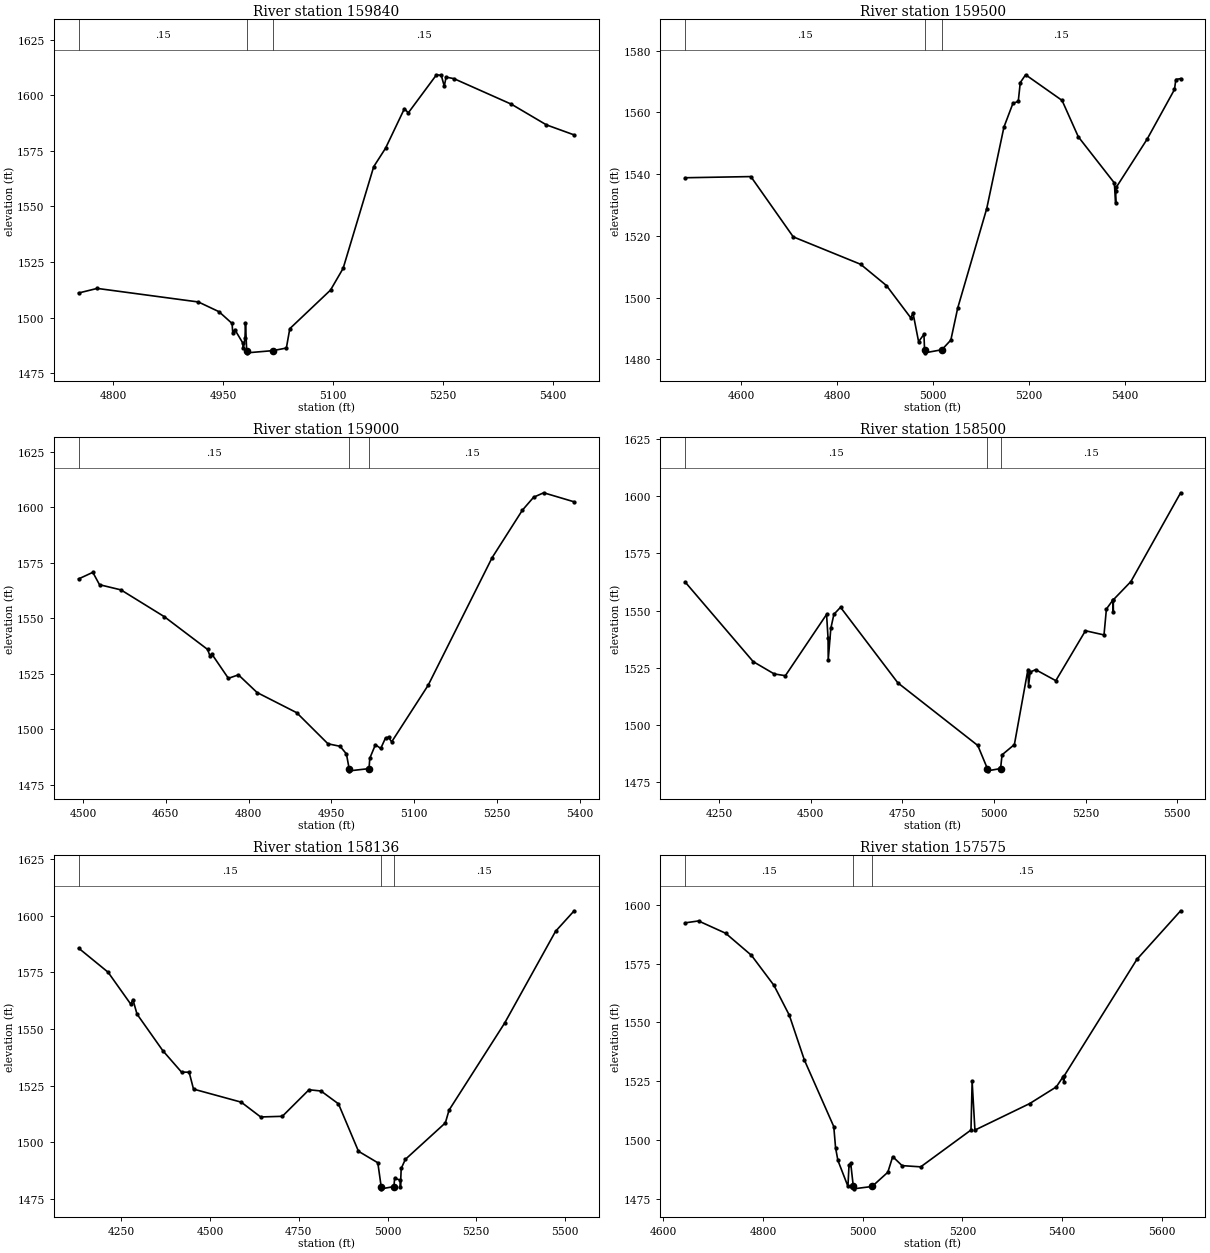
Type RM Length L Ch R = 1,159840,340,340,340
BEGIN DESCRIPTION:
Chauga River 320.0
END DESCRIPTION:
XS GIS Cut Line= 3
      1353491.01      1099181.97      1353267.22      1099286.75
      1352917.31      1099534.08
#Sta/Elev= 30
  4752.9 1511.03  4778.2 1513.10  4916.2 1506.99  4944.3 1502.61  4962.1 1497.32
  4963.0 1493.13  4965.8 1494.57  4976.6 1488.59  4977.5 1486.26  4979.7 1490.65
  4980.4 1497.68  4982.0 1485.10  4982.5 1484.10  5018.0 1485.10  5036.1 1486.26
  5040.8 1494.98  5096.3 1512.34  5113.5 1522.12  5155.2 1567.89  5171.3 1576.18
  5197.1 1594.02  5202.3 1592.09  5240.8 1609.25  5247.3 1609.00  5251.4 1604.12
  5253.9 1608.21  5264.6 1607.50  5343.0 1595.99  5390.7 1586.70  5428.5 1582.18
#Mann=3,-1,0
  4752.9    0.15       0  4982.0    0.05       0  5018.0    0.15       0
Bank Sta=4982,5018
XS Rating Curve= 0
Exp/Cntr=0.3,0.1

Type RM Length L Ch R = 1,159500,500,500,500
BEGIN DESCRIPTION:
Chauga River 319.0
END DESCRIPTION:
XS GIS Cut Line= 3
      1353224.99      1098575.02      1353026.27      1099051.86
      1352625.00      1099375.00
#Sta/Elev= 30
  4483.4 1538.82  4620.3 1539.20  4708.6 1519.68  4848.9 1510.80  4902.7 1503.91
  4953.6 1493.40  4957.8 1495.15  4969.6 1485.74  4980.7 1488.13  4982.0 1483.13
  4982.5 1482.13  5018.0 1483.13  5036.7 1486.26  5051.0 1496.62  5111.4 1528.81
  5147.3 1555.23  5166.0 1562.91  5177.1 1563.54  5181.3 1569.64  5192.4 1572.16
  5268.3 1563.86  5302.1 1552.09  5377.1 1537.15  5379.9 1530.62  5380.3 1534.42
  5381.1 1535.71  5445.3 1551.29  5502.4 1567.40  5505.2 1570.63  5515.2 1570.93
#Mann=3,-1,0
  4483.4    0.15       0  4982.0    0.05       0  5018.0    0.15       0
Bank Sta=4982,5018
XS Rating Curve= 0
Exp/Cntr=0.3,0.1

Type RM Length L Ch R = 1,159000,500,500,500
BEGIN DESCRIPTION:
Chauga River 318.0
END DESCRIPTION:
XS GIS Cut Line= 3
      1353124.97      1098475.02      1352671.53      1098703.38
      1352331.87      1098893.81
#Sta/Elev= 30
  4492.3 1567.71  4518.0 1570.67  4530.1 1565.09  4568.9 1562.76  4647.2 1550.71
  4725.8 1535.90  4730.2 1532.83  4733.0 1533.98  4763.4 1522.88  4781.6 1524.45
  4815.4 1516.47  4887.1 1507.38  4943.7 1493.36  4965.7 1492.23  4977.1 1488.79
  4982.0 1482.17  4982.5 1481.17  5018.0 1482.17  5019.4 1486.84  5029.6 1492.96
  5039.2 1491.25  5047.9 1496.01  5053.3 1496.31  5059.0 1494.23  5125.0 1519.73
  5240.8 1577.26  5295.6 1598.68  5316.0 1604.54  5334.2 1606.54  5389.4 1602.46
#Mann=3,-1,0
  4492.3    0.15       0  4982.0    0.05       0  5018.0    0.15       0
Bank Sta=4982,5018
XS Rating Curve= 0
Exp/Cntr=0.3,0.1

Type RM Length L Ch R = 1,158500,364,364,364
BEGIN DESCRIPTION:
Chauga River 317.0
END DESCRIPTION:
XS GIS Cut Line= 3
      1353193.38      1098074.44      1352380.80      1098297.72
      1351925.02      1098524.99
#Sta/Elev= 30
  4157.3 1562.51  4343.1 1527.65  4400.4 1522.26  4430.9 1521.49  4543.3 1548.31
  4547.3 1537.95  4547.8 1528.43  4554.9 1542.21  4563.3 1548.36  4581.4 1551.43
  4737.8 1518.35  4955.9 1490.94  4982.0 1480.85  4982.5 1479.85  5018.0 1480.85
  5022.1 1486.86  5055.7 1491.35  5092.7 1524.18  5094.4 1517.05  5098.7 1523.04
  5113.5 1524.14  5168.7 1519.31  5249.6 1541.16  5300.2 1539.33  5306.8 1550.68
  5324.6 1554.60  5325.6 1549.22  5325.7 1554.71  5373.6 1562.69  5509.3 1601.54
#Mann=3,-1,0
  4157.3    0.15       0  4982.0    0.05       0  5018.0    0.15       0
Bank Sta=4982,5018
XS Rating Curve= 0
Exp/Cntr=0.3,0.1

Type RM Length L Ch R = 1,158136,561,561,561
BEGIN DESCRIPTION:
Chauga River 316.0
END DESCRIPTION:
XS GIS Cut Line= 3
      1353074.75      1097647.85      1352260.08      1097954.57
      1351791.40      1098193.12
#Sta/Elev= 30
  4129.5 1585.77  4212.4 1575.14  4276.6 1560.95  4282.4 1563.05  4294.0 1556.61
  4366.6 1540.46  4419.4 1530.96  4440.9 1530.91  4453.2 1523.44  4587.6 1517.67
  4642.5 1511.12  4703.5 1511.41  4778.7 1523.15  4812.5 1522.60  4861.7 1516.92
  4918.1 1495.95  4972.6 1490.87  4982.0 1480.34  4982.5 1479.34  5018.0 1480.34
  5019.9 1483.97  5036.2 1483.21  5036.3 1480.34  5038.5 1488.34  5050.1 1492.36
  5162.9 1508.50  5173.3 1514.14  5329.9 1552.61  5473.4 1593.20  5525.9 1602.29
#Mann=3,-1,0
  4129.5    0.15       0  4982.0    0.05       0  5018.0    0.15       0
Bank Sta=4982,5018
XS Rating Curve= 0
Exp/Cntr=0.3,0.1

Type RM Length L Ch R = 1,157575,536,536,536
BEGIN DESCRIPTION:
Chauga River 315.0
END DESCRIPTION:
XS GIS Cut Line= 3
      1351990.22      1097186.92      1351952.74      1097541.14
      1351776.33      1098153.95
#Sta/Elev= 30
  4643.8 1592.29  4670.7 1593.10  4725.1 1587.88  4776.9 1578.49  4822.0 1565.75
  4852.8 1553.07  4883.1 1533.99  4942.0 1505.76  4945.6 1496.76  4950.3 1491.38
  4970.4 1480.38  4972.6 1489.45  4976.0 1490.10  4981.2 1480.32  4981.7 1479.32
  5018.8 1480.32  5050.4 1486.36  5060.2 1493.01  5079.0 1489.18  5116.4 1488.66
  5217.2 1504.30  5219.5 1524.94  5225.1 1504.27  5334.9 1515.53  5388.3 1522.61
  5401.2 1526.69  5403.7 1524.60  5404.3 1527.36  5550.0 1576.79  5637.7 1597.42
#Mann=3,-1,0
  4643.8    0.15       0  4981.2    0.05       0  5018.8    0.15       0
Bank Sta=4981.2,5018.8
XS Rating Curve= 0
Exp/Cntr=0.3,0.1

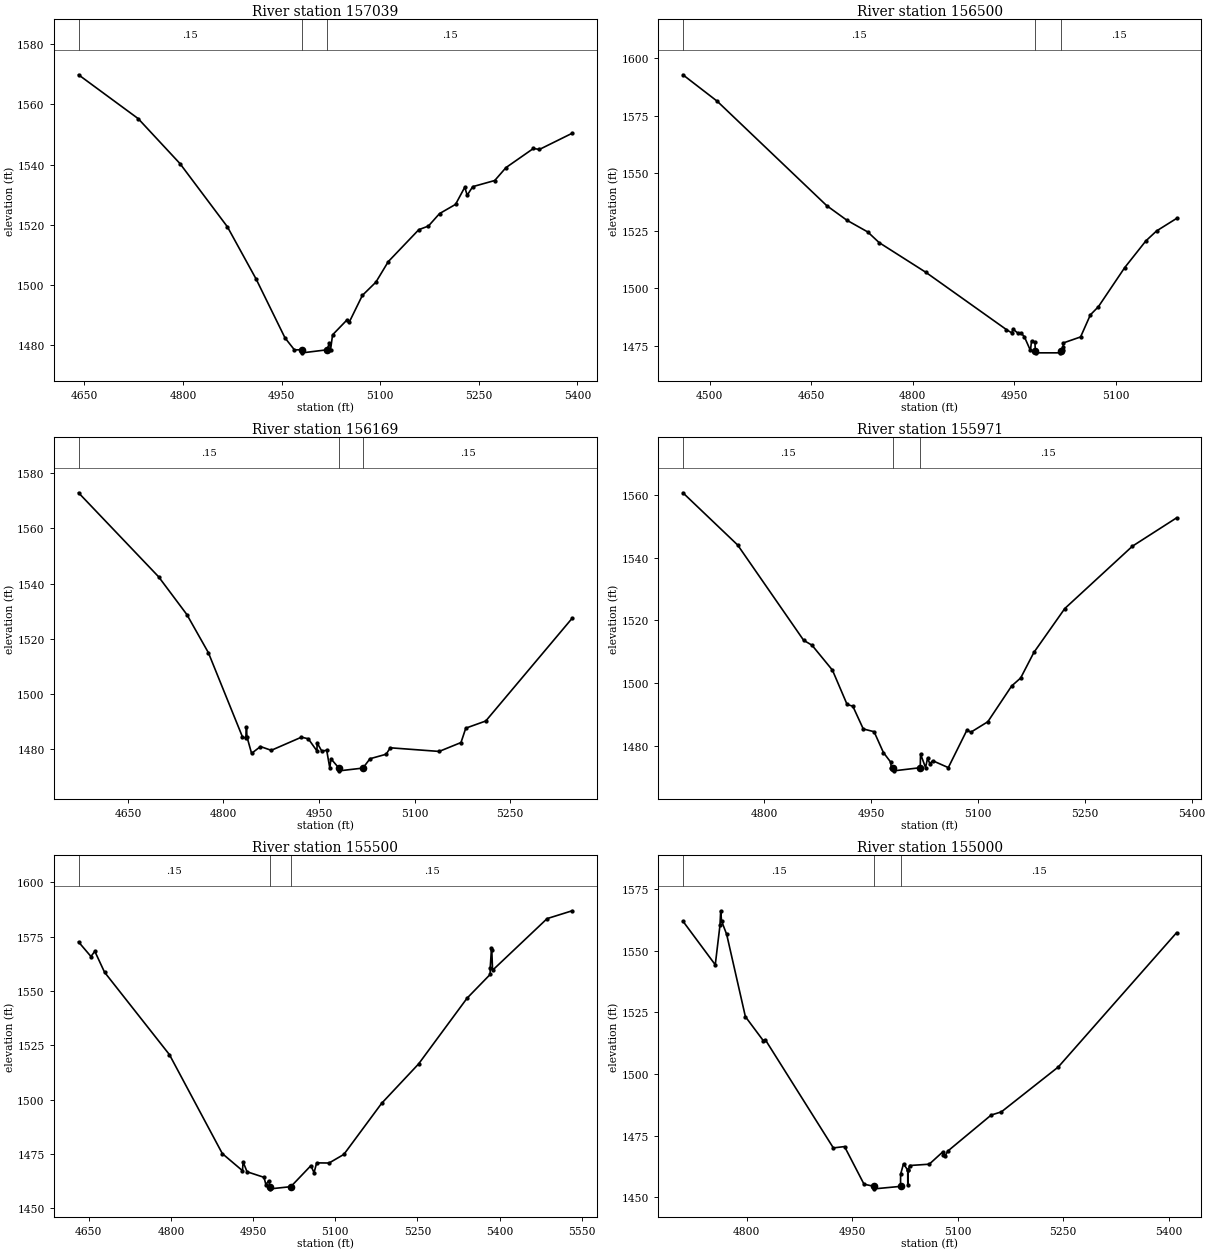
Type RM Length L Ch R = 1,157039,539,539,539
BEGIN DESCRIPTION:
Chauga River 314.0
END DESCRIPTION:
XS GIS Cut Line= 3
      1351597.40      1097289.36      1351436.56      1097610.20
      1351374.46      1097997.35
#Sta/Elev= 30
  4641.1 1569.82  4731.8 1555.27  4795.4 1540.34  4867.6 1519.33  4911.4 1501.94
  4955.2 1482.46  4969.5 1478.49  4981.2 1478.49  4981.7 1477.49  5018.8 1478.49
  5022.9 1480.72  5024.5 1478.49  5027.6 1483.47  5048.8 1488.26  5052.8 1487.61
  5072.9 1496.56  5093.5 1500.96  5112.3 1507.77  5158.8 1518.39  5173.4 1519.59
  5190.3 1523.72  5214.7 1526.79  5228.7 1532.49  5232.4 1529.82  5240.8 1532.67
  5274.3 1534.71  5291.4 1539.00  5333.2 1545.36  5342.2 1545.02  5392.1 1550.40
#Mann=3,-1,0
  4641.1    0.15       0  4981.2    0.05       0  5018.8    0.15       0
Bank Sta=4981.2,5018.8
XS Rating Curve= 0
Exp/Cntr=0.3,0.1

Type RM Length L Ch R = 1,156500,331,331,331
BEGIN DESCRIPTION:
Chauga River 313.0
END DESCRIPTION:
XS GIS Cut Line= 3
      1351474.99      1096975.00      1351028.52      1097277.50
      1350923.79      1097435.79
#Sta/Elev= 30
  4460.7 1592.83  4511.3 1581.36  4673.1 1535.99  4702.8 1529.66  4733.7 1524.55
  4750.5 1519.93  4819.3 1507.06  4938.5 1482.14  4946.5 1480.68  4948.2 1482.34
  4955.3 1480.63  4959.7 1480.76  4965.0 1479.06  4974.0 1473.06  4975.7 1477.28
  4980.7 1476.53  4981.2 1473.03  4981.7 1472.03  5018.3 1472.03  5018.8 1473.03
  5021.9 1474.51  5022.1 1473.06  5022.6 1476.33  5048.1 1478.94  5062.6 1488.56
  5074.3 1492.03  5113.3 1509.07  5144.5 1520.66  5160.3 1524.98  5189.8 1530.41
#Mann=3,-1,0
  4460.7    0.15       0  4981.2    0.05       0  5018.8    0.15       0
Bank Sta=4981.2,5018.8
XS Rating Curve= 0
Exp/Cntr=0.3,0.1

Type RM Length L Ch R = 1,156169,198,198,198
BEGIN DESCRIPTION:
Chauga River 312.5
END DESCRIPTION:
XS GIS Cut Line= 3
      1350420.70      1096842.91      1350750.08      1097115.42
      1350902.73      1097427.38
#Sta/Elev= 30
  4572.5 1572.92  4698.1 1542.47  4742.5 1528.76  4776.3 1514.92  4829.8 1484.36
  4835.0 1483.98  4836.1 1487.84  4836.9 1484.36  4844.1 1478.40  4858.1 1480.87
  4875.0 1479.50  4922.4 1484.27  4933.1 1483.69  4946.8 1479.25  4946.9 1482.23
  4954.4 1479.20  4962.0 1479.53  4966.9 1473.06  4968.7 1476.43  4981.2 1473.06
  4981.7 1472.06  5018.8 1473.06  5030.0 1476.45  5055.3 1478.08  5061.8 1480.42
  5138.5 1479.10  5172.8 1482.32  5180.3 1487.54  5211.7 1490.14  5347.3 1527.41
#Mann=3,-1,0
  4572.5    0.15       0  4981.2    0.05       0  5018.8    0.15       0
Bank Sta=4981.2,5018.8
XS Rating Curve= 0
Exp/Cntr=0.3,0.1

Type RM Length L Ch R = 1,155971,471,471,471
BEGIN DESCRIPTION:
Chauga River 312.0
END DESCRIPTION:
XS GIS Cut Line= 3
      1350396.61      1097203.82      1350697.03      1097296.88
      1351005.11      1097517.10
#Sta/Elev= 30
  4685.5 1560.72  4762.4 1544.06  4855.1 1513.66  4866.8 1512.10  4895.5 1504.15
  4916.1 1493.19  4924.1 1492.66  4938.8 1485.39  4954.0 1484.51  4967.1 1477.86
  4977.4 1474.78  4978.0 1473.06  4981.2 1473.03  4981.7 1472.03  5018.8 1473.03
  5019.2 1477.38  5026.3 1473.06  5029.0 1476.00  5032.3 1474.35  5036.3 1475.26
  5058.2 1473.06  5084.3 1484.99  5090.0 1484.37  5113.7 1487.69  5147.2 1499.11
  5159.8 1501.64  5178.4 1509.80  5221.8 1523.80  5316.8 1543.69  5378.7 1552.71
#Mann=3,-1,0
  4685.5    0.15       0  4981.2    0.05       0  5018.8    0.15       0
Bank Sta=4981.2,5018.8
XS Rating Curve= 0
Exp/Cntr=0.3,0.1

Type RM Length L Ch R = 1,155500,500,500,500
BEGIN DESCRIPTION:
Chauga River 311.0
END DESCRIPTION:
XS GIS Cut Line= 3
      1350182.69      1097791.26      1350544.55      1097720.58
      1351074.99      1097675.00
#Sta/Elev= 30
  4631.3 1572.65  4654.0 1565.93  4661.0 1568.34  4678.8 1558.69  4797.2 1520.78
  4893.8 1475.21  4930.6 1467.35  4931.7 1471.40  4938.9 1466.86  4969.9 1464.29
  4973.3 1460.92  4978.1 1462.68  4981.2 1460.00  4981.7 1459.00  5018.8 1460.00
  5055.5 1469.68  5061.2 1466.41  5066.0 1470.96  5088.6 1470.88  5115.7 1474.86
  5184.6 1498.36  5252.0 1516.47  5340.6 1546.77  5382.7 1557.68  5382.8 1560.64
  5385.1 1569.65  5385.7 1568.71  5387.1 1559.61  5486.7 1583.38  5532.4 1586.98
#Mann=3,-1,0
  4631.3    0.15       0  4981.2    0.05       0  5018.8    0.15       0
Bank Sta=4981.2,5018.8
XS Rating Curve= 0
Exp/Cntr=0.3,0.1

Type RM Length L Ch R = 1,155000,500,500,500
BEGIN DESCRIPTION:
Chauga River 310.0
END DESCRIPTION:
XS GIS Cut Line= 3
      1350255.05      1097920.81      1350461.99      1098124.68
      1350655.70      1098487.17
#Sta/Elev= 30
  4709.5 1561.96  4755.5 1544.27  4762.2 1560.31  4763.2 1566.16  4764.4 1562.03
  4771.7 1556.61  4798.3 1523.25  4823.7 1513.53  4826.6 1513.91  4923.3 1470.04
  4939.2 1470.58  4966.9 1455.33  4981.2 1454.45  4981.7 1453.45  5018.8 1454.45
  5018.9 1459.37  5023.0 1463.58  5029.0 1461.06  5029.1 1454.91  5029.7 1460.92
  5031.7 1462.90  5059.6 1463.44  5078.9 1468.45  5079.2 1467.21  5082.2 1466.76
  5085.8 1468.72  5147.6 1483.36  5162.1 1484.65  5243.0 1502.85  5411.0 1557.25
#Mann=3,-1,0
  4709.5    0.15       0  4981.2    0.05       0  5018.8    0.15       0
Bank Sta=4981.2,5018.8
XS Rating Curve= 0
Exp/Cntr=0.3,0.1

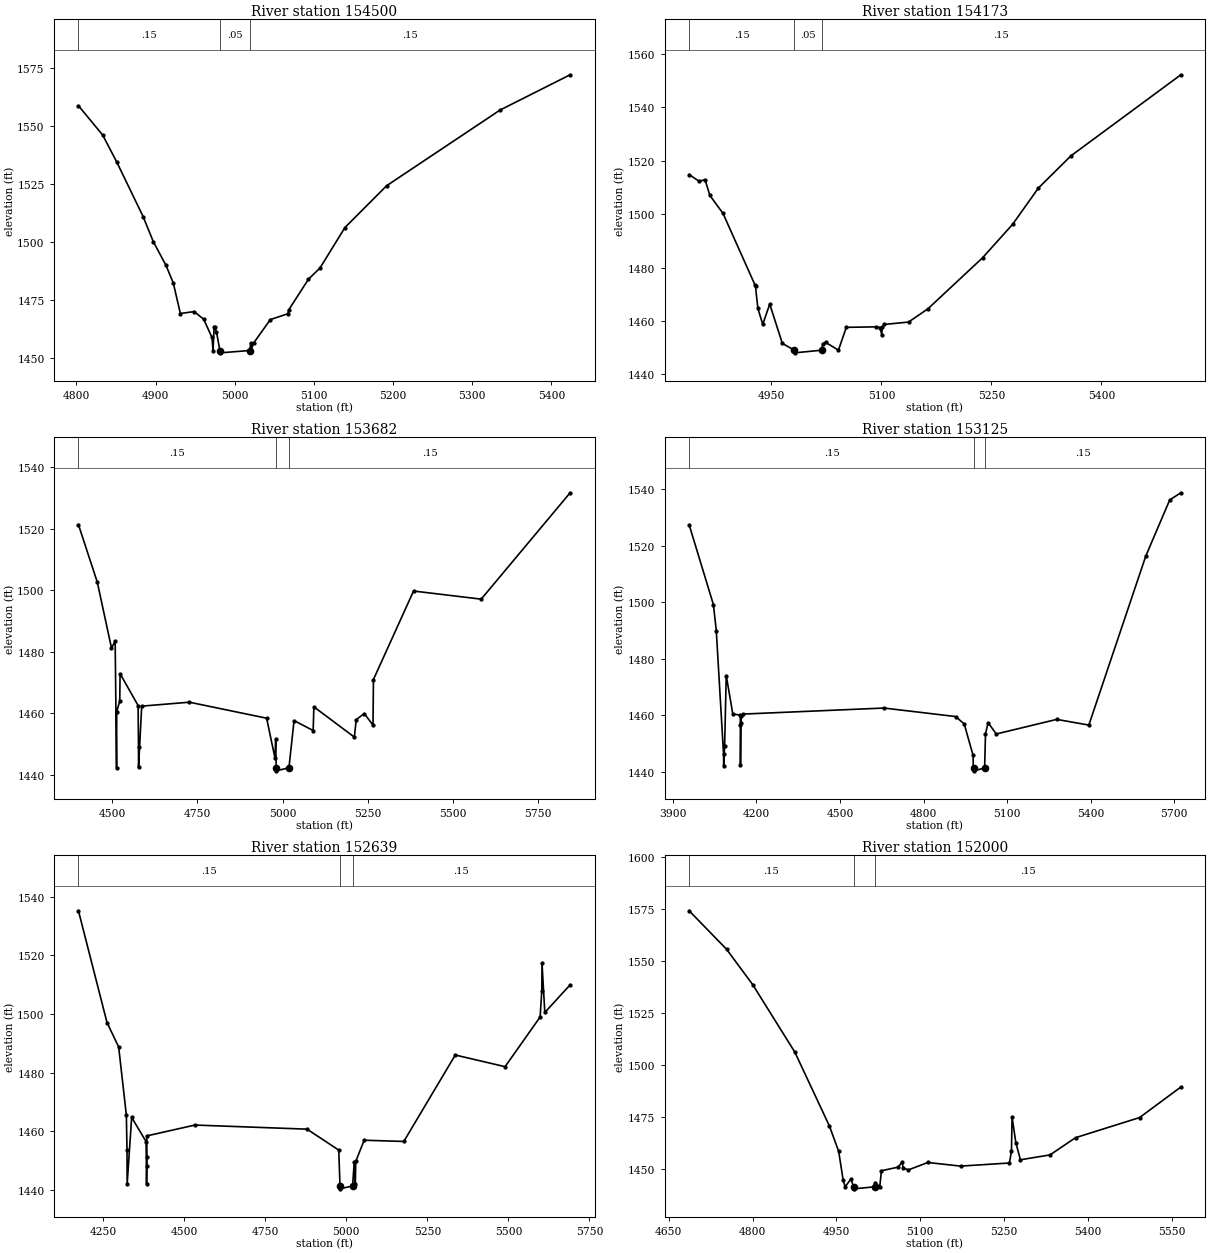
Type RM Length L Ch R = 1,154500,327,327,327
BEGIN DESCRIPTION:
Chauga River 309.0
END DESCRIPTION:
XS GIS Cut Line= 3
      1350071.28      1098496.78      1350260.90      1098551.66
      1350676.75      1098632.34
#Sta/Elev= 30
  4802.6 1558.82  4833.2 1546.18  4850.8 1534.66  4884.3 1510.99  4897.1 1500.22
  4913.1 1490.00  4922.5 1482.22  4931.3 1469.18  4948.7 1470.00  4960.8 1466.70
  4971.3 1458.83  4972.6 1453.21  4973.9 1463.17  4974.6 1463.25  4976.9 1461.39
  4981.2 1453.21  4981.7 1452.21  5018.8 1453.21  5020.3 1456.36  5020.6 1453.21
  5023.7 1456.38  5045.0 1466.56  5067.2 1469.09  5068.0 1470.65  5093.1 1483.97
  5107.7 1488.81  5139.1 1506.24  5191.8 1524.29  5335.1 1556.95  5423.6 1572.17
#Mann=3,-1,0
  4802.6    0.15       0  4981.2    0.05       0  5018.8    0.15       0
Bank Sta=4981.2,5018.8
XS Rating Curve= 0
Exp/Cntr=0.3,0.1

Type RM Length L Ch R = 1,154173,491,491,491
BEGIN DESCRIPTION:
Chauga River 308.0
END DESCRIPTION:
XS GIS Cut Line= 3
      1350047.18      1098752.85      1350165.86      1098863.41
      1350589.39      1099144.45
#Sta/Elev= 30
  4837.8 1514.82  4851.5 1512.29  4859.5 1512.91  4866.1 1506.99  4884.0 1500.26
  4927.5 1473.53  4928.3 1472.91  4931.5 1464.69  4938.2 1458.69  4947.7 1466.29
  4964.9 1451.57  4981.2 1449.03  4981.7 1448.03  5018.8 1449.03  5020.0 1451.50
  5023.9 1451.96  5041.4 1449.03  5052.1 1457.58  5093.2 1457.77  5098.4 1457.46
  5100.4 1454.73  5101.2 1457.54  5103.8 1458.67  5137.0 1459.56  5163.4 1464.52
  5237.9 1483.63  5279.0 1496.21  5314.1 1509.78  5358.5 1521.84  5508.3 1552.20
#Mann=3,-1,0
  4837.8    0.15       0  4981.2    0.05       0  5018.8    0.15       0
Bank Sta=4981.2,5018.8
XS Rating Curve= 0
Exp/Cntr=0.3,0.1

Type RM Length L Ch R = 1,153682,557,557,557
BEGIN DESCRIPTION:
Chauga River 307.0
END DESCRIPTION:
XS GIS Cut Line= 5
      1350031.52      1098726.90      1349847.74      1099154.71
      1349903.33      1099276.07      1350064.64      1099612.60
      1349975.00      1100075.00
#Sta/Elev= 30
  4400.9 1521.32  4456.3 1502.61  4497.9 1481.23  4508.7 1483.44  4512.8 1442.33
  4513.3 1460.55  4522.2 1464.03  4523.1 1472.90  4576.0 1462.55  4577.2 1448.93
  4577.3 1442.44  4586.6 1462.35  4726.6 1463.63  4953.3 1458.43  4977.6 1445.60
  4980.0 1451.68  4981.2 1442.33  4981.7 1441.33  5018.8 1442.33  5033.8 1457.66
  5089.9 1454.42  5092.0 1462.12  5210.8 1452.29  5216.3 1457.98  5240.1 1459.94
  5265.6 1456.15  5266.8 1471.00  5384.6 1499.75  5583.1 1497.11  5844.2 1531.67
#Mann=3,-1,0
  4400.9    0.15       0  4981.2    0.05       0  5018.8    0.15       0
Bank Sta=4981.2,5018.8
XS Rating Curve= 0
Exp/Cntr=0.3,0.1

Type RM Length L Ch R = 1,153125,486,486,486
BEGIN DESCRIPTION:
Chauga River 306.0
END DESCRIPTION:
XS GIS Cut Line= 3
      1350025.46      1098692.01      1349448.16      1099559.35
      1348877.76      1100005.40
#Sta/Elev= 30
  3958.1 1527.46  4045.2 1499.20  4055.6 1489.98  4081.7 1446.22  4082.2 1442.14
  4085.5 1448.94  4091.4 1474.05  4115.0 1460.40  4141.7 1460.05  4142.3 1456.68
  4142.5 1442.20  4143.8 1457.10  4144.9 1459.65  4151.8 1460.40  4657.9 1462.54
  4915.1 1459.53  4946.1 1456.91  4978.0 1445.77  4978.6 1441.30  4980.6 1441.30
  4981.1 1440.30  5019.4 1441.30  5022.5 1453.39  5031.9 1457.36  5061.3 1453.35
  5278.3 1458.52  5393.7 1456.51  5598.3 1516.39  5684.3 1536.26  5724.1 1538.78
#Mann=3,-1,0
  3958.1    0.15       0  4980.6    0.05       0  5019.4    0.15       0
Bank Sta=4980.6,5019.4
XS Rating Curve= 0
Exp/Cntr=0.3,0.1

Type RM Length L Ch R = 1,152639,639,639,639
BEGIN DESCRIPTION:
Chauga River 305.0
END DESCRIPTION:
XS GIS Cut Line= 4
      1350022.49      1098648.58      1349676.03      1099130.61
      1349446.91      1099090.05      1348784.35      1098895.64
#Sta/Elev= 30
  4173.7 1535.19  4261.8 1497.06  4297.8 1488.71  4321.5 1465.46  4323.5 1453.61
  4324.0 1442.00  4337.9 1464.68  4382.3 1456.44  4383.7 1448.16  4383.8 1442.06
  4384.6 1451.22  4384.7 1458.37  4533.1 1462.07  4878.8 1460.67  4976.7 1453.53
  4980.6 1441.30  4981.1 1440.30  5019.4 1441.30  5024.5 1449.43  5027.8 1442.05
  5029.2 1449.67  5055.1 1456.89  5177.4 1456.47  5336.2 1485.97  5489.8 1481.99
  5597.9 1498.94  5603.1 1507.87  5603.7 1517.34  5612.4 1500.49  5690.5 1509.92
#Mann=3,-1,0
  4173.7    0.15       0  4980.6    0.05       0  5019.4    0.15       0
Bank Sta=4980.6,5019.4
XS Rating Curve= 0
Exp/Cntr=0.3,0.1

Type RM Length L Ch R = 1,152000,500,500,500
BEGIN DESCRIPTION:
Chauga River 304.0
END DESCRIPTION:
XS GIS Cut Line= 3
      1349992.98      1098420.85      1349709.85      1098555.93
      1349158.48      1098685.97
#Sta/Elev= 30
  4686.3 1573.98  4753.2 1555.51  4800.1 1538.48  4875.5 1506.03  4937.3 1470.60
  4954.0 1458.33  4962.1 1444.31  4965.7 1441.30  4975.9 1445.05  4980.6 1441.30
  4981.1 1440.30  5019.4 1441.30  5019.7 1443.32  5027.5 1441.30  5030.6 1449.00
  5060.2 1450.72  5067.9 1453.25  5069.1 1450.41  5078.8 1449.41  5113.6 1452.97
  5172.2 1451.23  5259.6 1452.72  5263.3 1458.37  5264.4 1474.76  5271.2 1462.41
  5279.3 1454.27  5332.3 1456.61  5378.1 1464.90  5492.6 1474.56  5566.5 1489.24
#Mann=3,-1,0
  4686.3    0.15       0  4980.6    0.05       0  5019.4    0.15       0
Bank Sta=4980.6,5019.4
XS Rating Curve= 0
Exp/Cntr=0.3,0.1

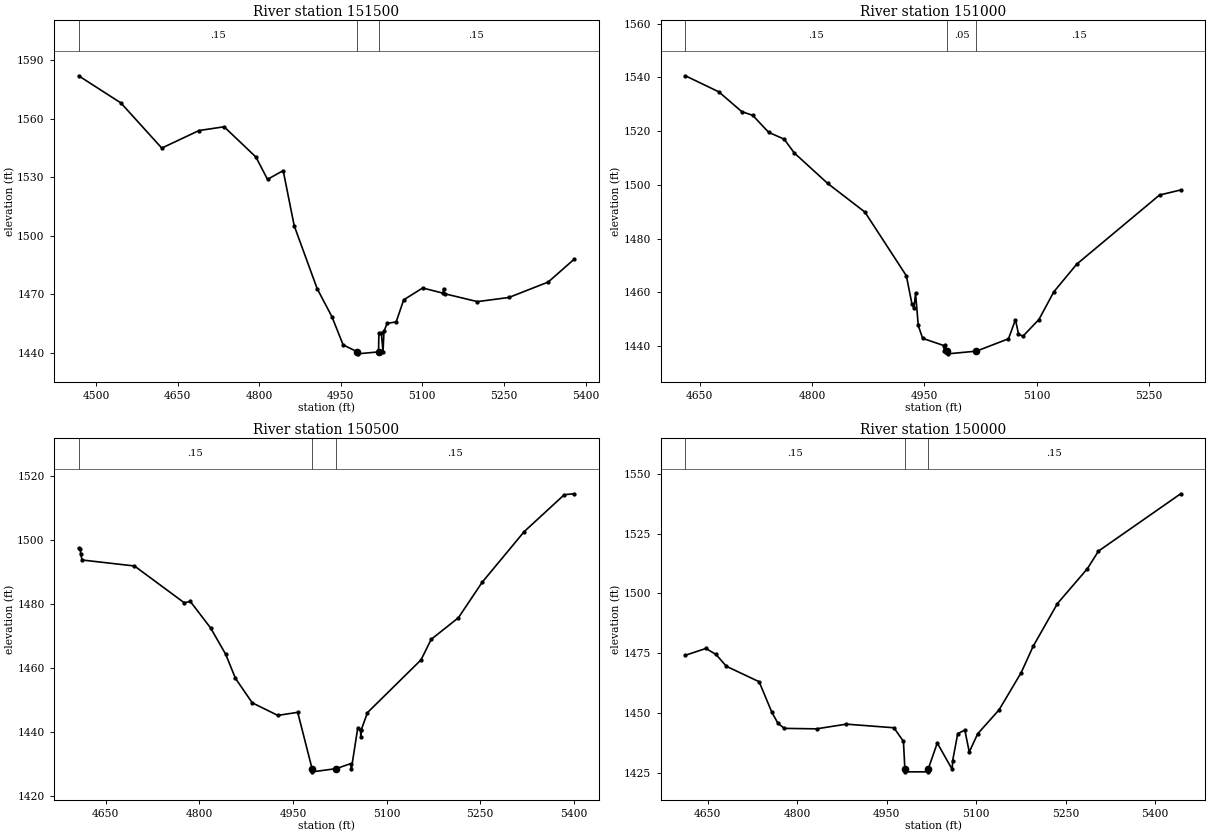
Type RM Length L Ch R = 1,151500,500,500,500
BEGIN DESCRIPTION:
Chauga River 303.0
END DESCRIPTION:
XS GIS Cut Line= 3
      1349774.98      1097775.02      1349408.25      1098160.42
      1349158.49      1098444.95
#Sta/Elev= 30
  4468.0 1582.06  4545.7 1568.13  4620.9 1544.97  4689.4 1553.97  4735.5 1555.90
  4794.0 1540.37  4815.3 1528.92  4844.1 1533.41  4864.4 1505.10  4906.6 1472.84
  4933.7 1458.49  4954.3 1444.02  4980.6 1440.41  4981.1 1439.41  5019.4 1440.41
  5020.1 1449.91  5024.5 1450.13  5027.7 1440.41  5029.4 1450.91  5035.2 1455.04
  5051.9 1455.79  5065.6 1467.09  5100.5 1473.19  5138.2 1470.53  5139.0 1472.86
  5140.8 1470.25  5201.2 1466.20  5259.0 1468.32  5331.4 1476.24  5378.6 1487.83
#Mann=3,-1,0
  4468.0    0.15       0  4980.6    0.05       0  5019.4    0.15       0
Bank Sta=4980.6,5019.4
XS Rating Curve= 0
Exp/Cntr=0.3,0.1

Type RM Length L Ch R = 1,151000,500,500,500
BEGIN DESCRIPTION:
Chauga River 302.0
END DESCRIPTION:
XS GIS Cut Line= 3
      1348750.01      1097931.06      1348962.77      1098232.42
      1349108.49      1098485.35
#Sta/Elev= 30
  4631.1 1540.63  4675.7 1534.65  4706.4 1527.27  4720.9 1525.92  4742.2 1519.58
  4762.9 1517.04  4776.4 1511.91  4820.9 1500.57  4870.6 1489.91  4925.9 1466.20
  4933.3 1455.83  4936.1 1454.05  4938.2 1459.74  4941.8 1447.68  4947.7 1442.89
  4976.3 1440.18  4976.6 1438.33  4977.6 1440.28  4980.6 1438.13  4981.1 1437.13
  5019.4 1438.13  5062.2 1442.74  5071.5 1449.83  5075.5 1444.62  5081.3 1443.64
  5102.8 1449.91  5122.7 1460.22  5153.3 1470.52  5263.7 1496.24  5291.9 1498.12
#Mann=3,-1,0
  4631.1    0.15       0  4980.6    0.05       0  5019.4    0.15       0
Bank Sta=4980.6,5019.4
XS Rating Curve= 0
Exp/Cntr=0.3,0.1

Type RM Length L Ch R = 1,150500,500,500,500
BEGIN DESCRIPTION:
Chauga River 301.0
END DESCRIPTION:
XS GIS Cut Line= 3
      1348373.43      1098187.09      1348563.94      1098531.51
      1348749.97      1098885.95
#Sta/Elev= 30
  4606.4 1497.26  4609.3 1497.17  4609.6 1495.57  4612.0 1493.64  4695.9 1491.78
  4775.6 1480.32  4785.5 1480.71  4818.0 1472.44  4842.2 1464.22  4857.8 1456.73
  4884.7 1449.10  4925.7 1445.17  4957.6 1446.13  4980.6 1428.57  4981.1 1427.57
  5019.4 1428.57  5042.7 1430.15  5043.7 1428.57  5053.9 1441.34  5058.4 1440.48
  5058.7 1438.44  5059.3 1440.58  5069.4 1446.04  5155.3 1462.50  5171.6 1468.91
  5215.2 1475.63  5253.2 1486.68  5320.7 1502.51  5384.9 1514.01  5400.3 1514.30
#Mann=3,-1,0
  4606.4    0.15       0  4980.6    0.05       0  5019.4    0.15       0
Bank Sta=4980.6,5019.4
XS Rating Curve= 0
Exp/Cntr=0.3,0.1

Type RM Length L Ch R = 1,150000,466,466,466
BEGIN DESCRIPTION:
Chauga River 300.0
END DESCRIPTION:
XS GIS Cut Line= 3
      1348017.96      1098364.83      1348110.03      1098741.03
      1348210.77      1099172.22
#Sta/Elev= 30
  4612.7 1474.22  4647.1 1477.07  4664.1 1474.54  4681.4 1469.62  4736.3 1463.18
  4757.6 1450.45  4767.9 1445.80  4778.6 1443.72  4832.5 1443.52  4882.5 1445.48
  4962.2 1443.97  4978.2 1438.30  4980.6 1426.58  4981.1 1425.58  5018.9 1425.58
  5019.4 1426.58  5034.9 1437.59  5059.9 1426.58  5060.6 1430.17  5069.2 1441.55
  5081.1 1442.98  5088.5 1433.85  5102.6 1441.45  5138.5 1451.46  5175.6 1467.01
  5195.5 1477.93  5236.3 1495.80  5286.5 1510.35  5305.1 1517.69  5442.8 1541.60
#Mann=3,-1,0
  4612.7    0.15       0  4980.6    0.05       0  5019.4    0.15       0
Bank Sta=4980.6,5019.4
XS Rating Curve= 0
Exp/Cntr=0.3,0.1