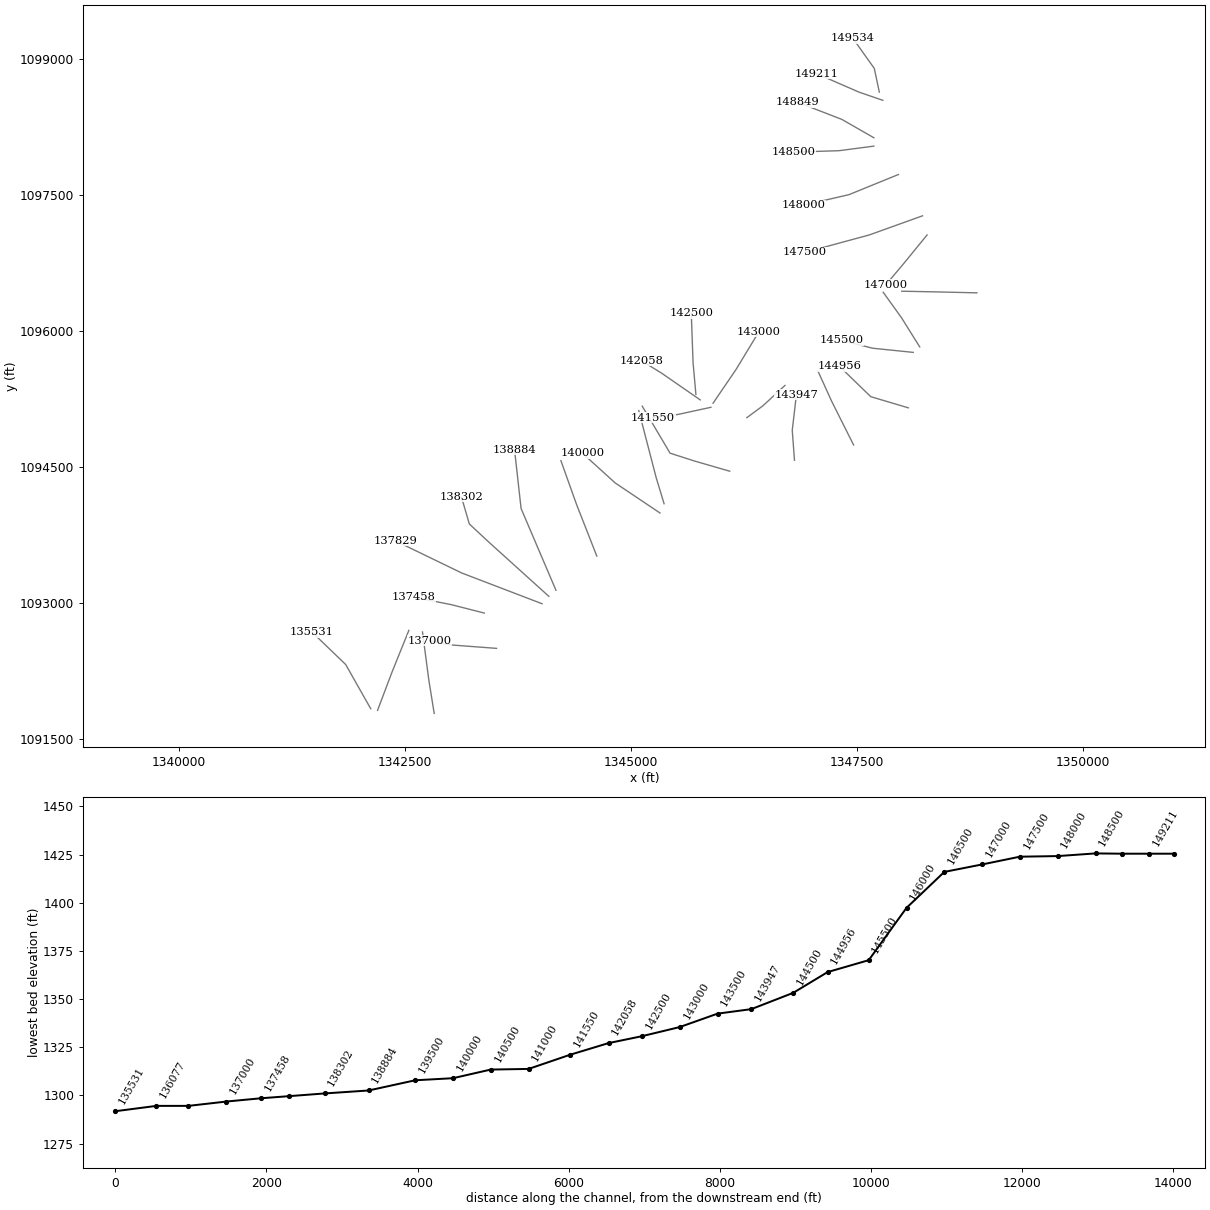
HEC-RAS study Chauga River.prj: Chauga River Limited Detail Study

--- Chauga River.g01 (geometry) --- (continued)

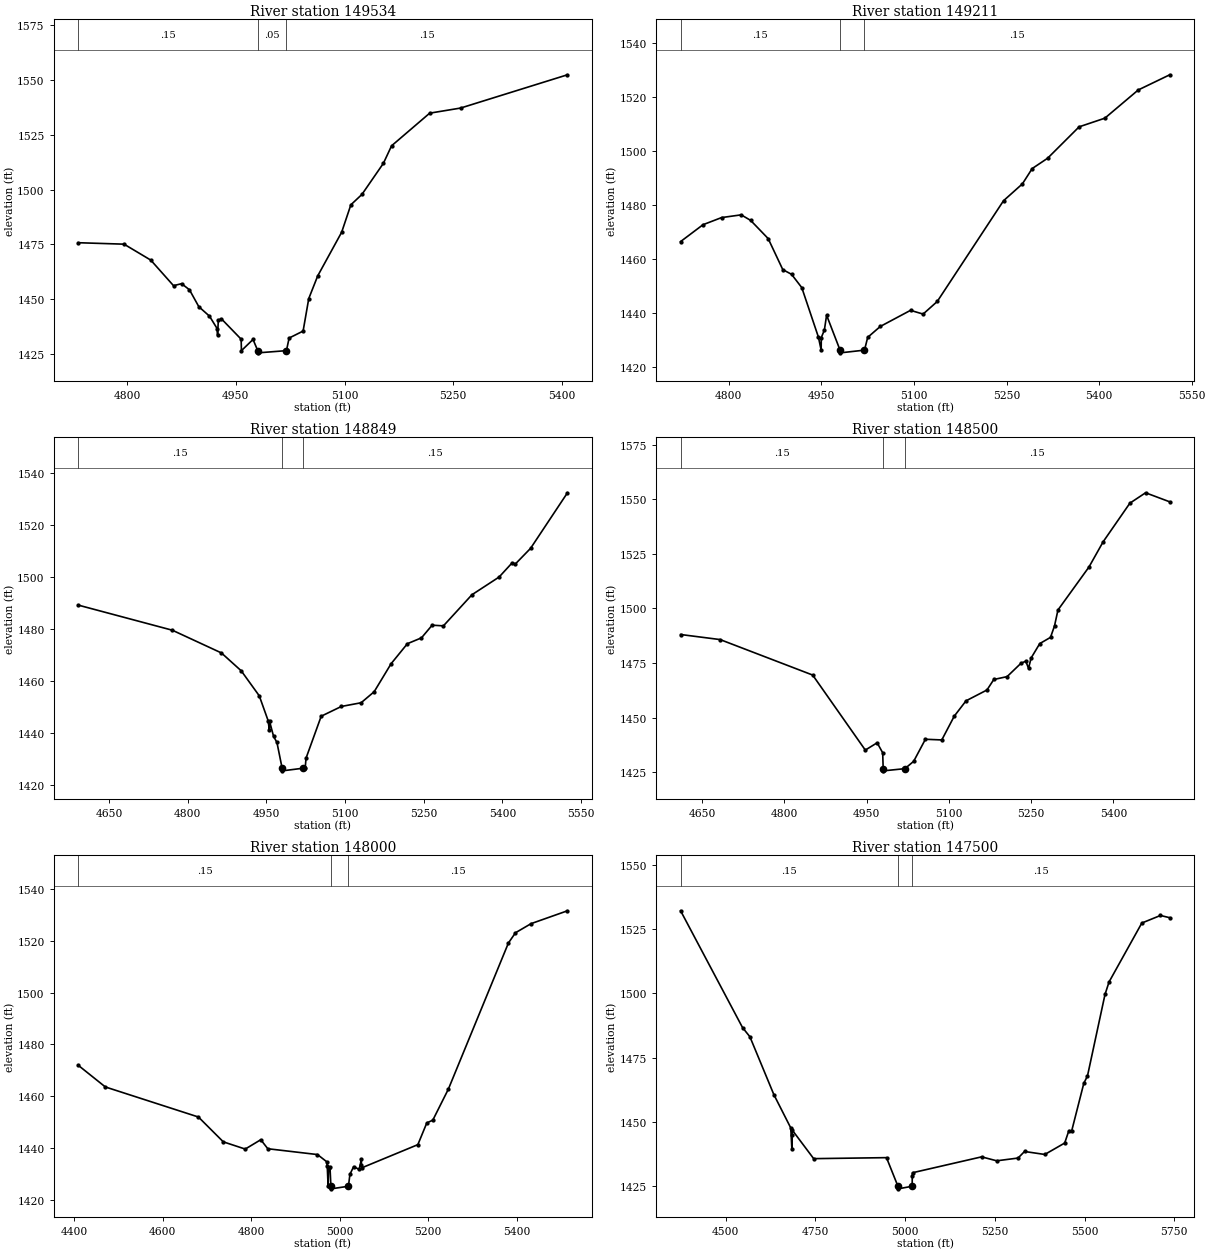
Type RM Length L Ch R = 1,149534,323,323,323
BEGIN DESCRIPTION:
Chauga River 299.5
END DESCRIPTION:
XS GIS Cut Line= 3
      1347746.82      1098639.01      1347691.39      1098900.61
      1347454.64      1099232.40
#Sta/Elev= 30
  4732.6 1475.71  4795.7 1475.05  4832.6 1467.77  4864.0 1456.09  4875.1 1457.01
  4886.0 1454.21  4898.9 1446.49  4913.6 1442.18  4924.2 1436.48  4924.8 1433.43
  4925.8 1440.36  4930.1 1440.94  4957.3 1431.65  4957.7 1426.42  4973.7 1431.54
  4980.2 1426.42  4980.7 1425.42  5019.8 1426.42  5023.5 1432.18  5042.8 1435.36
  5050.6 1450.21  5063.0 1460.59  5096.0 1480.50  5108.7 1493.02  5124.0 1497.78
  5153.6 1511.98  5164.9 1519.98  5217.5 1534.88  5260.1 1537.21  5407.6 1552.41
#Mann=3,-1,0
  4732.6    0.15       0  4980.2    0.05       0  5019.8    0.15       0
Bank Sta=4980.2,5019.8
XS Rating Curve= 0
Exp/Cntr=0.3,0.1

Type RM Length L Ch R = 1,149211,362,362,362
BEGIN DESCRIPTION:
Chauga River 299.0
END DESCRIPTION:
XS GIS Cut Line= 3
      1347786.04      1098548.58      1347522.89      1098638.86
      1347050.98      1098843.81
#Sta/Elev= 30
  4721.8 1466.58  4758.1 1472.82  4788.2 1475.46  4820.0 1476.47  4835.3 1474.42
  4863.7 1467.69  4887.4 1456.21  4901.6 1454.47  4918.2 1449.54  4945.1 1431.27
  4949.6 1426.42  4949.8 1431.08  4954.8 1433.84  4958.4 1439.34  4980.2 1426.42
  4980.7 1425.42  5019.8 1426.42  5025.0 1431.15  5045.4 1435.18  5094.4 1441.14
  5114.8 1439.76  5137.7 1444.42  5245.1 1481.69  5275.7 1487.93  5291.6 1493.60
  5316.5 1497.40  5367.6 1509.03  5409.3 1512.23  5463.5 1522.68  5514.5 1528.29
#Mann=3,-1,0
  4721.8    0.15       0  4980.2    0.05       0  5019.8    0.15       0
Bank Sta=4980.2,5019.8
XS Rating Curve= 0
Exp/Cntr=0.3,0.1

Type RM Length L Ch R = 1,148849,349,349,349
BEGIN DESCRIPTION:
Chauga River 298.0
END DESCRIPTION:
XS GIS Cut Line= 3
      1347686.62      1098135.86      1347332.03      1098338.48
      1346843.09      1098527.50
#Sta/Elev= 30
  4591.6 1489.21  4770.9 1479.55  4864.4 1470.81  4902.2 1463.93  4936.6 1454.30
  4953.5 1444.73  4955.9 1440.98  4956.3 1444.44  4963.9 1438.66  4970.3 1436.36
  4980.2 1426.42  4980.7 1425.42  5019.8 1426.42  5024.1 1426.42  5025.8 1430.31
  5054.7 1446.45  5093.1 1450.20  5130.8 1451.63  5155.7 1455.88  5188.0 1466.67
  5219.0 1474.36  5245.9 1476.62  5266.2 1481.49  5287.7 1481.23  5342.1 1493.21
  5393.9 1500.03  5418.7 1505.48  5425.0 1505.08  5453.9 1511.08  5524.2 1532.46
#Mann=3,-1,0
  4591.6    0.15       0  4980.2    0.05       0  5019.8    0.15       0
Bank Sta=4980.2,5019.8
XS Rating Curve= 0
Exp/Cntr=0.3,0.1

Type RM Length L Ch R = 1,148500,500,500,500
BEGIN DESCRIPTION:
Chauga River 297.0
END DESCRIPTION:
XS GIS Cut Line= 3
      1347686.56      1098043.70      1347300.56      1097993.15
      1346797.91      1097977.43
#Sta/Elev= 30
  4610.7 1488.04  4682.8 1485.72  4851.6 1469.46  4947.6 1435.08  4969.2 1438.43
  4979.3 1433.85  4980.2 1426.57  4980.7 1425.57  5019.8 1426.57  5035.8 1429.93
  5057.2 1440.04  5087.1 1439.73  5109.9 1450.65  5131.3 1457.65  5169.5 1462.62
  5182.0 1467.43  5206.2 1468.74  5231.5 1474.85  5240.3 1475.83  5245.3 1472.55
  5250.1 1477.31  5265.8 1483.88  5285.4 1486.73  5292.7 1491.98  5299.0 1499.29
  5355.5 1518.95  5381.4 1530.53  5430.2 1548.23  5458.8 1552.99  5502.9 1548.84
#Mann=3,-1,0
  4610.7    0.15       0  4980.2    0.05       0  5019.8    0.15       0
Bank Sta=4980.2,5019.8
XS Rating Curve= 0
Exp/Cntr=0.3,0.1

Type RM Length L Ch R = 1,148000,500,500,500
BEGIN DESCRIPTION:
Chauga River 296.0
END DESCRIPTION:
XS GIS Cut Line= 3
      1347957.68      1097730.39      1347410.83      1097508.10
      1346909.37      1097393.01
#Sta/Elev= 30
  4409.7 1471.88  4470.8 1463.53  4681.0 1451.92  4737.2 1442.33  4786.7 1439.54
  4821.8 1443.15  4837.7 1439.67  4949.9 1437.42  4970.3 1434.71  4971.9 1433.17
  4973.9 1425.18  4975.0 1432.07  4978.1 1432.66  4980.2 1425.18  4980.7 1424.18
  5019.8 1425.18  5023.2 1429.82  5031.6 1432.76  5044.1 1431.67  5049.0 1435.55
  5049.1 1433.52  5050.2 1432.31  5176.6 1441.25  5196.8 1449.64  5210.4 1450.72
  5245.5 1462.69  5381.2 1519.15  5397.1 1523.09  5432.3 1526.61  5514.5 1531.58
#Mann=3,-1,0
  4409.7    0.15       0  4980.2    0.05       0  5019.8    0.15       0
Bank Sta=4980.2,5019.8
XS Rating Curve= 0
Exp/Cntr=0.3,0.1

Type RM Length L Ch R = 1,147500,500,500,500
BEGIN DESCRIPTION:
Chauga River 295.0
END DESCRIPTION:
XS GIS Cut Line= 3
      1348225.01      1097275.00      1347636.35      1097064.10
      1346924.45      1096871.85
#Sta/Elev= 30
  4374.7 1532.18  4547.3 1486.67  4567.7 1483.12  4634.6 1460.54  4681.7 1447.57
  4684.7 1439.22  4685.1 1444.80  4685.9 1446.72  4745.4 1435.63  4948.3 1436.02
  4980.2 1424.87  4980.7 1423.87  5019.8 1424.87  5020.1 1428.99  5020.8 1430.14
  5213.3 1436.33  5255.3 1434.79  5314.8 1435.86  5332.8 1438.42  5389.3 1437.26
  5444.7 1441.71  5456.3 1446.51  5464.3 1446.49  5498.0 1464.99  5508.2 1467.85
  5557.0 1499.58  5568.3 1504.46  5659.6 1527.41  5711.5 1530.35  5737.4 1529.48
#Mann=3,-1,0
  4374.7    0.15       0  4980.2    0.05       0  5019.8    0.15       0
Bank Sta=4980.2,5019.8
XS Rating Curve= 0
Exp/Cntr=0.3,0.1

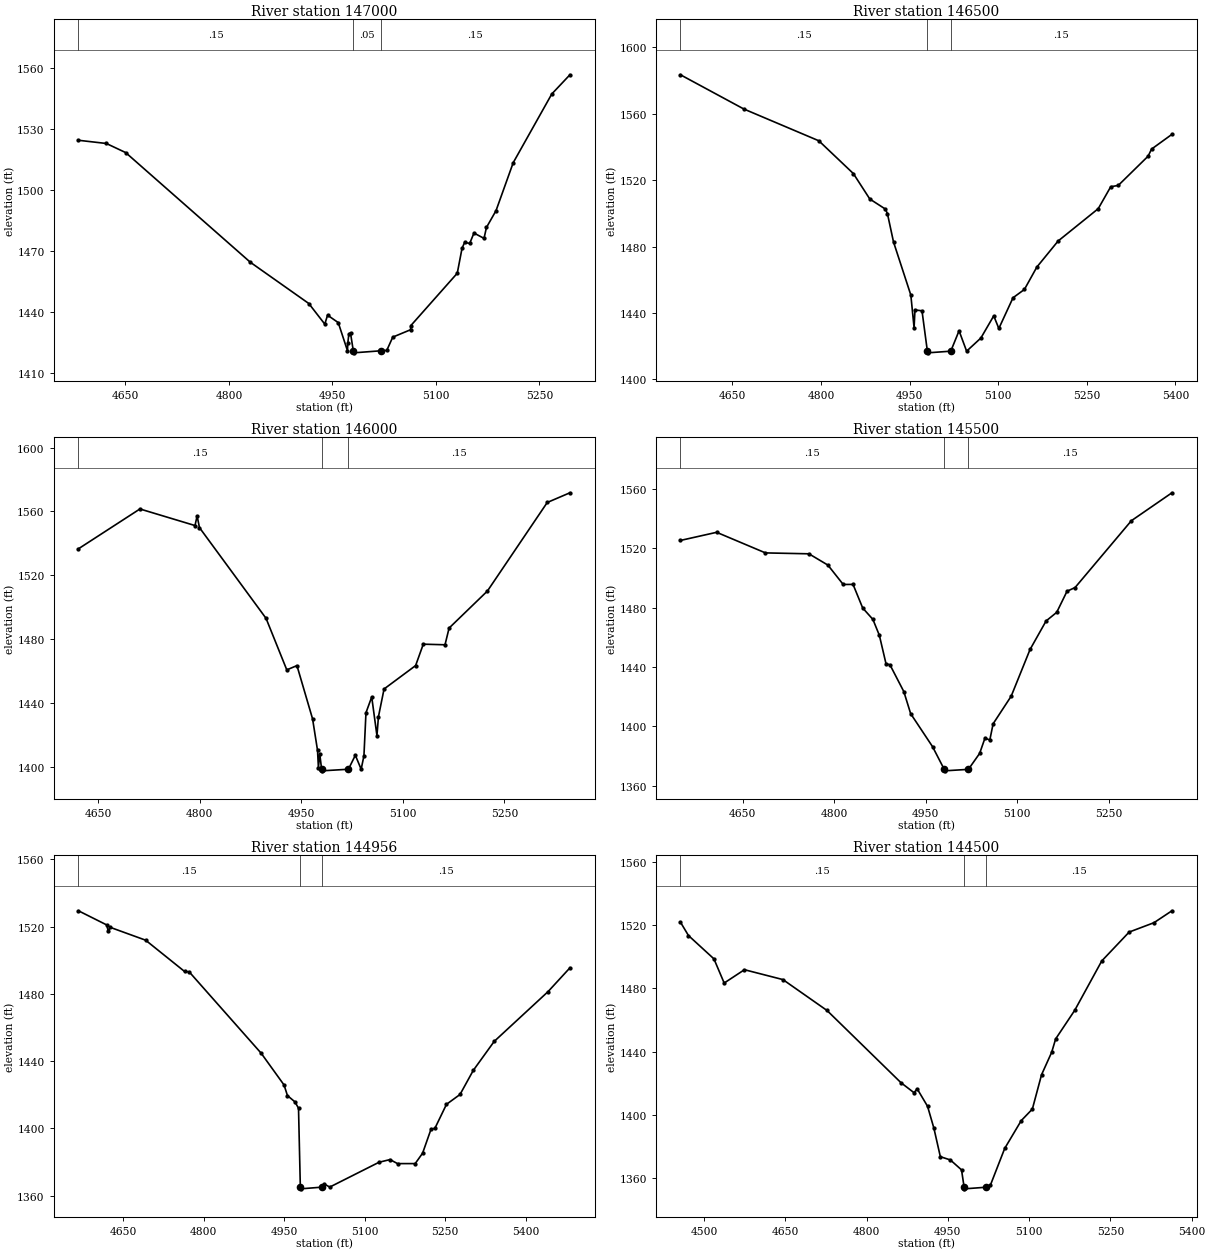
Type RM Length L Ch R = 1,147000,500,500,500
BEGIN DESCRIPTION:
Chauga River 294.0
END DESCRIPTION:
XS GIS Cut Line= 3
      1348275.20      1097064.01      1348010.07      1096740.59
      1347820.33      1096515.75
#Sta/Elev= 30
  4581.8 1524.28  4622.2 1522.71  4650.3 1518.23  4831.1 1464.31  4915.7 1444.08
  4938.9 1433.94  4942.9 1438.35  4958.4 1434.69  4971.8 1420.84  4972.2 1424.50
  4973.8 1429.18  4976.2 1429.49  4980.2 1420.84  4980.7 1419.84  5019.8 1420.84
  5028.7 1421.02  5037.4 1427.56  5063.2 1431.19  5063.6 1433.22  5130.9 1458.95
  5137.8 1471.17  5141.6 1474.14  5148.9 1473.58  5155.1 1478.70  5169.7 1476.08
  5173.2 1481.43  5187.1 1489.71  5212.0 1513.27  5267.9 1547.02  5294.2 1556.46
#Mann=3,-1,0
  4581.8    0.15       0  4980.2    0.05       0  5019.8    0.15       0
Bank Sta=4980.2,5019.8
XS Rating Curve= 0
Exp/Cntr=0.3,0.1

Type RM Length L Ch R = 1,146500,500,500,500
BEGIN DESCRIPTION:
Chauga River 293.0
END DESCRIPTION:
XS GIS Cut Line= 3
      1348826.49      1096425.40      1348389.01      1096435.69
      1347995.09      1096443.47
#Sta/Elev= 30
  4562.4 1583.49  4669.7 1562.86  4796.5 1543.73  4855.0 1523.96  4882.8 1508.64
  4909.1 1502.59  4912.6 1499.85  4922.9 1482.77  4952.2 1450.78  4957.7 1431.11
  4959.2 1441.82  4971.1 1441.29  4980.2 1416.97  4980.7 1415.97  5019.8 1416.97
  5033.8 1429.26  5046.6 1416.97  5070.7 1424.89  5092.5 1438.25  5101.1 1430.65
  5125.1 1449.15  5144.4 1454.17  5165.4 1467.63  5201.4 1483.34  5269.3 1502.83
  5290.4 1516.03  5303.2 1516.84  5353.7 1534.46  5359.5 1538.72  5394.0 1547.60
#Mann=3,-1,0
  4562.4    0.15       0  4980.2    0.05       0  5019.8    0.15       0
Bank Sta=4980.2,5019.8
XS Rating Curve= 0
Exp/Cntr=0.3,0.1

Type RM Length L Ch R = 1,146000,500,500,500
BEGIN DESCRIPTION:
Chauga River 292.0
END DESCRIPTION:
XS GIS Cut Line= 3
      1348193.87      1095828.95      1347992.74      1096149.94
      1347790.20      1096431.45
#Sta/Elev= 30
  4621.2 1536.56  4712.0 1561.54  4793.3 1551.14  4796.4 1557.14  4799.9 1549.83
  4898.2 1492.94  4928.8 1460.64  4943.8 1463.32  4966.9 1429.86  4974.2 1410.11
  4975.5 1399.28  4977.4 1408.20  4980.2 1398.33  4980.7 1397.33  5019.8 1398.33
  5030.0 1407.10  5038.6 1398.33  5042.7 1406.77  5045.7 1433.77  5054.2 1443.66
  5061.9 1419.39  5064.1 1431.24  5072.4 1448.65  5119.0 1463.34  5130.3 1476.75
  5162.4 1476.38  5168.4 1486.85  5225.0 1510.09  5313.3 1565.60  5346.8 1571.69
#Mann=3,-1,0
  4621.2    0.15       0  4980.2    0.05       0  5019.8    0.15       0
Bank Sta=4980.2,5019.8
XS Rating Curve= 0
Exp/Cntr=0.3,0.1

Type RM Length L Ch R = 1,145500,544,544,544
BEGIN DESCRIPTION:
Chauga River 291.0
END DESCRIPTION:
XS GIS Cut Line= 3
      1348122.15      1095768.68      1347672.50      1095814.76
      1347329.94      1095901.21
#Sta/Elev= 30
  4548.0 1525.11  4607.3 1530.58  4687.3 1516.73  4758.5 1516.12  4789.6 1508.53
  4814.7 1495.50  4830.8 1495.54  4846.6 1479.68  4863.3 1472.03  4873.9 1461.33
  4884.8 1442.20  4891.3 1441.46  4914.0 1423.46  4925.2 1408.62  4961.1 1386.41
  4980.2 1371.18  4980.7 1370.18  5019.8 1371.18  5038.2 1381.88  5046.9 1392.16
  5054.9 1390.94  5060.3 1401.82  5089.9 1420.37  5120.8 1451.78  5147.1 1470.97
  5164.5 1476.76  5181.4 1490.95  5194.6 1493.44  5286.8 1538.36  5353.3 1557.16
#Mann=3,-1,0
  4548.0    0.15       0  4980.2    0.05       0  5019.8    0.15       0
Bank Sta=4980.2,5019.8
XS Rating Curve= 0
Exp/Cntr=0.3,0.1

Type RM Length L Ch R = 1,144956,456,456,456
BEGIN DESCRIPTION:
Chauga River 290.0
END DESCRIPTION:
XS GIS Cut Line= 3
      1348068.01      1095157.13      1347652.52      1095280.11
      1347305.78      1095615.06
#Sta/Elev= 30
  4566.7 1529.44  4619.3 1521.03  4622.4 1517.17  4625.7 1519.61  4691.8 1511.95
  4764.4 1493.32  4772.9 1493.14  4907.0 1444.71  4949.7 1425.78  4956.0 1419.47
  4969.8 1415.79  4976.6 1411.99  4980.0 1365.00  4980.5 1364.00  5020.0 1365.00
  5024.5 1366.87  5034.8 1365.05  5126.6 1379.82  5147.1 1381.41  5161.0 1379.01
  5193.9 1379.02  5207.7 1385.21  5223.4 1399.49  5230.5 1399.93  5252.2 1414.29
  5277.4 1420.14  5302.0 1434.43  5341.0 1451.70  5441.3 1481.32  5482.1 1495.49
#Mann=3,-1,0
  4566.7    0.15       0  4980.0    0.05       0  5020.0    0.15       0
Bank Sta=4980,5020
XS Rating Curve= 0
Exp/Cntr=0.3,0.1

Type RM Length L Ch R = 1,144500,553,553,553
BEGIN DESCRIPTION:
Chauga River 289.0
END DESCRIPTION:
XS GIS Cut Line= 3
      1347462.46      1094747.43      1347218.11      1095232.90
      1347067.80      1095563.87
#Sta/Elev= 30
  4456.5 1521.95  4471.3 1513.48  4518.3 1498.72  4537.2 1483.43  4574.6 1491.86
  4645.6 1485.61  4727.0 1466.06  4863.5 1420.36  4887.5 1414.05  4893.4 1416.47
  4912.5 1405.44  4924.2 1391.58  4936.1 1373.56  4954.6 1371.49  4975.2 1365.21
  4980.0 1354.21  4980.5 1353.21  5020.0 1354.21  5028.6 1355.64  5054.9 1378.80
  5085.4 1396.38  5105.9 1403.67  5122.9 1425.43  5141.5 1439.56  5148.9 1448.07
  5184.1 1466.17  5234.0 1497.41  5284.5 1515.67  5330.3 1521.60  5363.5 1529.15
#Mann=3,-1,0
  4456.5    0.15       0  4980.0    0.05       0  5020.0    0.15       0
Bank Sta=4980,5020
XS Rating Curve= 0
Exp/Cntr=0.3,0.1

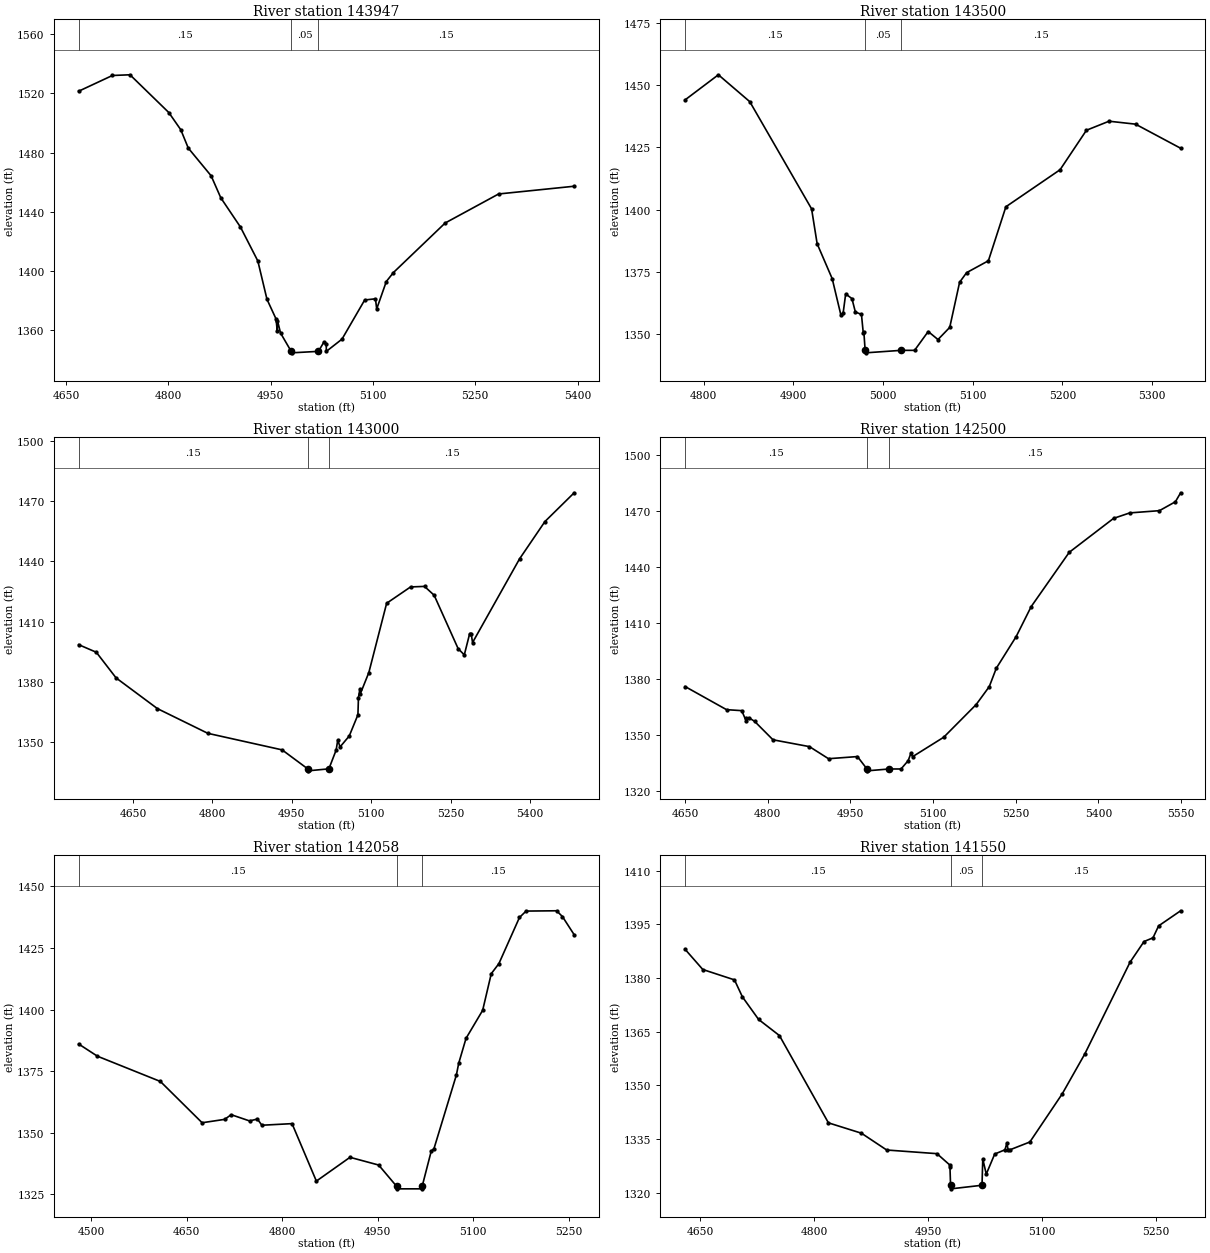
Type RM Length L Ch R = 1,143947,447,447,447
BEGIN DESCRIPTION:
Chauga River 288.0
END DESCRIPTION:
XS GIS Cut Line= 3
      1346808.75      1094578.69      1346783.89      1094909.46
      1346829.84      1095301.78
#Sta/Elev= 30
  4668.3 1521.44  4717.8 1532.07  4743.6 1532.55  4800.5 1507.07  4818.1 1495.44
  4829.1 1483.04  4862.6 1464.34  4876.8 1449.46  4905.6 1429.73  4931.1 1406.81
  4944.5 1380.94  4957.8 1367.66  4959.6 1359.41  4959.9 1366.56  4964.4 1358.15
  4980.0 1345.78  4980.5 1344.78  5020.0 1345.78  5027.9 1351.99  5031.4 1351.00
  5031.6 1345.78  5054.5 1354.02  5087.8 1380.47  5103.6 1381.27  5105.4 1374.43
  5119.5 1392.93  5130.0 1399.03  5205.8 1432.45  5284.2 1452.06  5395.0 1457.28
#Mann=3,-1,0
  4668.3    0.15       0  4980.0    0.05       0  5020.0    0.15       0
Bank Sta=4980,5020
XS Rating Curve= 0
Exp/Cntr=0.3,0.1

Type RM Length L Ch R = 1,143500,500,500,500
BEGIN DESCRIPTION:
Chauga River 287.0
END DESCRIPTION:
XS GIS Cut Line= 3
      1346281.55      1095048.68      1346459.24      1095179.59
      1346703.33      1095404.19
#Sta/Elev= 30
  4779.3 1444.04  4816.4 1454.12  4851.4 1443.32  4920.3 1400.27  4926.5 1386.25
  4943.3 1372.21  4952.9 1357.73  4955.5 1358.47  4958.3 1366.10  4965.3 1364.22
  4969.1 1358.84  4975.9 1357.87  4977.9 1350.43  4978.6 1350.65  4980.0 1343.44
  4980.5 1342.44  5020.0 1343.44  5035.1 1343.44  5050.3 1351.00  5061.2 1347.78
  5074.3 1352.66  5085.3 1370.78  5093.1 1374.64  5117.4 1379.42  5136.9 1401.11
  5197.3 1415.98  5226.7 1431.84  5251.9 1435.47  5281.4 1434.29  5331.7 1424.61
#Mann=3,-1,0
  4779.3    0.15       0  4980.0    0.05       0  5020.0    0.15       0
Bank Sta=4980,5020
XS Rating Curve= 0
Exp/Cntr=0.3,0.1

Type RM Length L Ch R = 1,143000,500,500,500
BEGIN DESCRIPTION:
Chauga River 286.0
END DESCRIPTION:
XS GIS Cut Line= 3
      1345908.00      1095208.33      1346163.37      1095581.76
      1346414.10      1095994.58
#Sta/Elev= 30
  4547.6 1398.46  4581.0 1394.66  4618.3 1381.86  4696.3 1366.54  4791.5 1354.20
  4931.7 1345.94  4980.0 1336.48  4980.5 1335.48  5020.0 1336.48  5033.7 1345.85
  5036.7 1350.80  5041.1 1347.42  5058.4 1352.86  5074.8 1363.46  5075.8 1372.00
  5078.4 1376.21  5079.1 1373.77  5095.4 1384.53  5129.0 1419.11  5174.2 1427.27
  5200.5 1427.53  5218.7 1423.12  5264.0 1396.45  5275.6 1393.36  5285.8 1404.02
  5288.6 1403.91  5291.2 1399.51  5379.8 1441.23  5427.8 1459.90  5483.0 1474.26
#Mann=3,-1,0
  4547.6    0.15       0  4980.0    0.05       0  5020.0    0.15       0
Bank Sta=4980,5020
XS Rating Curve= 0
Exp/Cntr=0.3,0.1

Type RM Length L Ch R = 1,142500,442,442,442
BEGIN DESCRIPTION:
Chauga River 285.0
END DESCRIPTION:
XS GIS Cut Line= 3
      1345718.22      1095304.79      1345687.01      1095653.49
      1345667.02      1096202.43
#Sta/Elev= 30
  4649.9 1375.98  4725.1 1363.57  4752.7 1363.04  4760.9 1357.38  4761.1 1359.04
  4765.6 1359.24  4776.1 1357.29  4809.4 1347.40  4875.6 1343.73  4910.2 1337.25
  4962.7 1338.40  4980.0 1331.74  4980.5 1330.74  5020.0 1331.74  5041.8 1331.74
  5054.8 1336.21  5059.8 1340.22  5062.7 1338.32  5119.3 1348.77  5178.2 1366.31
  5202.0 1375.95  5214.7 1385.78  5250.8 1402.80  5278.0 1418.86  5347.1 1448.01
  5427.6 1466.23  5457.0 1469.16  5510.8 1470.36  5539.8 1475.14  5549.3 1479.96
#Mann=3,-1,0
  4649.9    0.15       0  4980.0    0.05       0  5020.0    0.15       0
Bank Sta=4980,5020
XS Rating Curve= 0
Exp/Cntr=0.3,0.1

Type RM Length L Ch R = 1,142058,508,508,508
BEGIN DESCRIPTION:
Chauga River 284.0
END DESCRIPTION:
XS GIS Cut Line= 3
      1345766.47      1095244.48      1345339.04      1095539.58
      1345118.78      1095675.26
#Sta/Elev= 30
  4480.6 1386.01  4510.1 1381.05  4609.0 1370.78  4674.5 1354.01  4710.0 1355.39
  4720.1 1357.29  4749.0 1354.75  4761.3 1355.52  4768.3 1353.00  4815.7 1353.65
  4853.9 1330.30  4906.7 1339.97  4951.7 1336.83  4980.0 1328.16  4980.5 1327.16
  5019.5 1327.16  5020.0 1328.16  5034.3 1342.52  5038.5 1343.43  5073.7 1373.37
  5077.4 1378.18  5088.9 1388.30  5115.0 1399.68  5128.5 1414.57  5140.5 1418.66
  5172.8 1437.41  5183.2 1440.01  5231.1 1440.13  5240.3 1437.77  5258.7 1430.40
#Mann=3,-1,0
  4480.6    0.15       0  4980.0    0.05       0  5020.0    0.15       0
Bank Sta=4980,5020
XS Rating Curve= 0
Exp/Cntr=0.3,0.1

Type RM Length L Ch R = 1,141550,550,550,550
BEGIN DESCRIPTION:
Chauga River 283.0
END DESCRIPTION:
XS GIS Cut Line= 3
      1345884.53      1095163.17      1345522.73      1095084.73
      1345242.85      1095048.69
#Sta/Elev= 30
  4629.8 1388.05  4653.1 1382.41  4694.8 1379.51  4705.2 1374.78  4726.6 1368.45
  4754.0 1363.95  4818.5 1339.56  4861.9 1336.67  4895.2 1331.97  4961.4 1330.95
  4978.1 1327.81  4978.5 1327.21  4979.3 1322.12  4979.8 1321.12  5020.7 1322.12
  5021.7 1329.48  5026.3 1325.23  5037.4 1330.84  5051.0 1332.04  5053.3 1333.87
  5055.1 1332.07  5058.1 1332.08  5083.7 1334.21  5126.3 1347.66  5156.0 1358.80
  5215.6 1384.45  5234.0 1390.23  5245.8 1391.26  5253.2 1394.60  5282.2 1398.82
#Mann=3,-1,0
  4629.8    0.15       0  4979.3    0.05       0  5020.7    0.15       0
Bank Sta=4979.3,5020.7
XS Rating Curve= 0
Exp/Cntr=0.3,0.1

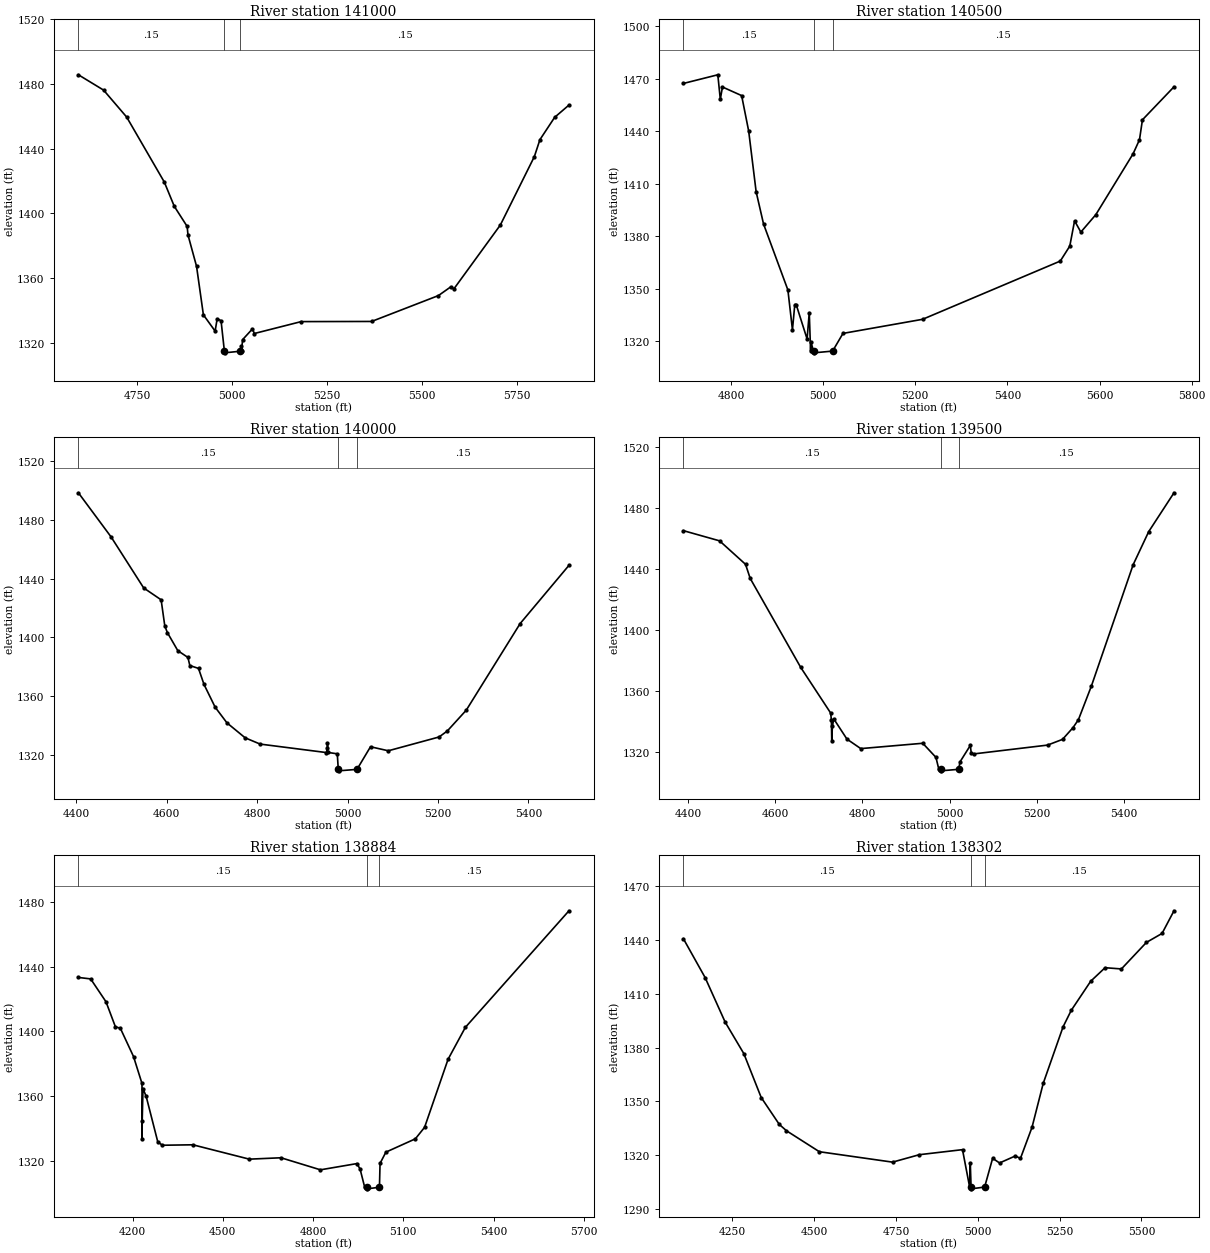
Type RM Length L Ch R = 1,141000,500,500,500
BEGIN DESCRIPTION:
Chauga River 282.0
END DESCRIPTION:
XS GIS Cut Line= 4
      1346092.41      1094458.23      1345703.17      1094570.47
      1345432.64      1094657.07      1345124.98      1095175.04
#Sta/Elev= 30
  4594.9 1485.75  4661.3 1476.26  4722.0 1459.60  4821.1 1419.40  4847.4 1404.38
  4881.3 1391.93  4883.4 1386.72  4906.0 1367.27  4924.0 1337.27  4954.9 1327.21
  4960.3 1334.85  4970.5 1333.65  4979.3 1314.76  4979.8 1313.76  5020.7 1314.76
  5024.1 1318.14  5024.6 1314.78  5027.1 1321.88  5053.2 1328.58  5058.2 1325.72
  5181.5 1333.08  5366.9 1333.17  5542.8 1349.18  5575.6 1354.63  5583.6 1353.35
  5705.7 1392.79  5795.4 1435.17  5810.0 1445.62  5848.8 1459.43  5886.5 1467.03
#Mann=3,-1,0
  4594.9    0.15       0  4979.3    0.05       0  5020.7    0.15       0
Bank Sta=4979.3,5020.7
XS Rating Curve= 0
Exp/Cntr=0.3,0.1

Type RM Length L Ch R = 1,140500,500,500,500
BEGIN DESCRIPTION:
Chauga River 281.0
END DESCRIPTION:
XS GIS Cut Line= 3
      1345366.36      1094099.77      1345278.25      1094389.89
      1345086.22      1095126.98
#Sta/Elev= 30
  4696.8 1467.27  4771.5 1472.22  4776.9 1458.22  4781.6 1465.24  4823.2 1460.33
  4838.5 1440.08  4854.7 1405.39  4870.8 1386.97  4923.6 1349.34  4933.5 1326.60
  4938.6 1341.00  4941.9 1340.75  4965.3 1321.32  4970.0 1336.42  4972.9 1314.43
  4973.7 1319.55  4979.3 1314.43  4979.8 1313.43  5020.7 1314.43  5043.2 1324.53
  5216.0 1332.58  5514.9 1365.84  5535.5 1374.39  5545.9 1388.82  5559.5 1382.38
  5592.0 1392.34  5672.9 1427.09  5686.8 1435.13  5693.2 1446.51  5761.7 1465.35
#Mann=3,-1,0
  4696.8    0.15       0  4979.3    0.05       0  5020.7    0.15       0
Bank Sta=4979.3,5020.7
XS Rating Curve= 0
Exp/Cntr=0.3,0.1

Type RM Length L Ch R = 1,140000,500,500,500
BEGIN DESCRIPTION:
Chauga River 280.0
END DESCRIPTION:
XS GIS Cut Line= 3
      1345321.18      1093997.34      1344825.94      1094328.57
      1344462.63      1094657.06
#Sta/Elev= 30
  4404.2 1498.56  4476.7 1468.40  4548.7 1433.66  4587.3 1425.57  4595.4 1407.79
  4601.1 1403.23  4624.2 1390.90  4646.6 1386.28  4650.8 1380.76  4670.0 1378.80
  4682.2 1367.86  4706.8 1352.37  4732.9 1341.68  4773.2 1331.47  4806.4 1327.19
  4953.1 1321.41  4955.3 1324.63  4955.4 1328.11  4955.9 1321.53  4977.1 1320.55
  4979.3 1309.95  4979.8 1308.95  5020.7 1309.95  5050.6 1325.37  5090.0 1322.63
  5202.4 1332.04  5220.6 1336.14  5262.5 1350.32  5381.7 1409.36  5489.8 1449.09
#Mann=3,-1,0
  4404.2    0.15       0  4979.3    0.05       0  5020.7    0.15       0
Bank Sta=4979.3,5020.7
XS Rating Curve= 0
Exp/Cntr=0.3,0.1

Type RM Length L Ch R = 1,139500,616,616,616
BEGIN DESCRIPTION:
Chauga River 279.0
END DESCRIPTION:
XS GIS Cut Line= 3
      1344622.30      1093521.93      1344398.76      1094090.25
      1344224.98      1094575.04
#Sta/Elev= 30
  4389.3 1465.37  4472.3 1458.69  4531.9 1443.29  4542.6 1434.04  4658.3 1375.79
  4727.1 1345.82  4728.9 1341.30  4729.7 1327.69  4731.1 1337.00  4734.3 1341.95
  4764.6 1328.67  4796.3 1322.45  4938.5 1325.95  4968.8 1316.69  4975.4 1308.87
  4979.3 1308.87  4979.8 1307.87  5020.7 1308.87  5024.3 1313.88  5047.6 1324.52
  5049.9 1319.33  5055.7 1318.97  5224.9 1324.75  5259.2 1328.50  5283.2 1336.17
  5295.7 1341.40  5325.5 1363.50  5421.3 1443.05  5457.0 1464.75  5515.0 1490.21
#Mann=3,-1,0
  4389.3    0.15       0  4979.3    0.05       0  5020.7    0.15       0
Bank Sta=4979.3,5020.7
XS Rating Curve= 0
Exp/Cntr=0.3,0.1

Type RM Length L Ch R = 1,138884,582,582,582
BEGIN DESCRIPTION:
Chauga River 278.0
END DESCRIPTION:
XS GIS Cut Line= 3
      1344170.42      1093145.38      1343784.81      1094046.86
      1343712.51      1094693.84
#Sta/Elev= 30
  4019.5 1433.41  4060.3 1432.51  4111.3 1418.36  4142.6 1402.87  4159.1 1401.94
  4202.8 1384.48  4231.0 1367.79  4231.5 1333.43  4231.7 1344.35  4234.3 1364.62
  4244.9 1359.83  4283.7 1331.53  4299.1 1329.56  4400.2 1329.84  4588.0 1320.95
  4693.3 1321.81  4824.4 1314.35  4945.7 1318.21  4956.3 1314.84  4971.6 1303.58
  4979.3 1303.58  4979.8 1302.58  5020.7 1303.58  5022.7 1318.32  5042.1 1325.29
  5140.1 1333.53  5170.8 1340.65  5248.9 1382.77  5306.4 1402.52  5651.0 1474.67
#Mann=3,-1,0
  4019.5    0.15       0  4979.3    0.05       0  5020.7    0.15       0
Bank Sta=4979.3,5020.7
XS Rating Curve= 0
Exp/Cntr=0.3,0.1

Type RM Length L Ch R = 1,138302,473,473,473
BEGIN DESCRIPTION:
Chauga River 277.0
END DESCRIPTION:
XS GIS Cut Line= 4
      1344092.10      1093077.92      1343423.59      1093680.20
      1343212.44      1093876.23      1343125.01      1094174.98
#Sta/Elev= 30
  4100.2 1440.79  4166.5 1419.11  4227.9 1394.17  4284.9 1376.58  4338.0 1352.06
  4393.2 1337.05  4415.2 1333.49  4515.7 1321.78  4739.3 1315.96  4821.2 1320.12
  4953.1 1322.94  4974.9 1302.04  4976.9 1315.32  4979.3 1302.04  4979.8 1301.04
  5020.7 1302.04  5045.2 1318.12  5066.3 1315.49  5114.5 1319.41  5130.2 1318.05
  5165.5 1335.41  5199.7 1359.94  5260.4 1391.55  5285.3 1400.74  5344.8 1417.03
  5388.8 1424.60  5438.7 1423.91  5515.1 1438.73  5562.9 1443.75  5599.4 1456.41
#Mann=3,-1,0
  4100.2    0.15       0  4979.3    0.05       0  5020.7    0.15       0
Bank Sta=4979.3,5020.7
XS Rating Curve= 0
Exp/Cntr=0.3,0.1

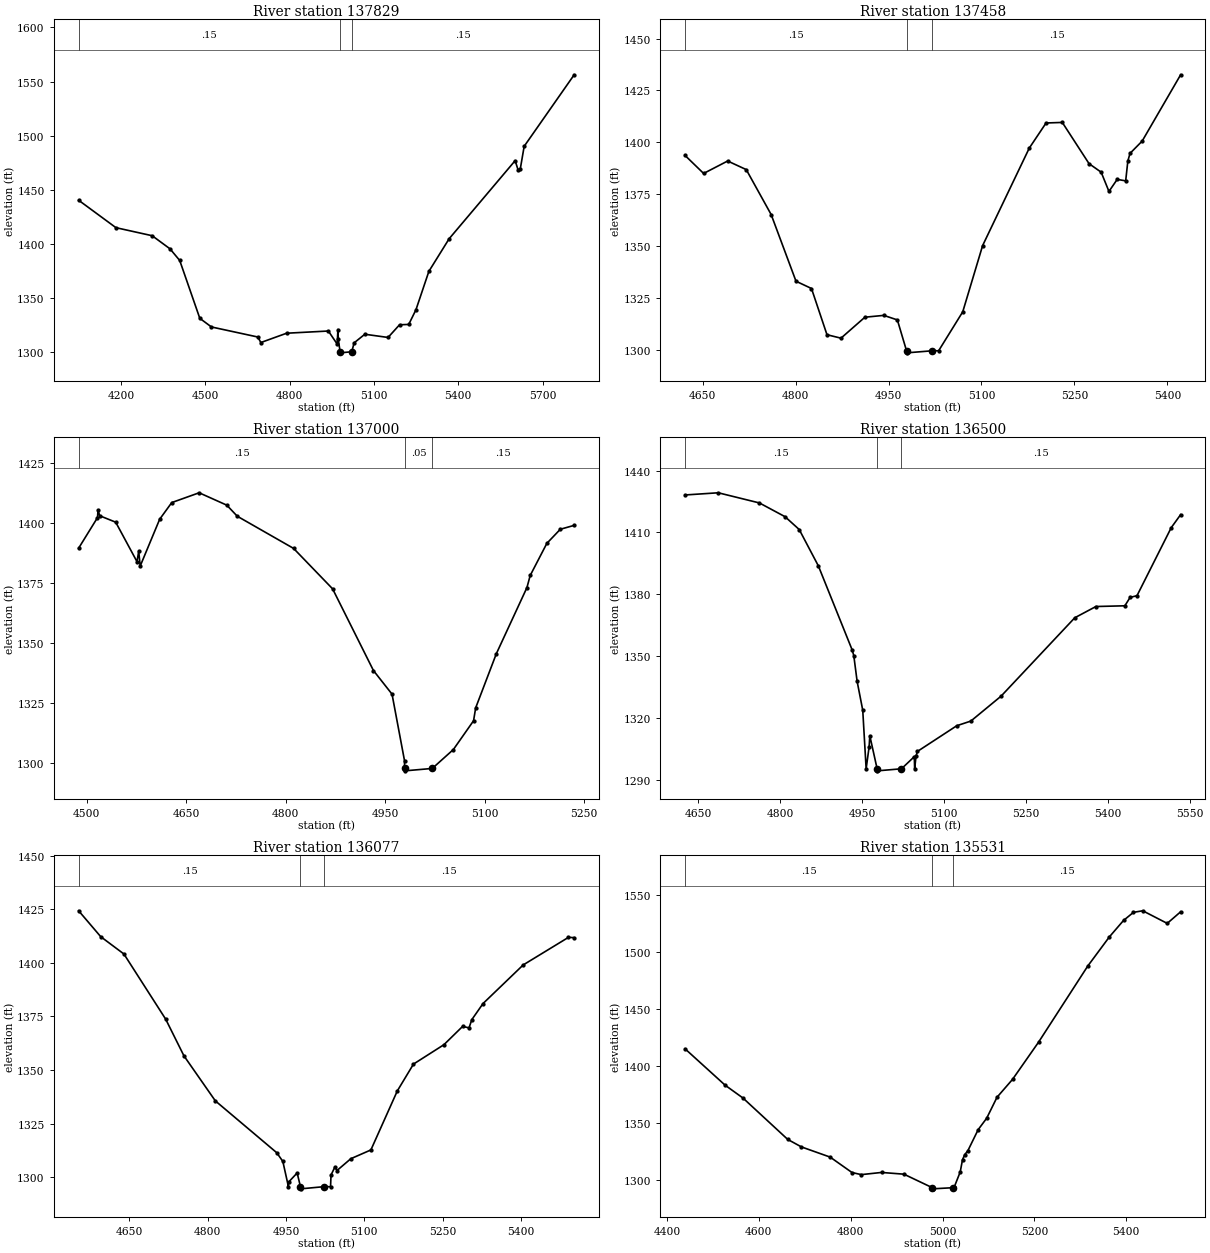
Type RM Length L Ch R = 1,137829,371,371,371
BEGIN DESCRIPTION:
Chauga River 276.0
END DESCRIPTION:
XS GIS Cut Line= 3
      1344016.81      1092996.57      1343127.79      1093335.96
      1342396.10      1093689.44
#Sta/Elev= 30
  4048.4 1440.48  4181.2 1415.16  4310.2 1407.73  4373.7 1395.63  4408.3 1384.89
  4479.8 1331.49  4521.2 1323.51  4686.3 1314.24  4697.1 1309.14  4788.9 1317.74
  4937.5 1319.77  4969.1 1307.64  4971.4 1321.17  4972.8 1312.09  4979.3 1300.63
  4979.8 1299.63  5020.7 1300.63  5029.3 1308.88  5067.3 1316.79  5150.0 1313.83
  5190.9 1325.53  5223.6 1325.85  5249.3 1339.38  5295.3 1374.83  5367.4 1404.92
  5602.5 1477.04  5613.0 1468.36  5620.9 1469.60  5634.6 1490.27  5812.6 1556.28
#Mann=3,-1,0
  4048.4    0.15       0  4979.3    0.05       0  5020.7    0.15       0
Bank Sta=4979.3,5020.7
XS Rating Curve= 0
Exp/Cntr=0.3,0.1

Type RM Length L Ch R = 1,137458,458,458,458
BEGIN DESCRIPTION:
Chauga River 275.0
END DESCRIPTION:
XS GIS Cut Line= 3
      1343378.09      1092893.57      1343011.47      1092986.84
      1342597.91      1093068.28
#Sta/Elev= 30
  4621.7 1393.63  4651.6 1384.97  4690.4 1390.97  4720.4 1386.83  4760.6 1365.17
  4800.7 1333.04  4825.7 1329.53  4850.7 1307.26  4873.3 1305.60  4911.9 1315.70
  4942.4 1316.58  4964.3 1314.39  4979.1 1299.53  4979.6 1298.53  5020.9 1299.53
  5030.9 1299.53  5069.8 1318.29  5101.9 1350.21  5177.2 1397.19  5204.3 1409.29
  5230.5 1409.56  5273.7 1389.68  5293.2 1385.59  5305.8 1376.31  5319.1 1382.11
  5332.8 1381.41  5336.3 1390.98  5339.8 1394.64  5359.4 1400.57  5421.5 1432.52
#Mann=3,-1,0
  4621.7    0.15       0  4979.1    0.05       0  5020.9    0.15       0
Bank Sta=4979.1,5020.9
XS Rating Curve= 0
Exp/Cntr=0.3,0.1

Type RM Length L Ch R = 1,137000,500,500,500
BEGIN DESCRIPTION:
Chauga River 274.0
END DESCRIPTION:
XS GIS Cut Line= 3
      1343513.68      1092504.35      1343002.81      1092542.64
      1342772.57      1092588.71
#Sta/Elev= 30
  4487.7 1389.54  4516.1 1402.24  4517.0 1405.42  4519.4 1403.05  4543.6 1400.36
  4575.7 1383.92  4578.3 1388.30  4580.5 1382.08  4609.9 1401.60  4628.1 1408.53
  4669.4 1412.61  4711.1 1407.45  4726.9 1402.84  4811.8 1389.44  4870.6 1372.61
  4932.2 1338.58  4960.2 1328.76  4979.0 1301.08  4979.1 1297.83  4979.6 1296.83
  5020.9 1297.83  5052.7 1305.71  5083.1 1317.68  5086.3 1323.06  5117.5 1345.63
  5163.6 1373.14  5168.5 1378.17  5193.6 1391.54  5213.9 1397.42  5234.8 1399.04
#Mann=3,-1,0
  4487.7    0.15       0  4979.1    0.05       0  5020.9    0.15       0
Bank Sta=4979.1,5020.9
XS Rating Curve= 0
Exp/Cntr=0.3,0.1

Type RM Length L Ch R = 1,136500,423,423,423
BEGIN DESCRIPTION:
Chauga River 273.0
END DESCRIPTION:
XS GIS Cut Line= 3
      1342823.83      1091787.36      1342764.19      1092156.37
      1342694.30      1092685.07
#Sta/Elev= 30
  4626.2 1428.16  4686.9 1429.22  4762.2 1424.30  4809.1 1417.65  4835.1 1411.43
  4870.1 1393.85  4932.2 1353.01  4935.0 1350.36  4941.1 1337.92  4951.4 1323.91
  4957.6 1295.59  4963.1 1306.31  4964.3 1311.60  4977.7 1295.59  4978.2 1294.59
  5022.3 1295.59  5045.8 1301.46  5046.4 1295.59  5049.0 1301.82  5051.6 1304.01
  5123.5 1316.43  5149.3 1318.69  5204.7 1330.77  5339.5 1368.70  5378.2 1374.15
  5431.2 1374.50  5440.8 1378.57  5453.4 1379.39  5516.1 1412.34  5533.3 1418.64
#Mann=3,-1,0
  4626.2    0.15       0  4977.7    0.05       0  5022.3    0.15       0
Bank Sta=4977.7,5022.3
XS Rating Curve= 0
Exp/Cntr=0.3,0.1

Type RM Length L Ch R = 1,136077,546,546,546
BEGIN DESCRIPTION:
Chauga River 272.0
END DESCRIPTION:
XS GIS Cut Line= 3
      1342197.23      1091820.49      1342355.67      1092238.26
      1342543.68      1092703.18
#Sta/Elev= 30
  4553.2 1424.24  4595.5 1412.16  4639.9 1404.08  4719.8 1373.70  4754.7 1356.61
  4814.8 1335.61  4932.3 1311.44  4944.0 1307.37  4954.7 1295.59  4954.9 1297.71
  4971.4 1302.00  4977.7 1295.59  4978.2 1294.59  5022.3 1295.59  5035.3 1295.59
  5036.2 1301.04  5043.6 1304.76  5047.6 1303.13  5074.1 1308.64  5112.5 1312.73
  5163.1 1340.27  5194.0 1352.76  5252.2 1361.79  5288.0 1370.32  5300.3 1369.66
  5305.7 1373.51  5327.1 1380.99  5403.9 1398.98  5490.6 1411.85  5501.5 1411.71
#Mann=3,-1,0
  4553.2    0.15       0  4977.7    0.05       0  5022.3    0.15       0
Bank Sta=4977.7,5022.3
XS Rating Curve= 0
Exp/Cntr=0.3,0.1

Type RM Length L Ch R = 1,135531,531,531,531
BEGIN DESCRIPTION:
Chauga River 271.0
END DESCRIPTION:
XS GIS Cut Line= 3
      1342121.92      1091838.60      1341845.03      1092326.05
      1341471.23      1092685.09
#Sta/Elev= 30
  4439.4 1414.94  4526.6 1382.96  4565.5 1371.66  4662.9 1335.27  4692.7 1328.68
  4755.2 1319.73  4802.7 1306.18  4823.0 1304.31  4867.1 1306.23  4915.8 1304.71
  4977.7 1292.81  4978.2 1291.81  5022.3 1292.81  5025.6 1293.59  5038.4 1306.69
  5043.4 1317.48  5048.4 1321.96  5055.0 1325.31  5077.5 1343.89  5096.0 1353.91
  5118.5 1372.36  5152.3 1388.10  5209.3 1421.03  5316.0 1487.73  5363.1 1513.42
  5393.9 1527.87  5415.6 1535.03  5435.8 1536.40  5489.1 1525.31  5518.3 1535.51
#Mann=3,-1,0
  4439.4    0.15       0  4977.7    0.05       0  5022.3    0.15       0
Bank Sta=4977.7,5022.3
XS Rating Curve= 0
Exp/Cntr=0.3,0.1