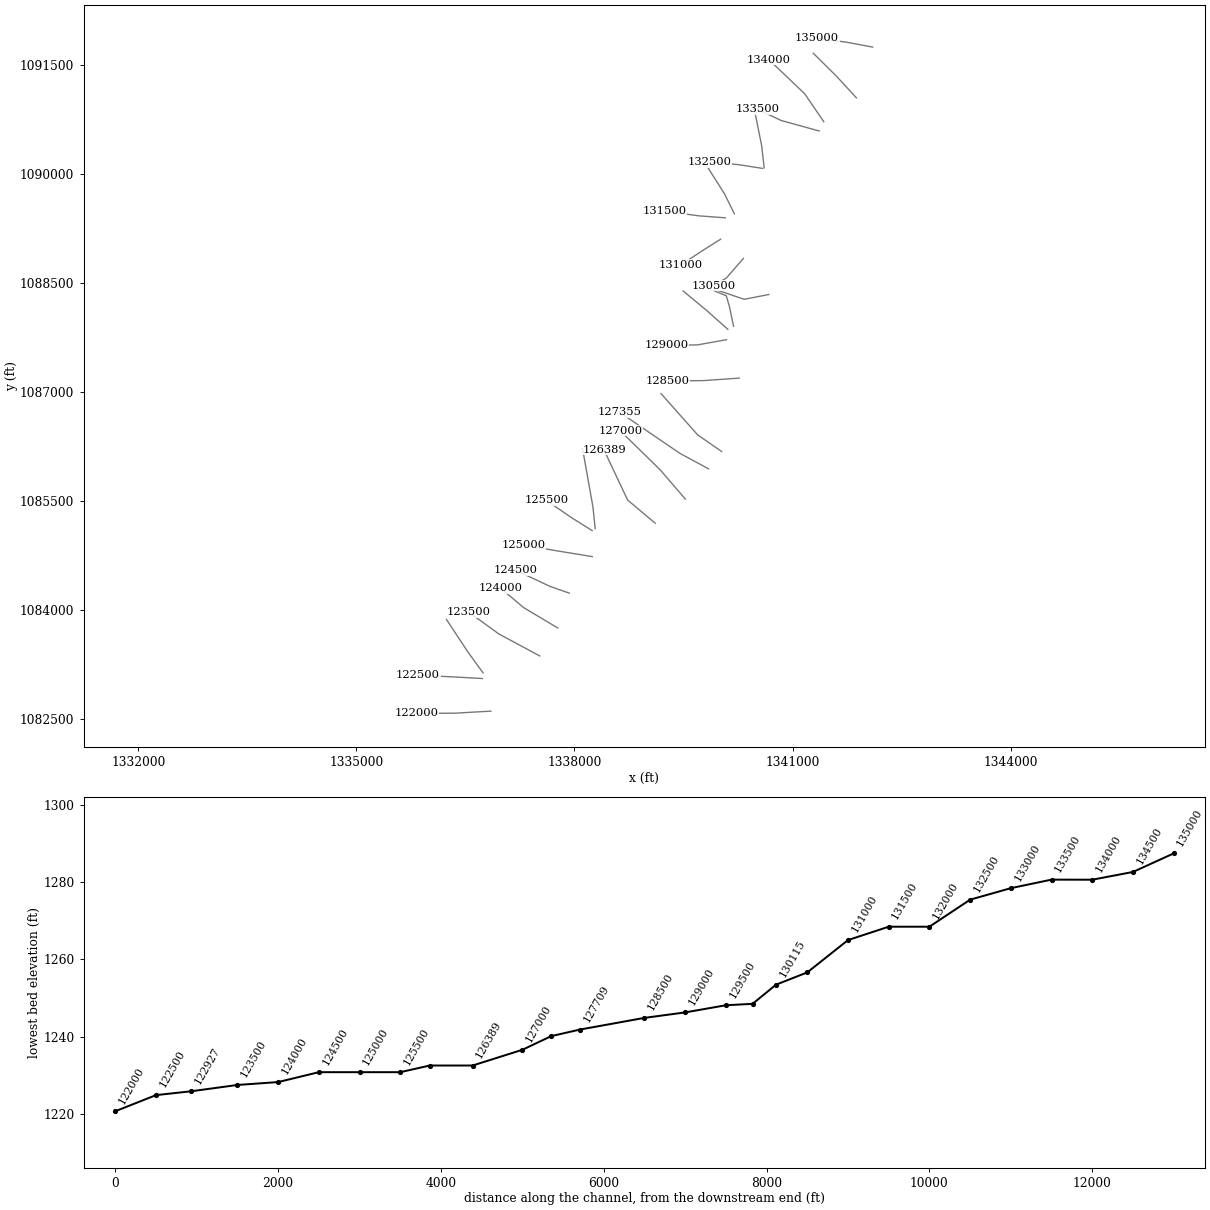
HEC-RAS study Chauga River.prj: Chauga River Limited Detail Study

--- Chauga River.g01 (geometry) --- (continued)

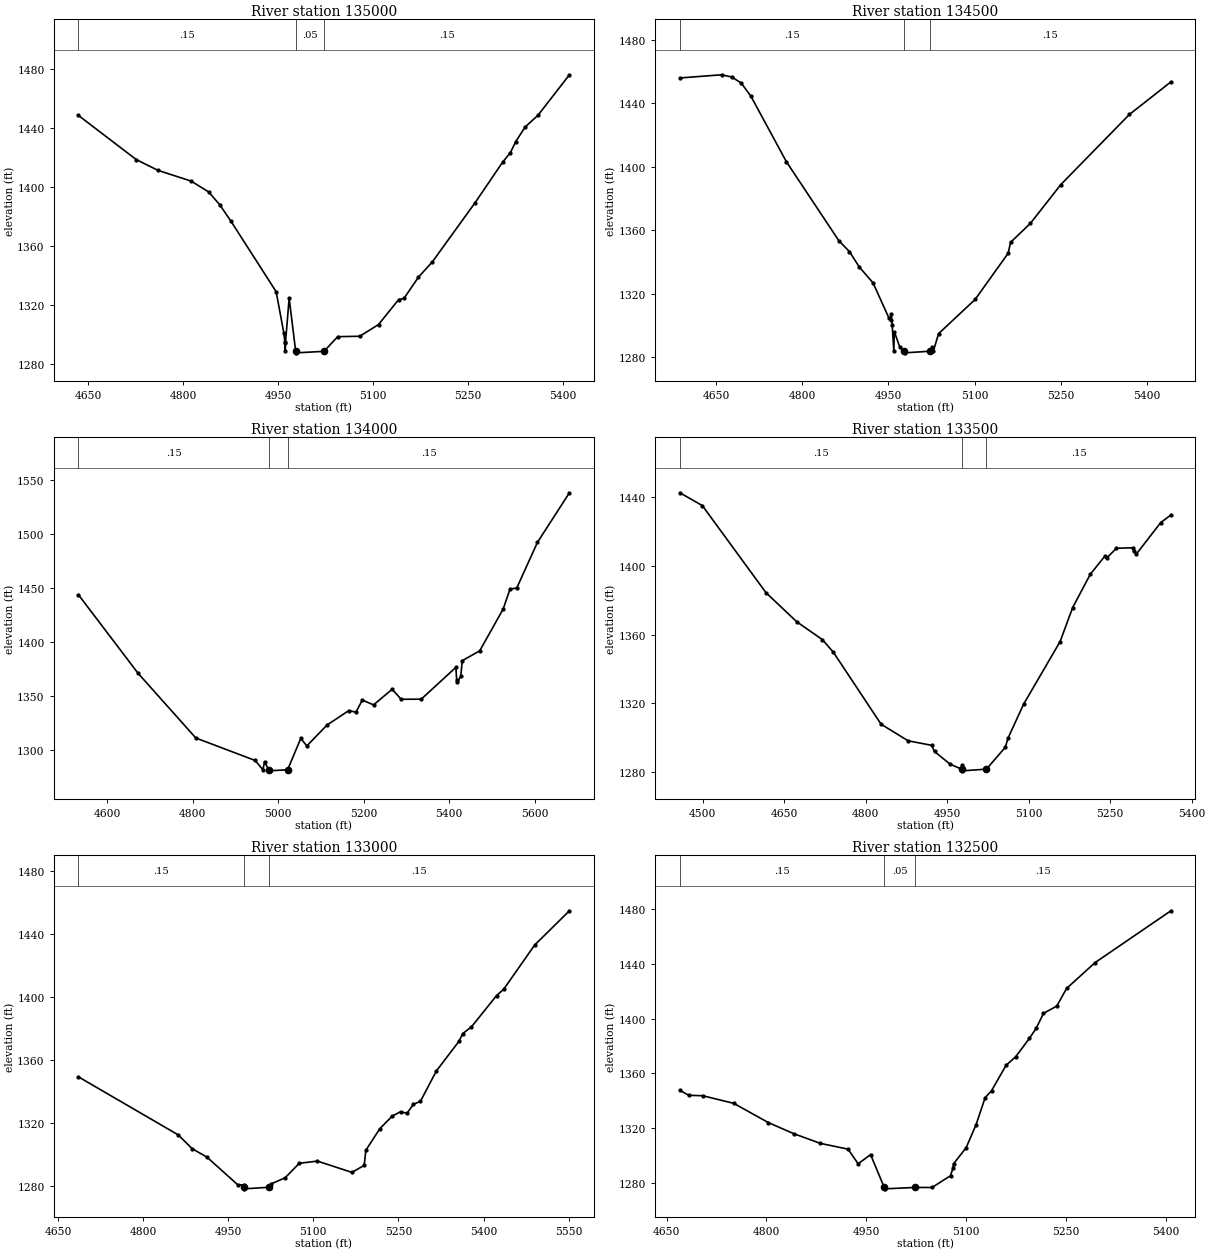
Type RM Length L Ch R = 1,135000,500,500,500
BEGIN DESCRIPTION:
Chauga River 270.0
END DESCRIPTION:
XS GIS Cut Line= 3
      1342100.86      1091748.21      1341741.94      1091815.67
      1341335.69      1091868.71
#Sta/Elev= 30
  4634.8 1448.33  4726.0 1418.42  4760.1 1411.13  4812.8 1403.79  4840.4 1396.44
  4857.9 1387.72  4875.4 1376.70  4946.9 1328.82  4959.1 1300.55  4960.6 1294.67
  4961.3 1288.38  4961.6 1294.28  4967.4 1324.47  4977.7 1288.38  4978.2 1287.38
  5022.3 1288.38  5044.0 1298.34  5078.8 1298.62  5108.4 1306.56  5140.2 1323.49
  5148.6 1324.28  5171.5 1338.73  5193.4 1349.06  5260.8 1389.13  5304.6 1416.81
  5316.6 1423.09  5324.9 1430.54  5339.8 1440.45  5360.1 1448.41  5409.7 1475.87
#Mann=3,-1,0
  4634.8    0.15       0  4977.7    0.05       0  5022.3    0.15       0
Bank Sta=4977.7,5022.3
XS Rating Curve= 0
Exp/Cntr=0.3,0.1

Type RM Length L Ch R = 1,134500,500,500,500
BEGIN DESCRIPTION:
Chauga River 269.0
END DESCRIPTION:
XS GIS Cut Line= 3
      1341877.90      1091049.33      1341598.39      1091353.11
      1341284.47      1091663.84
#Sta/Elev= 30
  4587.2 1455.92  4659.7 1457.93  4677.3 1456.54  4693.9 1452.74  4710.8 1444.39
  4772.6 1403.06  4863.8 1353.31  4882.3 1346.41  4899.3 1336.76  4923.3 1326.74
  4950.7 1304.74  4953.8 1303.13  4955.1 1306.82  4956.7 1299.84  4959.5 1283.59
  4960.4 1295.89  4970.1 1285.98  4977.7 1283.59  4978.2 1282.59  5022.3 1283.59
  5026.8 1286.37  5028.3 1283.59  5037.3 1294.66  5101.0 1316.27  5158.5 1345.40
  5162.6 1352.23  5197.3 1364.29  5250.1 1388.68  5369.5 1432.92  5441.7 1453.45
#Mann=3,-1,0
  4587.2    0.15       0  4977.7    0.05       0  5022.3    0.15       0
Bank Sta=4977.7,5022.3
XS Rating Curve= 0
Exp/Cntr=0.3,0.1

Type RM Length L Ch R = 1,134000,500,500,500
BEGIN DESCRIPTION:
Chauga River 268.0
END DESCRIPTION:
XS GIS Cut Line= 3
      1341429.03      1090720.99      1341165.96      1091106.60
      1340672.92      1091576.50
#Sta/Elev= 30
  4533.2 1443.61  4672.4 1371.03  4807.7 1310.99  4946.4 1290.20  4964.5 1281.59
  4968.5 1289.12  4977.7 1281.59  4978.2 1280.59  5022.3 1281.59  5053.1 1310.61
  5067.2 1303.63  5114.3 1322.96  5165.7 1336.43  5181.9 1334.82  5196.9 1346.07
  5223.3 1341.65  5266.6 1356.08  5287.8 1346.84  5334.7 1346.93  5415.7 1376.40
  5417.5 1364.65  5419.3 1362.59  5427.0 1368.18  5430.7 1382.57  5471.4 1391.69
  5526.3 1430.42  5542.1 1448.72  5558.1 1449.89  5606.3 1492.04  5681.1 1537.96
#Mann=3,-1,0
  4533.2    0.15       0  4977.7    0.05       0  5022.3    0.15       0
Bank Sta=4977.7,5022.3
XS Rating Curve= 0
Exp/Cntr=0.3,0.1

Type RM Length L Ch R = 1,133500,500,500,500
BEGIN DESCRIPTION:
Chauga River 267.0
END DESCRIPTION:
XS GIS Cut Line= 3
      1341365.79      1090593.23      1340843.59      1090737.64
      1340516.24      1090891.48
#Sta/Elev= 30
  4458.2 1442.68  4499.5 1435.21  4616.6 1384.46  4673.4 1367.45  4720.4 1357.10
  4740.5 1349.79  4828.4 1307.79  4877.9 1298.15  4921.2 1295.49  4926.7 1291.90
  4955.2 1284.54  4976.3 1281.61  4977.1 1283.77  4977.7 1281.61  4978.2 1280.61
  5022.3 1281.61  5056.9 1294.31  5062.0 1299.69  5090.9 1319.61  5157.8 1355.94
  5180.8 1375.68  5213.4 1395.20  5239.8 1405.60  5243.9 1404.77  5261.5 1410.34
  5292.1 1410.63  5293.0 1408.46  5298.0 1406.91  5342.9 1425.30  5361.7 1429.73
#Mann=3,-1,0
  4458.2    0.15       0  4977.7    0.05       0  5022.3    0.15       0
Bank Sta=4977.7,5022.3
XS Rating Curve= 0
Exp/Cntr=0.3,0.1

Type RM Length L Ch R = 1,133000,500,500,500
BEGIN DESCRIPTION:
Chauga River 266.0
END DESCRIPTION:
XS GIS Cut Line= 3
      1340609.66      1090084.10      1340573.86      1090396.05
      1340465.07      1090936.61
#Sta/Elev= 30
  4686.0 1349.40  4861.9 1312.60  4886.4 1303.89  4912.6 1298.49  4966.9 1280.95
  4977.5 1280.91  4977.6 1279.41  4978.1 1278.41  5022.4 1279.41  5026.0 1281.61
  5050.3 1285.40  5075.3 1294.60  5107.2 1296.00  5168.1 1288.83  5189.7 1293.29
  5192.6 1302.85  5217.1 1316.48  5238.8 1324.43  5253.7 1327.28  5265.2 1326.26
  5276.2 1331.95  5288.8 1333.88  5317.0 1353.17  5357.2 1372.14  5363.2 1376.75
  5378.8 1381.10  5423.1 1400.94  5435.6 1404.91  5490.0 1432.88  5551.4 1454.64
#Mann=3,-1,0
  4686.0    0.15       0  4977.6    0.05       0  5022.4    0.15       0
Bank Sta=4977.6,5022.4
XS Rating Curve= 0
Exp/Cntr=0.3,0.1

Type RM Length L Ch R = 1,132500,500,500,500
BEGIN DESCRIPTION:
Chauga River 265.0
END DESCRIPTION:
XS GIS Cut Line= 3
      1340585.52      1090078.10      1340259.64      1090129.44
      1339853.48      1090162.44
#Sta/Elev= 30
  4670.1 1347.56  4683.5 1343.94  4704.5 1343.62  4751.1 1338.02  4803.1 1323.91
  4841.4 1315.78  4881.2 1308.72  4922.6 1304.50  4937.8 1293.80  4956.5 1300.48
  4977.0 1276.44  4977.5 1275.44  5023.0 1276.44  5048.8 1276.44  5076.5 1285.05
  5080.4 1291.01  5081.0 1293.71  5100.0 1305.59  5114.8 1322.28  5128.5 1342.22
  5138.1 1347.27  5159.9 1365.89  5174.5 1372.23  5194.9 1385.57  5205.3 1393.10
  5216.1 1403.93  5236.1 1409.28  5250.8 1422.18  5293.7 1441.14  5407.5 1479.06
#Mann=3,-1,0
  4670.1    0.15       0  4977.0    0.05       0  5023.0    0.15       0
Bank Sta=4977,5023
XS Rating Curve= 0
Exp/Cntr=0.3,0.1

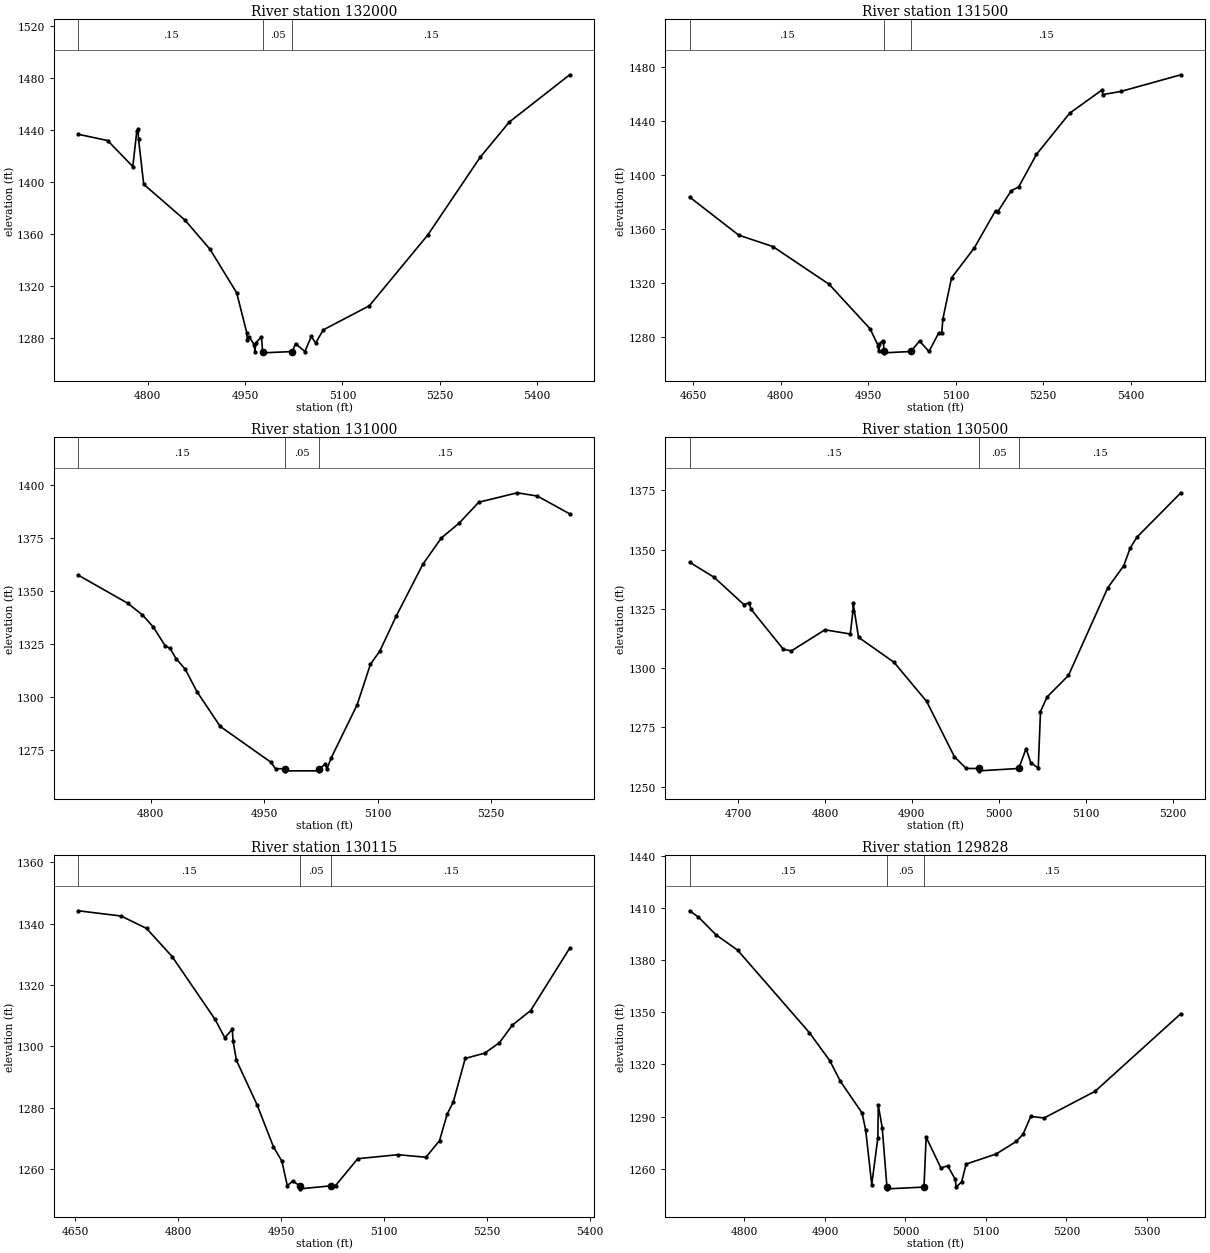
Type RM Length L Ch R = 1,132000,500,500,500
BEGIN DESCRIPTION:
Chauga River 264.0
END DESCRIPTION:
XS GIS Cut Line= 3
      1340199.96      1089452.10      1340064.07      1089727.16
      1339823.39      1090107.62
#Sta/Elev= 30
  4693.2 1436.61  4738.2 1431.80  4777.0 1411.80  4783.1 1438.79  4785.0 1440.62
  4785.8 1433.08  4793.8 1398.16  4857.4 1370.60  4895.9 1348.18  4937.0 1314.74
  4952.6 1283.92  4953.4 1278.34  4956.3 1280.80  4964.3 1274.49  4965.0 1269.46
  4966.8 1276.24  4975.2 1280.76  4977.0 1269.46  4977.5 1268.46  5023.0 1269.46
  5027.7 1275.56  5042.2 1269.46  5052.0 1281.06  5058.8 1276.01  5070.4 1286.10
  5141.5 1304.69  5231.2 1358.93  5312.1 1418.83  5357.2 1446.09  5450.2 1482.41
#Mann=3,-1,0
  4693.2    0.15       0  4977.0    0.05       0  5023.0    0.15       0
Bank Sta=4977,5023
XS Rating Curve= 0
Exp/Cntr=0.3,0.1

Type RM Length L Ch R = 1,131500,500,500,500
BEGIN DESCRIPTION:
Chauga River 263.0
END DESCRIPTION:
XS GIS Cut Line= 3
      1340073.41      1089397.88      1339717.98      1089424.29
      1339236.01      1089488.24
#Sta/Elev= 30
  4643.6 1383.71  4727.8 1355.52  4786.6 1347.04  4883.0 1319.14  4953.4 1286.15
  4967.2 1273.56  4968.1 1269.46  4968.2 1275.07  4975.1 1277.47  4976.2 1276.67
  4977.0 1269.46  4977.5 1268.46  5023.0 1269.46  5038.1 1277.19  5054.2 1269.46
  5070.8 1283.13  5076.1 1283.10  5078.0 1293.44  5092.9 1323.89  5132.2 1346.23
  5168.5 1373.69  5172.0 1372.68  5195.2 1388.34  5208.1 1391.18  5238.6 1415.26
  5295.5 1445.68  5351.8 1463.12  5352.0 1459.43  5383.3 1461.77  5486.2 1474.10
#Mann=3,-1,0
  4643.6    0.15       0  4977.0    0.05       0  5023.0    0.15       0
Bank Sta=4977,5023
XS Rating Curve= 0
Exp/Cntr=0.3,0.1

Type RM Length L Ch R = 1,131000,500,500,500
BEGIN DESCRIPTION:
Chauga River 262.0
END DESCRIPTION:
XS GIS Cut Line= 3
      1340010.17      1089102.65      1339760.17      1088945.30
      1339464.91      1088750.19
#Sta/Elev= 30
  4704.6 1357.41  4769.7 1344.19  4789.2 1338.67  4803.6 1332.92  4819.1 1324.20
  4825.8 1322.82  4833.6 1318.05  4845.7 1313.06  4861.4 1302.34  4892.0 1286.00
  4959.2 1269.02  4965.1 1266.01  4977.0 1266.01  4977.5 1265.01  5022.5 1265.01
  5023.0 1266.01  5030.6 1268.12  5033.1 1266.01  5038.9 1271.28  5072.9 1296.16
  5090.6 1315.42  5102.9 1321.55  5124.4 1337.97  5159.8 1362.59  5184.2 1374.97
  5208.2 1382.17  5233.7 1391.90  5284.6 1396.37  5311.2 1394.82  5353.9 1386.41
#Mann=3,-1,0
  4704.6    0.15       0  4977.0    0.05       0  5023.0    0.15       0
Bank Sta=4977,5023
XS Rating Curve= 0
Exp/Cntr=0.3,0.1

Type RM Length L Ch R = 1,130500,385,385,385
BEGIN DESCRIPTION:
Chauga River 261.0
END DESCRIPTION:
XS GIS Cut Line= 3
      1340323.49      1088838.78      1340090.34      1088570.02
      1339910.73      1088462.18
#Sta/Elev= 30
  4644.2 1344.72  4672.5 1338.34  4706.6 1326.86  4712.8 1327.59  4714.9 1324.87
  4752.1 1307.97  4761.4 1307.31  4800.0 1316.19  4829.1 1314.42  4832.3 1324.33
  4832.4 1327.55  4838.6 1313.04  4879.4 1302.49  4917.0 1285.98  4949.0 1262.60
  4962.5 1257.67  4977.0 1257.67  4977.5 1256.67  5023.0 1257.67  5031.4 1266.07
  5036.8 1260.15  5045.4 1257.80  5048.0 1281.71  5055.6 1287.85  5080.2 1296.95
  5125.5 1333.97  5143.8 1343.24  5151.1 1350.61  5158.8 1355.23  5209.5 1374.02
#Mann=3,-1,0
  4644.2    0.15       0  4977.0    0.05       0  5023.0    0.15       0
Bank Sta=4977,5023
XS Rating Curve= 0
Exp/Cntr=0.3,0.1

Type RM Length L Ch R = 1,130115,287,287,287
BEGIN DESCRIPTION:
Chauga River 260.0
END DESCRIPTION:
XS GIS Cut Line= 3
      1340672.92      1088341.70      1340333.57      1088275.75
      1339983.10      1088395.91
#Sta/Elev= 30
  4654.3 1344.23  4716.7 1342.51  4753.6 1338.47  4791.0 1329.27  4853.4 1308.83
  4867.7 1302.81  4878.6 1305.54  4879.8 1301.62  4884.7 1295.39  4914.7 1280.93
  4938.5 1267.27  4950.9 1262.52  4958.8 1254.56  4966.8 1256.00  4977.0 1254.49
  4977.5 1253.49  5023.0 1254.49  5029.2 1254.56  5061.5 1263.33  5120.0 1264.63
  5160.9 1263.80  5180.7 1269.21  5191.9 1277.89  5200.8 1281.85  5218.2 1296.05
  5246.6 1297.77  5268.1 1301.19  5286.9 1306.92  5313.5 1311.66  5370.5 1332.04
#Mann=3,-1,0
  4654.3    0.15       0  4977.0    0.05       0  5023.0    0.15       0
Bank Sta=4977,5023
XS Rating Curve= 0
Exp/Cntr=0.3,0.1

Type RM Length L Ch R = 1,129828,328,328,328
BEGIN DESCRIPTION:
Chauga River 259.5
END DESCRIPTION:
XS GIS Cut Line= 4
      1340187.91      1087904.90      1340133.71      1088167.57
      1340088.50      1088323.62      1339922.78      1088392.92
#Sta/Elev= 30
  4731.8 1408.28  4742.7 1404.73  4764.6 1394.48  4791.5 1385.66  4880.6 1338.30
  4905.9 1322.24  4919.2 1310.29  4946.1 1292.13  4950.6 1282.31  4958.1 1250.96
  4965.7 1277.91  4966.2 1296.62  4971.1 1283.78  4977.0 1249.55  4977.5 1248.55
  5023.0 1249.55  5025.7 1278.23  5044.0 1260.56  5052.5 1261.77  5061.8 1253.99
  5063.0 1249.55  5069.8 1252.58  5075.4 1262.77  5112.8 1268.59  5137.7 1275.77
  5146.2 1280.04  5155.6 1290.15  5172.2 1289.25  5235.6 1304.59  5342.1 1349.17
#Mann=3,-1,0
  4731.8    0.15       0  4977.0    0.05       0  5023.0    0.15       0
Bank Sta=4977,5023
XS Rating Curve= 0
Exp/Cntr=0.3,0.1

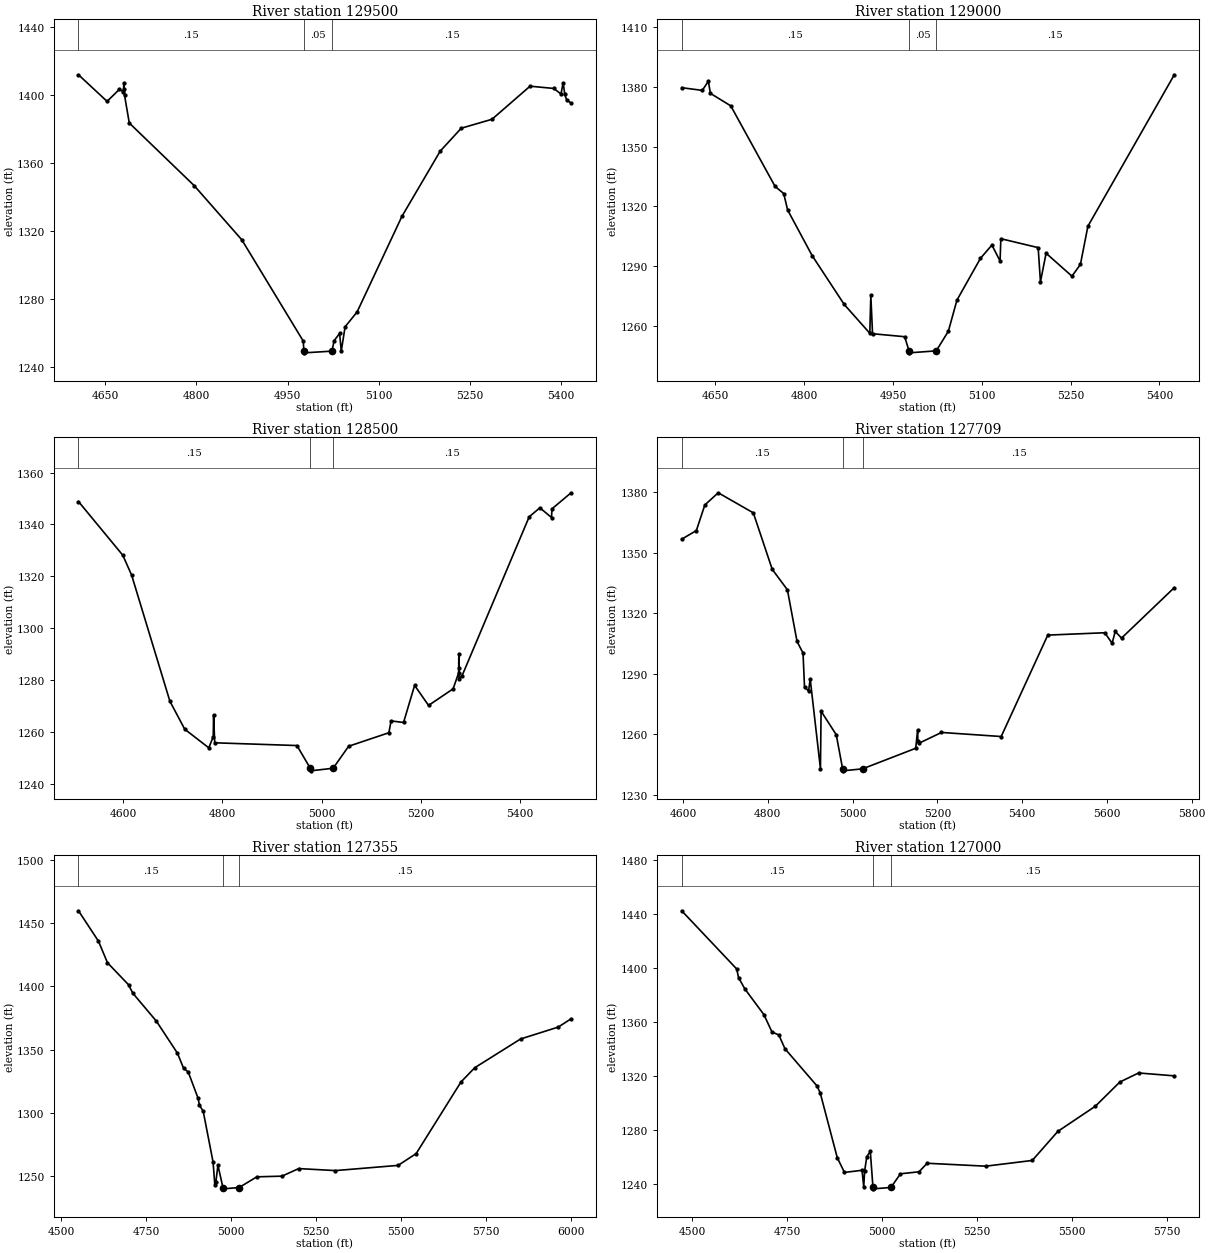
Type RM Length L Ch R = 1,129500,500,500,500
BEGIN DESCRIPTION:
Chauga River 259.0
END DESCRIPTION:
XS GIS Cut Line= 3
      1340109.57      1087862.72      1339815.59      1088124.58
      1339495.04      1088389.89
#Sta/Elev= 30
  4606.3 1411.70  4653.3 1396.07  4673.6 1403.14  4679.5 1401.83  4680.5 1403.15
  4680.7 1406.97  4682.0 1399.67  4689.8 1383.34  4796.5 1346.53  4874.9 1314.61
  4975.7 1255.17  4977.0 1249.19  4977.5 1248.19  5023.0 1249.19  5026.6 1255.39
  5035.6 1259.58  5038.3 1249.19  5044.6 1263.50  5064.3 1272.21  5138.0 1328.41
  5200.9 1366.76  5235.6 1380.28  5286.1 1385.53  5348.7 1404.99  5387.7 1403.66
  5399.5 1400.38  5403.1 1406.97  5405.8 1400.12  5408.8 1396.98  5416.1 1395.01
#Mann=3,-1,0
  4606.3    0.15       0  4977.0    0.05       0  5023.0    0.15       0
Bank Sta=4977,5023
XS Rating Curve= 0
Exp/Cntr=0.3,0.1

Type RM Length L Ch R = 1,129000,500,500,500
BEGIN DESCRIPTION:
Chauga River 258.0
END DESCRIPTION:
XS GIS Cut Line= 3
      1340091.53      1087719.92      1339691.04      1087647.96
      1339266.09      1087641.59
#Sta/Elev= 30
  4593.1 1379.68  4627.9 1378.34  4638.1 1382.91  4641.6 1376.83  4676.0 1370.54
  4750.8 1330.03  4765.4 1326.44  4772.0 1318.18  4813.3 1295.29  4867.6 1270.66
  4910.8 1256.18  4912.5 1275.41  4915.4 1255.95  4969.7 1254.45  4977.0 1247.34
  4977.5 1246.34  5023.0 1247.34  5043.4 1257.17  5058.0 1272.88  5097.7 1293.87
  5117.0 1300.55  5130.8 1292.51  5132.1 1303.74  5195.1 1299.25  5199.0 1282.04
  5208.5 1296.43  5252.2 1284.89  5266.5 1290.83  5279.1 1310.00  5425.0 1386.18
#Mann=3,-1,0
  4593.1    0.15       0  4977.0    0.05       0  5023.0    0.15       0
Bank Sta=4977,5023
XS Rating Curve= 0
Exp/Cntr=0.3,0.1

Type RM Length L Ch R = 1,128500,791,791,791
BEGIN DESCRIPTION:
Chauga River 257.0
END DESCRIPTION:
XS GIS Cut Line= 3
      1340266.28      1087190.89      1339777.48      1087156.65
      1339275.12      1087150.56
#Sta/Elev= 30
  4510.0 1348.85  4599.3 1328.12  4617.0 1320.49  4694.2 1271.77  4724.1 1260.98
  4772.6 1253.80  4781.5 1258.13  4782.2 1266.43  4784.5 1255.75  4950.1 1254.69
  4977.0 1245.93  4977.5 1244.93  5023.0 1245.93  5054.3 1254.42  5135.3 1259.63
  5139.8 1264.19  5164.9 1263.59  5187.2 1277.90  5215.3 1270.17  5264.8 1276.58
  5275.9 1282.72  5276.3 1290.17  5276.4 1284.66  5276.7 1280.46  5282.8 1281.63
  5418.0 1342.95  5439.5 1346.43  5463.0 1342.69  5464.0 1346.04  5502.4 1352.23
#Mann=3,-1,0
  4510.0    0.15       0  4977.0    0.05       0  5023.0    0.15       0
Bank Sta=4977,5023
XS Rating Curve= 0
Exp/Cntr=0.3,0.1

Type RM Length L Ch R = 1,127709,354,354,354
BEGIN DESCRIPTION:
Chauga River 256.0
END DESCRIPTION:
XS GIS Cut Line= 3
      1340024.61      1086179.95      1339693.31      1086409.93
      1339190.20      1086978.22
#Sta/Elev= 30
  4596.7 1356.80  4631.3 1361.10  4651.3 1373.79  4682.9 1379.83  4765.7 1369.87
  4810.3 1341.87  4846.1 1331.72  4868.9 1306.07  4883.0 1300.34  4886.5 1283.46
  4896.1 1281.55  4899.9 1287.50  4924.1 1242.97  4925.6 1271.50  4961.4 1259.84
  4976.4 1242.92  4976.9 1241.92  5023.6 1242.92  5148.8 1253.10  5153.7 1262.35
  5153.8 1256.89  5157.1 1255.66  5209.7 1260.96  5350.6 1258.94  5460.5 1309.24
  5594.9 1310.41  5612.3 1305.22  5619.7 1311.03  5634.6 1307.76  5759.0 1332.78
#Mann=3,-1,0
  4596.7    0.15       0  4976.4    0.05       0  5023.6    0.15       0
Bank Sta=4976.4,5023.6
XS Rating Curve= 0
Exp/Cntr=0.3,0.1

Type RM Length L Ch R = 1,127355,355,355,355
BEGIN DESCRIPTION:
Chauga River 255.0
END DESCRIPTION:
XS GIS Cut Line= 3
      1339843.93      1085941.93      1339449.65      1086155.28
      1338623.89      1086719.13
#Sta/Elev= 30
  4551.7 1459.58  4610.3 1435.66  4636.9 1418.60  4698.8 1401.23  4711.4 1394.59
  4780.8 1372.47  4842.6 1347.26  4860.9 1335.23  4874.4 1332.40  4903.4 1311.62
  4907.3 1306.22  4918.4 1301.38  4947.4 1261.36  4952.6 1242.97  4955.5 1245.53
  4961.7 1258.81  4976.4 1241.22  4976.9 1240.22  5023.6 1241.22  5076.1 1249.69
  5149.8 1250.23  5199.3 1256.20  5307.2 1254.62  5491.4 1258.72  5544.4 1268.00
  5676.3 1324.55  5717.0 1335.82  5851.4 1358.43  5962.4 1367.85  5999.9 1374.38
#Mann=3,-1,0
  4551.7    0.15       0  4976.4    0.05       0  5023.6    0.15       0
Bank Sta=4976.4,5023.6
XS Rating Curve= 0
Exp/Cntr=0.3,0.1

Type RM Length L Ch R = 1,127000,611,611,611
BEGIN DESCRIPTION:
Chauga River 254.0
END DESCRIPTION:
XS GIS Cut Line= 3
      1339524.98      1085525.02      1339181.46      1085925.20
      1338631.67      1086464.30
#Sta/Elev= 30
  4472.6 1442.52  4617.5 1399.44  4622.4 1393.01  4638.8 1384.73  4689.2 1365.62
  4710.4 1352.78  4728.4 1350.62  4744.6 1340.40  4829.0 1312.84  4837.4 1307.72
  4882.4 1259.71  4901.3 1248.84  4947.6 1250.42  4952.1 1237.94  4954.3 1249.59
  4960.1 1260.55  4969.4 1264.39  4976.4 1237.69  4976.9 1236.69  5023.6 1237.69
  5048.8 1247.83  5097.7 1249.31  5119.1 1255.62  5273.5 1253.47  5396.0 1257.70
  5463.4 1279.24  5562.1 1297.84  5626.6 1315.75  5676.1 1322.47  5770.0 1320.32
#Mann=3,-1,0
  4472.6    0.15       0  4976.4    0.05       0  5023.6    0.15       0
Bank Sta=4976.4,5023.6
XS Rating Curve= 0
Exp/Cntr=0.3,0.1

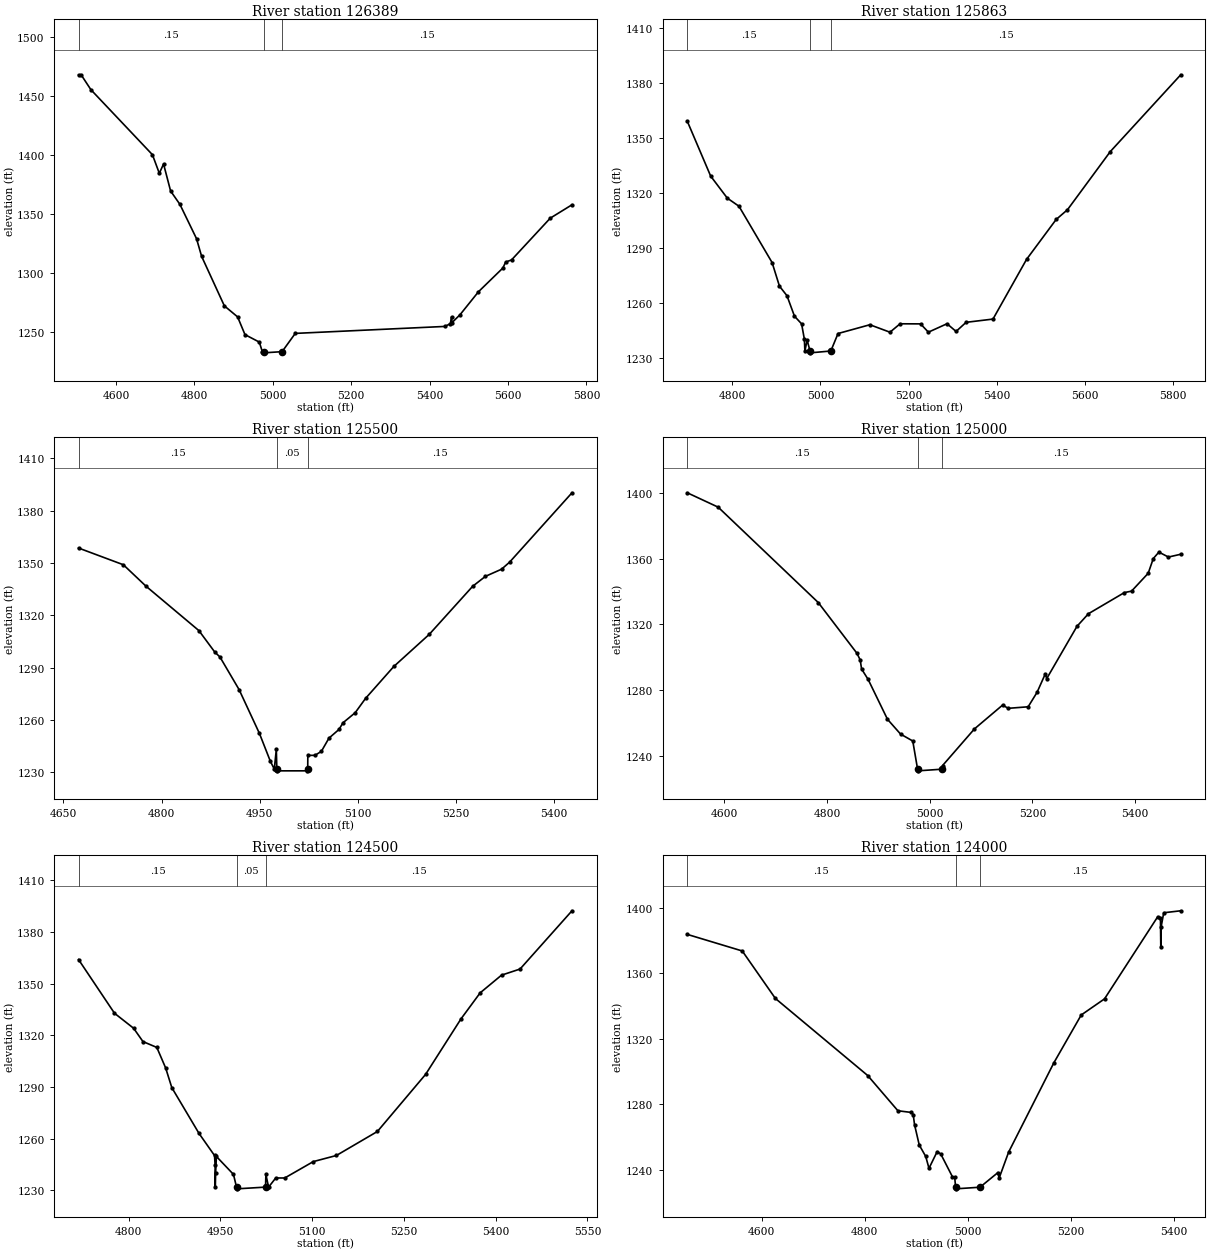
Type RM Length L Ch R = 1,126389,526,526,526
BEGIN DESCRIPTION:
Chauga River 253.0
END DESCRIPTION:
XS GIS Cut Line= 3
      1339110.65      1085193.04      1338731.29      1085512.11
      1338405.71      1086202.27
#Sta/Elev= 30
  4504.3 1468.17  4511.7 1467.77  4535.9 1455.52  4692.8 1400.47  4710.4 1384.71
  4721.2 1392.59  4739.2 1369.71  4762.8 1358.46  4805.3 1329.35  4818.3 1314.36
  4876.3 1272.42  4910.1 1263.08  4928.9 1248.06  4965.4 1241.74  4973.2 1233.63
  4976.4 1233.63  4976.9 1232.63  5023.6 1233.63  5057.2 1249.10  5439.0 1255.00
  5452.8 1257.37  5456.0 1263.19  5456.9 1258.19  5477.6 1264.96  5524.6 1284.40
  5586.8 1304.48  5593.9 1309.57  5608.8 1311.30  5707.7 1346.72  5763.1 1358.05
#Mann=3,-1,0
  4504.3    0.15       0  4976.4    0.05       0  5023.6    0.15       0
Bank Sta=4976.4,5023.6
XS Rating Curve= 0
Exp/Cntr=0.3,0.1

Type RM Length L Ch R = 1,125863,363,363,363
BEGIN DESCRIPTION:
Chauga River 252.0
END DESCRIPTION:
XS GIS Cut Line= 3
      1338285.23      1085117.72      1338253.87      1085418.29
      1338110.50      1086223.32
#Sta/Elev= 30
  4697.8 1358.94  4750.9 1329.00  4788.7 1316.97  4815.1 1312.57  4890.3 1281.86
  4907.0 1268.99  4924.0 1263.80  4941.1 1252.60  4957.2 1248.45  4963.5 1240.14
  4964.7 1233.63  4969.8 1239.54  4976.4 1233.63  4976.9 1232.63  5023.6 1233.63
  5039.9 1243.16  5112.2 1247.95  5157.8 1243.88  5180.8 1248.47  5227.2 1248.42
  5245.0 1243.90  5287.3 1248.50  5307.8 1244.30  5330.6 1249.27  5391.6 1251.04
  5467.8 1283.60  5534.9 1305.34  5560.6 1310.65  5657.8 1342.36  5817.7 1384.25
#Mann=3,-1,0
  4697.8    0.15       0  4976.4    0.05       0  5023.6    0.15       0
Bank Sta=4976.4,5023.6
XS Rating Curve= 0
Exp/Cntr=0.3,0.1

Type RM Length L Ch R = 1,125500,500,500,500
BEGIN DESCRIPTION:
Chauga River 251.0
END DESCRIPTION:
XS GIS Cut Line= 3
      1338242.48      1085091.81      1337965.52      1085265.48
      1337612.81      1085507.57
#Sta/Elev= 30
  4673.1 1358.52  4741.7 1348.93  4776.2 1336.69  4857.2 1311.22  4881.4 1298.97
  4889.4 1296.10  4918.6 1277.48  4949.8 1252.32  4966.5 1236.37  4972.5 1231.91
  4975.6 1243.22  4976.4 1231.91  4976.9 1230.91  5023.1 1230.91  5023.6 1231.91
  5023.8 1239.75  5034.7 1239.80  5044.5 1242.06  5056.1 1249.63  5071.5 1254.64
  5077.6 1258.44  5096.2 1264.19  5112.1 1272.41  5155.3 1290.68  5209.5 1309.07
  5275.9 1336.60  5295.4 1342.29  5320.1 1346.40  5332.5 1350.47  5427.8 1390.16
#Mann=3,-1,0
  4673.1    0.15       0  4976.4    0.05       0  5023.6    0.15       0
Bank Sta=4976.4,5023.6
XS Rating Curve= 0
Exp/Cntr=0.3,0.1

Type RM Length L Ch R = 1,125000,500,500,500
BEGIN DESCRIPTION:
Chauga River 250.0
END DESCRIPTION:
XS GIS Cut Line= 3
      1338245.48      1084733.34      1337779.17      1084809.60
      1337296.52      1084889.99
#Sta/Elev= 30
  4527.5 1400.08  4587.7 1391.33  4782.8 1333.30  4858.2 1302.43  4864.6 1298.33
  4867.2 1292.89  4880.0 1286.52  4917.7 1262.28  4943.2 1253.27  4967.0 1249.06
  4976.4 1231.91  4976.9 1230.91  5023.6 1231.91  5025.0 1234.10  5087.2 1256.42
  5142.2 1270.95  5152.9 1268.94  5191.9 1269.88  5209.2 1278.65  5225.4 1289.95
  5228.0 1286.99  5287.2 1318.90  5309.5 1326.52  5379.5 1339.37  5393.4 1340.24
  5425.9 1351.12  5435.8 1360.07  5446.7 1363.98  5465.3 1360.98  5489.3 1362.68
#Mann=3,-1,0
  4527.5    0.15       0  4976.4    0.05       0  5023.6    0.15       0
Bank Sta=4976.4,5023.6
XS Rating Curve= 0
Exp/Cntr=0.3,0.1

Type RM Length L Ch R = 1,124500,500,500,500
BEGIN DESCRIPTION:
Chauga River 249.0
END DESCRIPTION:
XS GIS Cut Line= 3
      1337929.14      1084230.26      1337663.09      1084323.77
      1337188.05      1084546.58
#Sta/Elev= 30
  4718.0 1364.07  4776.8 1332.87  4808.1 1324.14  4823.3 1316.43  4846.0 1313.02
  4860.4 1301.12  4870.5 1289.68  4915.0 1263.07  4940.3 1250.27  4941.3 1244.86
  4941.5 1231.91  4942.1 1240.06  4943.4 1249.71  4971.3 1239.29  4976.3 1231.91
  4976.8 1230.91  5023.7 1231.91  5024.3 1239.24  5028.7 1231.91  5040.4 1237.22
  5055.1 1237.21  5101.8 1246.73  5139.5 1250.27  5206.6 1264.22  5285.3 1297.33
  5343.2 1329.58  5374.6 1344.72  5409.5 1354.99  5439.8 1358.54  5524.7 1392.37
#Mann=3,-1,0
  4718.0    0.15       0  4976.3    0.05       0  5023.7    0.15       0
Bank Sta=4976.3,5023.7
XS Rating Curve= 0
Exp/Cntr=0.3,0.1

Type RM Length L Ch R = 1,124000,500,500,500
BEGIN DESCRIPTION:
Chauga River 248.0
END DESCRIPTION:
XS GIS Cut Line= 3
      1337769.49      1083751.27      1337302.08      1084030.17
      1336986.21      1084296.56
#Sta/Elev= 30
  4455.7 1383.87  4562.4 1373.73  4626.7 1344.70  4805.8 1297.61  4864.4 1276.08
  4890.5 1275.05  4894.1 1273.79  4896.7 1267.51  4905.8 1255.15  4918.4 1248.14
  4924.7 1240.91  4940.6 1251.13  4947.5 1249.69  4970.1 1235.78  4974.6 1235.49
  4976.3 1229.36  4976.8 1228.36  5023.7 1229.36  5058.6 1238.34  5060.7 1234.82
  5079.2 1250.78  5166.9 1305.32  5220.1 1334.61  5265.3 1344.46  5368.6 1394.70
  5373.8 1393.92  5374.5 1376.17  5375.1 1388.40  5380.2 1397.09  5413.2 1398.30
#Mann=3,-1,0
  4455.7    0.15       0  4976.3    0.05       0  5023.7    0.15       0
Bank Sta=4976.3,5023.7
XS Rating Curve= 0
Exp/Cntr=0.3,0.1

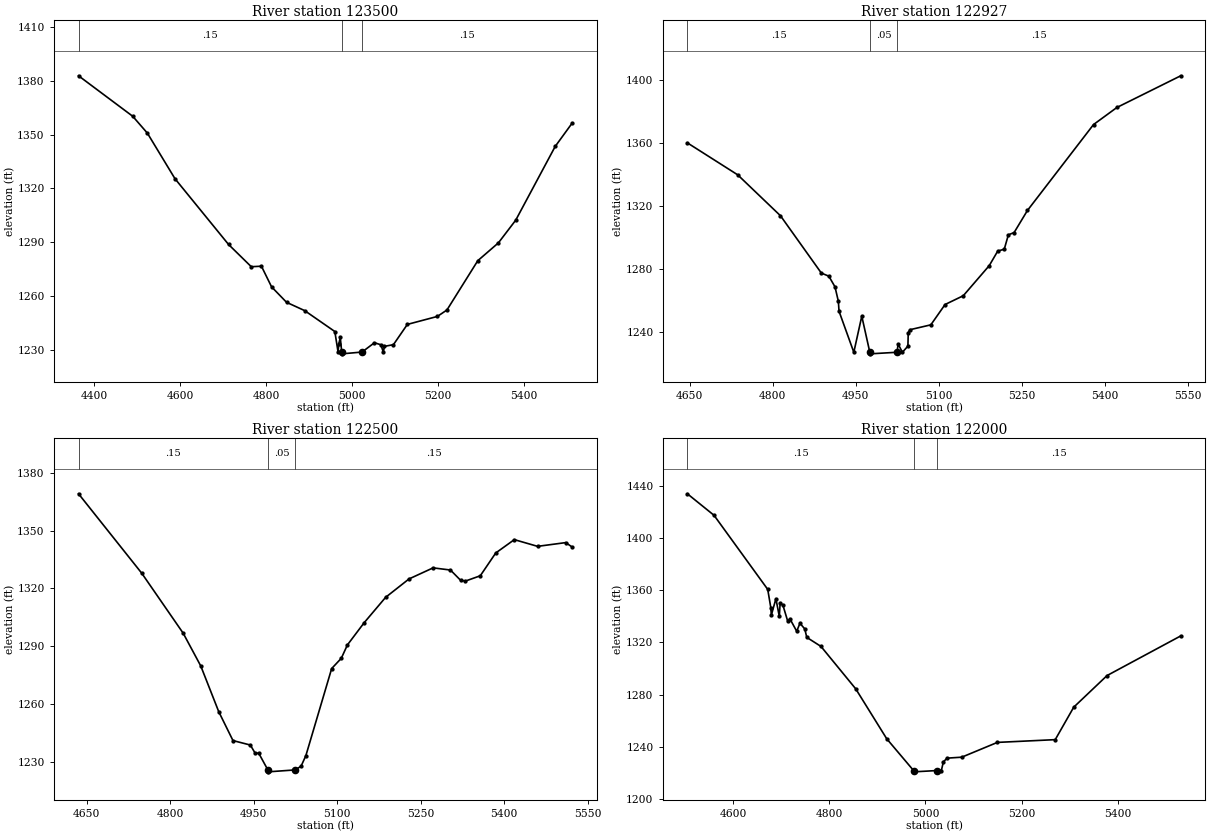
Type RM Length L Ch R = 1,123500,573,573,573
BEGIN DESCRIPTION:
Chauga River 247.0
END DESCRIPTION:
XS GIS Cut Line= 3
      1337522.50      1083365.66      1336961.68      1083667.53
      1336546.39      1083968.19
#Sta/Elev= 30
  4363.1 1382.97  4489.4 1360.34  4523.5 1350.93  4587.9 1325.44  4712.7 1288.71
  4765.6 1276.29  4789.3 1276.57  4812.9 1265.04  4847.8 1256.40  4890.1 1251.75
  4960.3 1240.08  4967.8 1228.69  4969.8 1233.37  4973.0 1236.78  4976.3 1228.61
  4976.8 1227.61  5023.7 1228.61  5052.6 1233.81  5067.7 1232.67  5073.2 1228.61
  5076.0 1231.80  5096.8 1232.73  5129.3 1244.06  5199.2 1248.51  5221.5 1252.10
  5293.4 1279.66  5341.4 1289.61  5381.8 1302.30  5473.7 1343.47  5512.7 1356.34
#Mann=3,-1,0
  4363.1    0.15       0  4976.3    0.05       0  5023.7    0.15       0
Bank Sta=4976.3,5023.7
XS Rating Curve= 0
Exp/Cntr=0.3,0.1

Type RM Length L Ch R = 1,122927,427,427,427
BEGIN DESCRIPTION:
Chauga River 246.0
END DESCRIPTION:
XS GIS Cut Line= 3
      1336742.26      1083133.07      1336534.42      1083419.77
      1336239.14      1083868.17
#Sta/Elev= 30
  4645.9 1359.97  4736.8 1339.66  4814.1 1313.65  4887.9 1277.26  4901.4 1275.29
  4912.5 1268.52  4918.6 1259.33  4919.8 1253.02  4946.5 1226.97  4960.9 1249.89
  4975.4 1226.97  4975.9 1225.97  5024.6 1226.97  5026.5 1232.21  5034.2 1226.97
  5044.2 1230.86  5044.8 1239.44  5047.8 1241.28  5085.6 1244.39  5111.3 1257.30
  5144.2 1262.88  5191.1 1282.01  5206.4 1291.23  5218.2 1292.43  5225.6 1301.55
  5236.0 1303.01  5260.0 1317.01  5379.4 1371.59  5421.6 1382.44  5536.9 1402.57
#Mann=3,-1,0
  4645.9    0.15       0  4975.4    0.05       0  5024.6    0.15       0
Bank Sta=4975.4,5024.6
XS Rating Curve= 0
Exp/Cntr=0.3,0.1

Type RM Length L Ch R = 1,122500,500,500,500
BEGIN DESCRIPTION:
Chauga River 245.0
END DESCRIPTION:
XS GIS Cut Line= 3
      1336733.18      1083054.79      1336368.87      1083075.43
      1335847.54      1083099.97
#Sta/Elev= 30
  4635.1 1369.07  4748.8 1327.88  4823.2 1296.83  4854.8 1279.86  4887.1 1256.17
  4912.7 1241.19  4943.9 1238.88  4952.6 1234.64  4958.9 1234.70  4975.4 1225.99
  4975.9 1224.99  5024.6 1225.99  5035.1 1227.91  5043.7 1233.37  5090.1 1278.51
  5107.4 1283.83  5118.4 1290.76  5148.4 1302.23  5187.1 1315.42  5229.1 1324.94
  5272.4 1330.68  5303.6 1329.56  5321.7 1324.28  5330.4 1323.83  5357.2 1326.58
  5385.0 1338.40  5418.4 1345.31  5460.2 1341.83  5510.8 1343.77  5521.9 1341.55
#Mann=3,-1,0
  4635.1    0.15       0  4975.4    0.05       0  5024.6    0.15       0
Bank Sta=4975.4,5024.6
XS Rating Curve= 0
Exp/Cntr=0.3,0.1

Type RM Length L Ch R = 1,122000,500,500,500
BEGIN DESCRIPTION:
Chauga River 244.0
END DESCRIPTION:
XS GIS Cut Line= 3
      1336850.63      1082605.92      1336356.23      1082577.75
      1335825.04      1082575.00
#Sta/Elev= 30
  4504.8 1433.94  4560.3 1417.44  4672.0 1360.66  4678.4 1346.71  4679.5 1340.88
  4689.0 1353.54  4696.1 1339.93  4697.8 1350.23  4703.6 1348.58  4713.7 1336.11
  4718.0 1338.20  4732.3 1328.57  4739.0 1334.69  4749.1 1330.35  4753.2 1323.89
  4782.8 1316.94  4855.0 1284.47  4919.6 1246.15  4975.4 1221.83  4975.9 1220.83
  5024.6 1221.83  5033.2 1221.83  5037.4 1228.49  5045.2 1231.33  5075.6 1232.06
  5149.7 1243.39  5270.1 1245.50  5308.6 1270.39  5377.9 1294.62  5531.2 1325.01
#Mann=3,-1,0
  4504.8    0.15       0  4975.4    0.05       0  5024.6    0.15       0
Bank Sta=4975.4,5024.6
XS Rating Curve= 0
Exp/Cntr=0.3,0.1