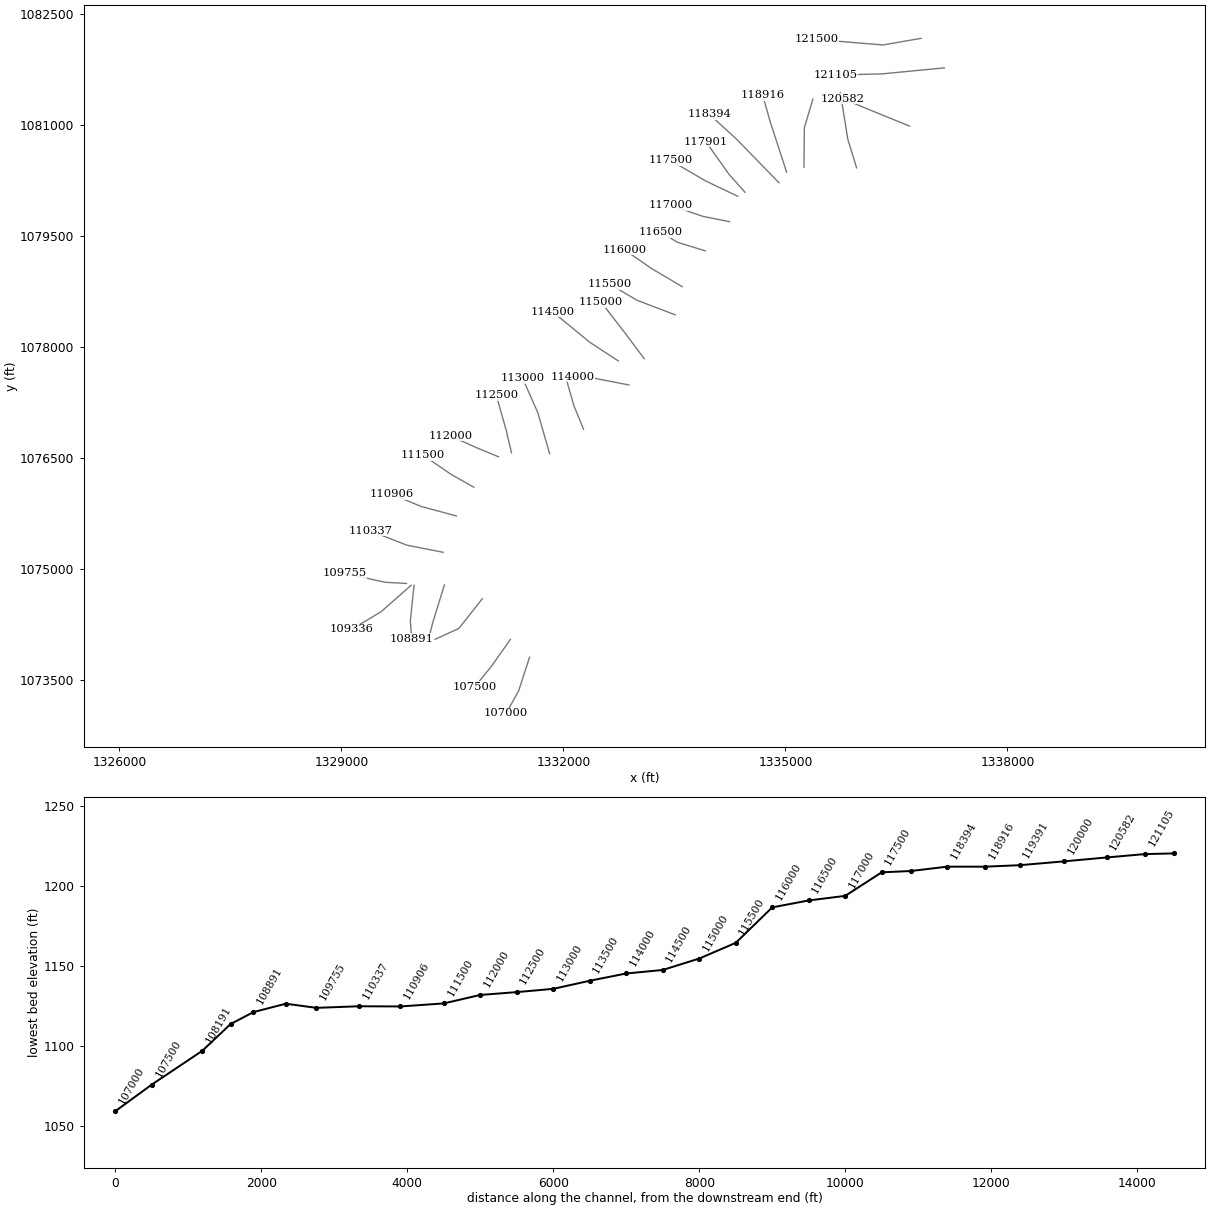
HEC-RAS study Chauga River.prj: Chauga River Limited Detail Study

--- Chauga River.g01 (geometry) --- (continued)

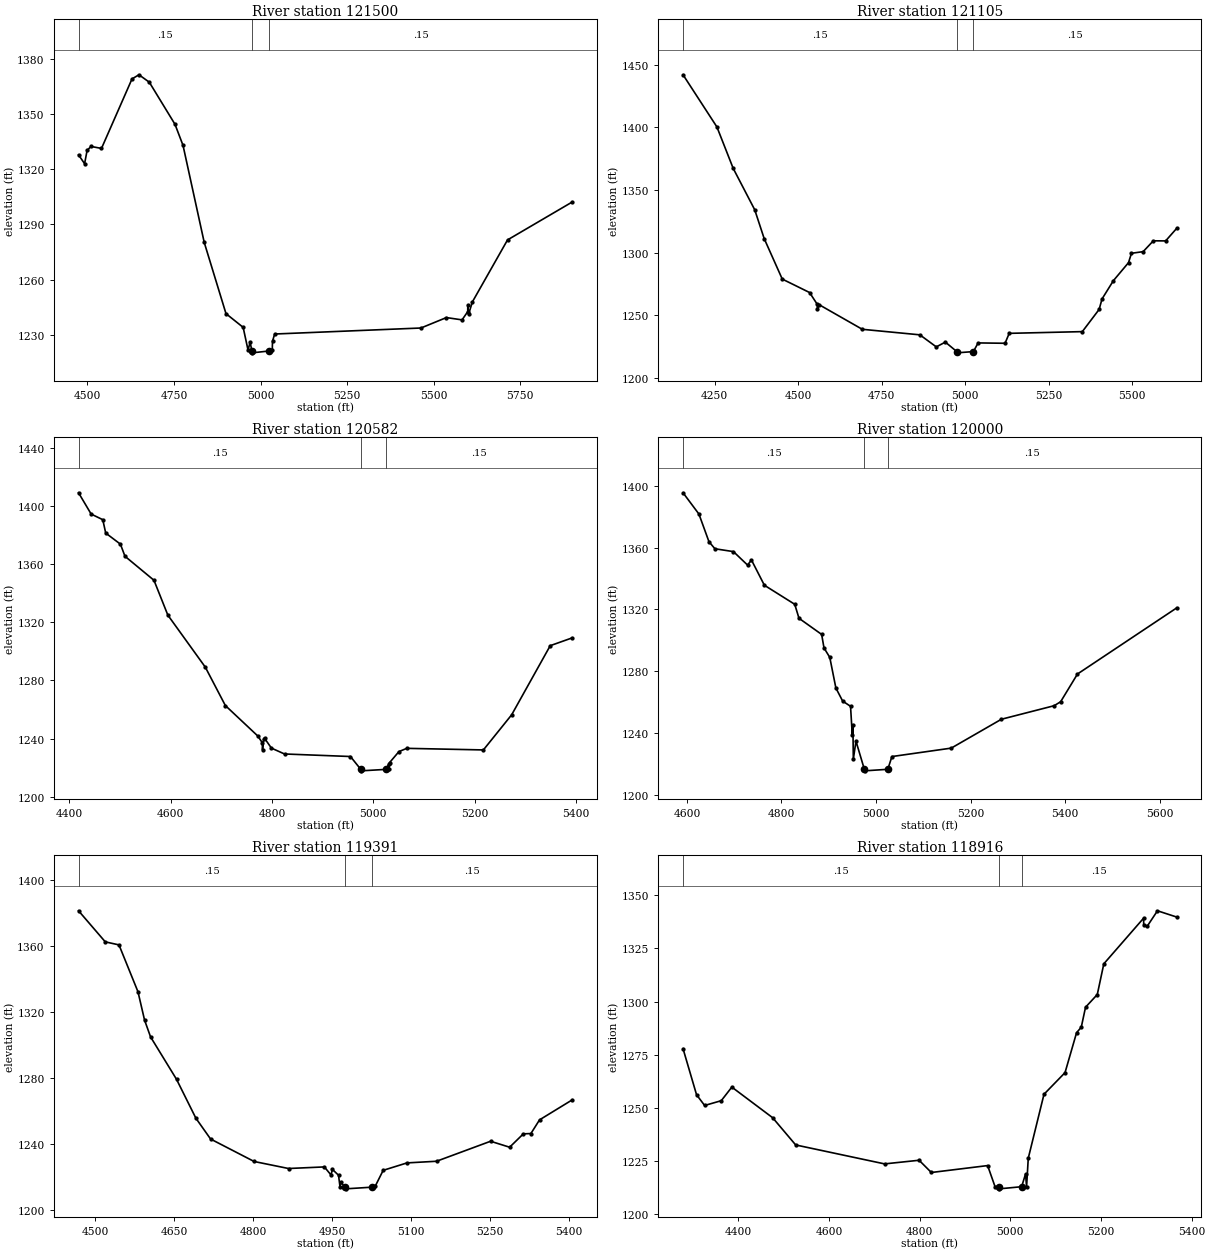
Type RM Length L Ch R = 1,121500,395,395,395
BEGIN DESCRIPTION:
Chauga River 243.0
END DESCRIPTION:
XS GIS Cut Line= 3
      1336835.57      1082172.12      1336317.51      1082082.82
      1335419.78      1082157.06
#Sta/Elev= 30
  4474.3 1327.72  4491.8 1322.95  4499.0 1330.13  4510.2 1332.31  4540.6 1331.23
  4628.8 1368.95  4648.9 1371.18  4678.7 1367.16  4753.0 1344.30  4776.2 1332.84
  4837.3 1280.32  4900.3 1241.60  4949.9 1234.16  4964.0 1221.83  4969.9 1226.06
  4975.4 1221.34  4975.9 1220.34  5024.6 1221.34  5034.0 1221.83  5034.7 1226.68
  5041.0 1230.55  5463.5 1233.81  5537.1 1239.47  5582.3 1238.22  5598.7 1242.68
  5598.9 1246.34  5601.3 1241.38  5612.3 1248.02  5713.7 1281.60  5900.8 1302.19
#Mann=3,-1,0
  4474.3    0.15       0  4975.4    0.05       0  5024.6    0.15       0
Bank Sta=4975.4,5024.6
XS Rating Curve= 0
Exp/Cntr=0.3,0.1

Type RM Length L Ch R = 1,121105,523,523,523
BEGIN DESCRIPTION:
Chauga River 242.0
END DESCRIPTION:
XS GIS Cut Line= 3
      1337148.96      1081772.68      1336308.52      1081692.04
      1335675.05      1081675.00
#Sta/Elev= 30
  4155.7 1441.99  4257.1 1400.33  4305.8 1367.26  4370.3 1334.17  4398.5 1311.22
  4452.7 1278.82  4534.5 1268.07  4557.1 1258.80  4558.1 1254.64  4563.1 1258.36
  4692.3 1238.71  4864.6 1234.29  4913.8 1224.67  4940.9 1228.48  4975.2 1220.91
  4975.7 1219.91  5024.8 1220.91  5039.0 1227.83  5119.6 1227.55  5132.1 1235.48
  5350.9 1236.85  5401.3 1254.61  5409.9 1262.95  5443.8 1277.51  5489.2 1291.94
  5498.0 1299.42  5533.0 1300.73  5563.5 1309.39  5600.3 1309.31  5633.7 1319.42
#Mann=3,-1,0
  4155.7    0.15       0  4975.2    0.05       0  5024.8    0.15       0
Bank Sta=4975.2,5024.8
XS Rating Curve= 0
Exp/Cntr=0.3,0.1

Type RM Length L Ch R = 1,120582,582,582,582
BEGIN DESCRIPTION:
Chauga River 241.0
END DESCRIPTION:
XS GIS Cut Line= 3
      1336675.95      1080986.42      1336137.48      1081206.22
      1335775.19      1081356.96
#Sta/Elev= 30
  4418.4 1409.22  4443.3 1394.56  4466.2 1390.70  4472.0 1381.49  4501.0 1373.85
  4510.0 1365.51  4567.2 1348.98  4594.6 1324.97  4668.5 1289.16  4708.0 1262.76
  4772.2 1241.72  4780.9 1237.13  4781.3 1232.32  4783.5 1239.61  4785.3 1240.22
  4798.9 1233.44  4824.7 1229.41  4954.8 1227.66  4975.2 1218.80  4975.7 1217.80
  5024.8 1218.80  5030.1 1222.30  5030.8 1218.80  5032.1 1223.52  5050.4 1231.04
  5065.9 1233.29  5217.0 1232.19  5272.8 1256.38  5348.9 1303.97  5392.4 1309.36
#Mann=3,-1,0
  4418.4    0.15       0  4975.2    0.05       0  5024.8    0.15       0
Bank Sta=4975.2,5024.8
XS Rating Curve= 0
Exp/Cntr=0.3,0.1

Type RM Length L Ch R = 1,120000,609,609,609
BEGIN DESCRIPTION:
Chauga River 240.0
END DESCRIPTION:
XS GIS Cut Line= 3
      1335962.00      1080421.26      1335842.72      1080811.65
      1335742.08      1081439.53
#Sta/Elev= 30
  4591.8 1395.54  4625.4 1381.76  4646.6 1363.85  4659.2 1359.27  4698.4 1357.42
  4728.2 1348.71  4736.5 1351.98  4763.8 1335.63  4828.0 1323.29  4837.0 1314.22
  4884.9 1303.77  4889.9 1295.00  4902.1 1288.90  4915.0 1269.05  4929.3 1260.59
  4946.0 1257.18  4949.7 1238.48  4951.0 1245.33  4951.9 1222.98  4957.5 1234.62
  4975.2 1216.38  4975.7 1215.38  5024.8 1216.38  5033.5 1224.64  5159.0 1230.10
  5265.0 1248.80  5376.6 1257.58  5390.3 1260.16  5425.9 1278.12  5635.9 1320.99
#Mann=3,-1,0
  4591.8    0.15       0  4975.2    0.05       0  5024.8    0.15       0
Bank Sta=4975.2,5024.8
XS Rating Curve= 0
Exp/Cntr=0.3,0.1

Type RM Length L Ch R = 1,119391,475,475,475
BEGIN DESCRIPTION:
Chauga River 239.0
END DESCRIPTION:
XS GIS Cut Line= 3
      1335251.05      1080430.30      1335255.87      1080962.18
      1335371.43      1081351.28
#Sta/Elev= 30
  4468.1 1381.15  4518.9 1362.34  4544.9 1360.52  4581.0 1332.16  4593.5 1315.02
  4604.9 1304.86  4654.2 1279.22  4691.0 1255.68  4718.9 1243.10  4801.6 1229.51
  4866.9 1225.27  4935.0 1226.23  4947.6 1221.36  4950.3 1224.71  4961.9 1221.21
  4964.8 1213.97  4965.7 1216.81  4975.0 1213.97  4975.5 1212.97  5025.0 1213.97
  5031.4 1214.43  5046.7 1224.16  5092.0 1228.66  5148.0 1229.65  5250.7 1241.75
  5286.9 1238.14  5312.9 1246.22  5327.3 1246.42  5343.7 1254.69  5405.9 1266.81
#Mann=3,-1,0
  4468.1    0.15       0  4975.0    0.05       0  5025.0    0.15       0
Bank Sta=4975,5025
XS Rating Curve= 0
Exp/Cntr=0.3,0.1

Type RM Length L Ch R = 1,118916,522,522,522
BEGIN DESCRIPTION:
Chauga River 238.0
END DESCRIPTION:
XS GIS Cut Line= 3
      1335016.34      1080363.71      1334792.91      1081049.85
      1334693.75      1081403.31
#Sta/Elev= 30
  4278.4 1277.89  4308.2 1256.25  4326.0 1251.21  4362.7 1253.46  4386.0 1259.84
  4476.0 1245.45  4526.8 1232.66  4722.8 1223.76  4798.9 1225.47  4825.9 1219.72
  4950.0 1222.97  4966.4 1213.04  4975.0 1213.04  4975.5 1212.04  5025.0 1213.04
  5033.6 1219.01  5035.9 1213.04  5039.6 1226.40  5074.3 1256.48  5120.7 1266.65
  5146.1 1285.39  5156.5 1288.00  5165.9 1297.37  5191.8 1303.34  5206.2 1317.77
  5293.9 1339.21  5294.2 1336.02  5301.7 1335.36  5324.5 1342.69  5367.1 1339.73
#Mann=3,-1,0
  4278.4    0.15       0  4975.0    0.05       0  5025.0    0.15       0
Bank Sta=4975,5025
XS Rating Curve= 0
Exp/Cntr=0.3,0.1

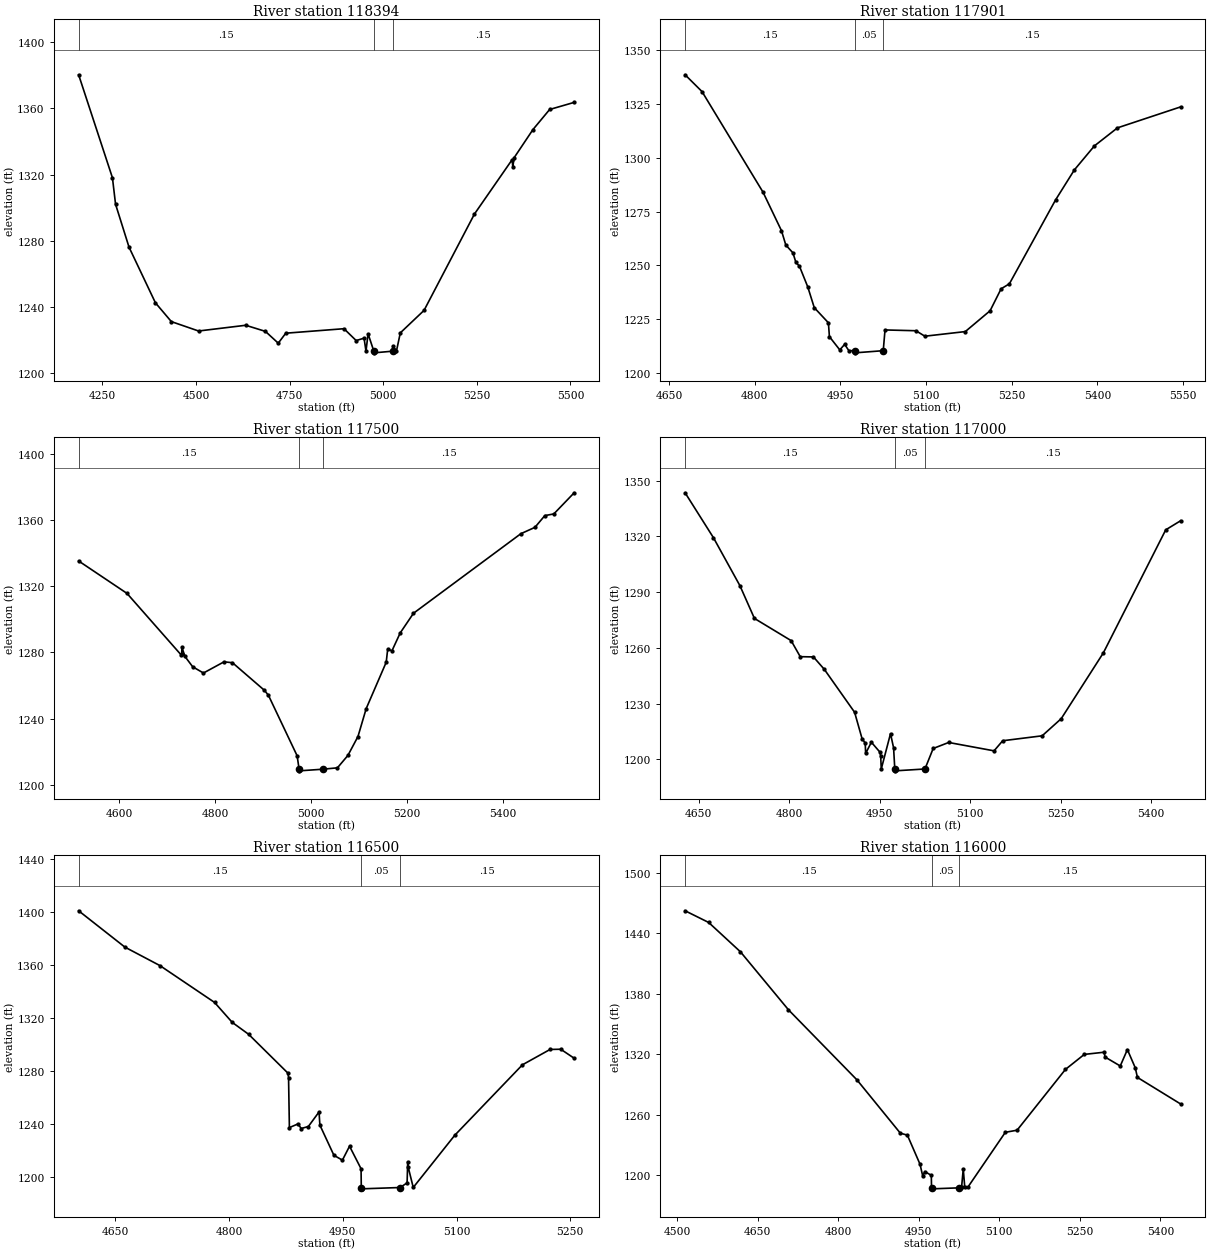
Type RM Length L Ch R = 1,118394,493,493,493
BEGIN DESCRIPTION:
Chauga River 237.0
END DESCRIPTION:
XS GIS Cut Line= 3
      1334913.67      1080219.42      1334346.70      1080802.66
      1333970.75      1081147.28
#Sta/Elev= 30
  4186.6 1380.37  4276.9 1318.02  4285.2 1302.01  4321.2 1276.00  4391.7 1242.32
  4434.2 1230.95  4506.9 1225.26  4632.9 1228.73  4685.4 1225.03  4719.7 1217.89
  4739.8 1223.93  4895.2 1226.65  4927.8 1219.47  4948.9 1220.93  4954.0 1213.04
  4959.6 1223.57  4975.0 1213.04  4975.5 1212.04  5025.0 1213.04  5025.6 1216.12
  5035.3 1213.04  5045.7 1224.13  5109.1 1237.75  5243.7 1296.08  5344.4 1329.00
  5346.1 1324.52  5349.6 1330.15  5399.9 1347.20  5444.5 1359.36  5510.0 1363.66
#Mann=3,-1,0
  4186.6    0.15       0  4975.0    0.05       0  5025.0    0.15       0
Bank Sta=4975,5025
XS Rating Curve= 0
Exp/Cntr=0.3,0.1

Type RM Length L Ch R = 1,117901,401,401,401
BEGIN DESCRIPTION:
Chauga River 236.0
END DESCRIPTION:
XS GIS Cut Line= 3
      1334455.74      1080089.92      1334241.41      1080330.23
      1333925.02      1080774.97
#Sta/Elev= 30
  4678.0 1338.55  4707.6 1330.75  4814.4 1284.02  4846.8 1266.08  4854.4 1259.42
  4866.8 1255.81  4872.1 1251.33  4878.2 1249.62  4892.8 1239.99  4904.2 1230.33
  4929.0 1223.28  4930.7 1216.86  4948.9 1210.70  4957.4 1213.27  4964.8 1210.33
  4975.0 1210.33  4975.5 1209.33  5025.0 1210.33  5028.1 1219.97  5082.2 1219.60
  5097.9 1217.06  5168.7 1219.21  5212.1 1228.88  5231.4 1239.09  5245.9 1241.41
  5326.7 1280.36  5359.7 1294.35  5394.8 1305.50  5435.2 1313.89  5545.8 1323.63
#Mann=3,-1,0
  4678.0    0.15       0  4975.0    0.05       0  5025.0    0.15       0
Bank Sta=4975,5025
XS Rating Curve= 0
Exp/Cntr=0.3,0.1

Type RM Length L Ch R = 1,117500,500,500,500
BEGIN DESCRIPTION:
Chauga River 235.0
END DESCRIPTION:
XS GIS Cut Line= 3
      1334356.37      1080036.87      1333919.72      1080245.87
      1333446.54      1080521.91
#Sta/Elev= 30
  4515.9 1335.27  4616.6 1315.69  4728.9 1278.68  4730.5 1279.23  4731.1 1283.02
  4737.3 1277.59  4753.4 1271.37  4775.8 1267.59  4818.6 1274.34  4836.2 1273.83
  4902.7 1257.16  4911.0 1254.21  4970.9 1217.60  4975.0 1209.51  4975.5 1208.51
  5025.0 1209.51  5054.8 1210.33  5076.6 1217.81  5097.6 1229.25  5114.7 1246.10
  5156.4 1274.11  5159.5 1282.04  5168.3 1280.98  5185.6 1291.83  5213.2 1303.69
  5436.8 1351.74  5466.1 1355.58  5486.7 1362.68  5505.4 1363.68  5547.8 1376.46
#Mann=3,-1,0
  4515.9    0.15       0  4975.0    0.05       0  5025.0    0.15       0
Bank Sta=4975,5025
XS Rating Curve= 0
Exp/Cntr=0.3,0.1

Type RM Length L Ch R = 1,117000,500,500,500
BEGIN DESCRIPTION:
Chauga River 234.0
END DESCRIPTION:
XS GIS Cut Line= 3
      1334244.93      1079693.45      1333879.79      1079767.11
      1333455.59      1079913.37
#Sta/Elev= 30
  4627.5 1343.55  4674.5 1319.34  4718.3 1293.54  4742.4 1275.87  4803.2 1263.92
  4818.3 1255.27  4840.2 1255.13  4858.3 1248.40  4908.4 1225.32  4920.7 1211.17
  4926.0 1208.67  4926.7 1203.16  4936.2 1209.18  4950.4 1203.83  4951.6 1201.82
  4952.6 1194.77  4967.9 1213.80  4973.0 1206.17  4975.0 1194.77  4975.5 1193.77
  5025.0 1194.77  5038.6 1205.81  5064.3 1209.05  5139.5 1204.54  5153.8 1209.98
  5219.2 1212.64  5250.8 1221.87  5320.6 1257.30  5424.0 1323.59  5448.7 1328.49
#Mann=3,-1,0
  4627.5    0.15       0  4975.0    0.05       0  5025.0    0.15       0
Bank Sta=4975,5025
XS Rating Curve= 0
Exp/Cntr=0.3,0.1

Type RM Length L Ch R = 1,116500,500,500,500
BEGIN DESCRIPTION:
Chauga River 233.0
END DESCRIPTION:
XS GIS Cut Line= 3
      1333916.52      1079300.03      1333535.70      1079416.75
      1333320.07      1079553.06
#Sta/Elev= 30
  4601.7 1400.66  4662.7 1373.25  4709.0 1359.28  4780.9 1331.54  4804.2 1316.49
  4825.8 1307.51  4877.7 1278.18  4878.5 1274.74  4879.6 1237.11  4890.9 1239.88
  4895.2 1236.42  4904.6 1237.93  4918.7 1248.92  4919.8 1239.00  4938.3 1216.22
  4949.5 1212.54  4958.9 1223.07  4974.1 1206.06  4974.4 1191.91  4974.9 1190.91
  5025.6 1191.91  5034.8 1195.40  5035.6 1211.42  5036.1 1207.64  5042.9 1191.95
  5097.6 1231.28  5186.9 1284.48  5223.3 1296.05  5237.4 1296.22  5255.1 1289.42
#Mann=3,-1,0
  4601.7    0.15       0  4974.4    0.05       0  5025.6    0.15       0
Bank Sta=4974.4,5025.6
XS Rating Curve= 0
Exp/Cntr=0.3,0.1

Type RM Length L Ch R = 1,116000,500,500,500
BEGIN DESCRIPTION:
Chauga River 232.0
END DESCRIPTION:
XS GIS Cut Line= 3
      1333606.25      1078815.01      1333188.36      1079062.15
      1332829.02      1079312.07
#Sta/Elev= 30
  4514.5 1462.46  4558.4 1450.87  4617.7 1421.70  4707.0 1364.26  4834.6 1294.73
  4915.5 1241.81  4928.6 1239.85  4952.2 1210.95  4957.2 1199.31  4961.1 1203.71
  4973.2 1199.96  4973.6 1187.58  4974.4 1187.58  4974.9 1186.58  5025.6 1187.58
  5029.6 1188.11  5032.7 1206.29  5035.5 1188.39  5041.6 1188.46  5111.1 1242.67
  5133.0 1244.76  5223.1 1305.08  5258.2 1319.96  5295.1 1322.13  5296.9 1317.35
  5325.2 1308.47  5338.5 1324.74  5353.2 1306.61  5357.2 1297.12  5437.7 1270.76
#Mann=3,-1,0
  4514.5    0.15       0  4974.4    0.05       0  5025.6    0.15       0
Bank Sta=4974.4,5025.6
XS Rating Curve= 0
Exp/Cntr=0.3,0.1

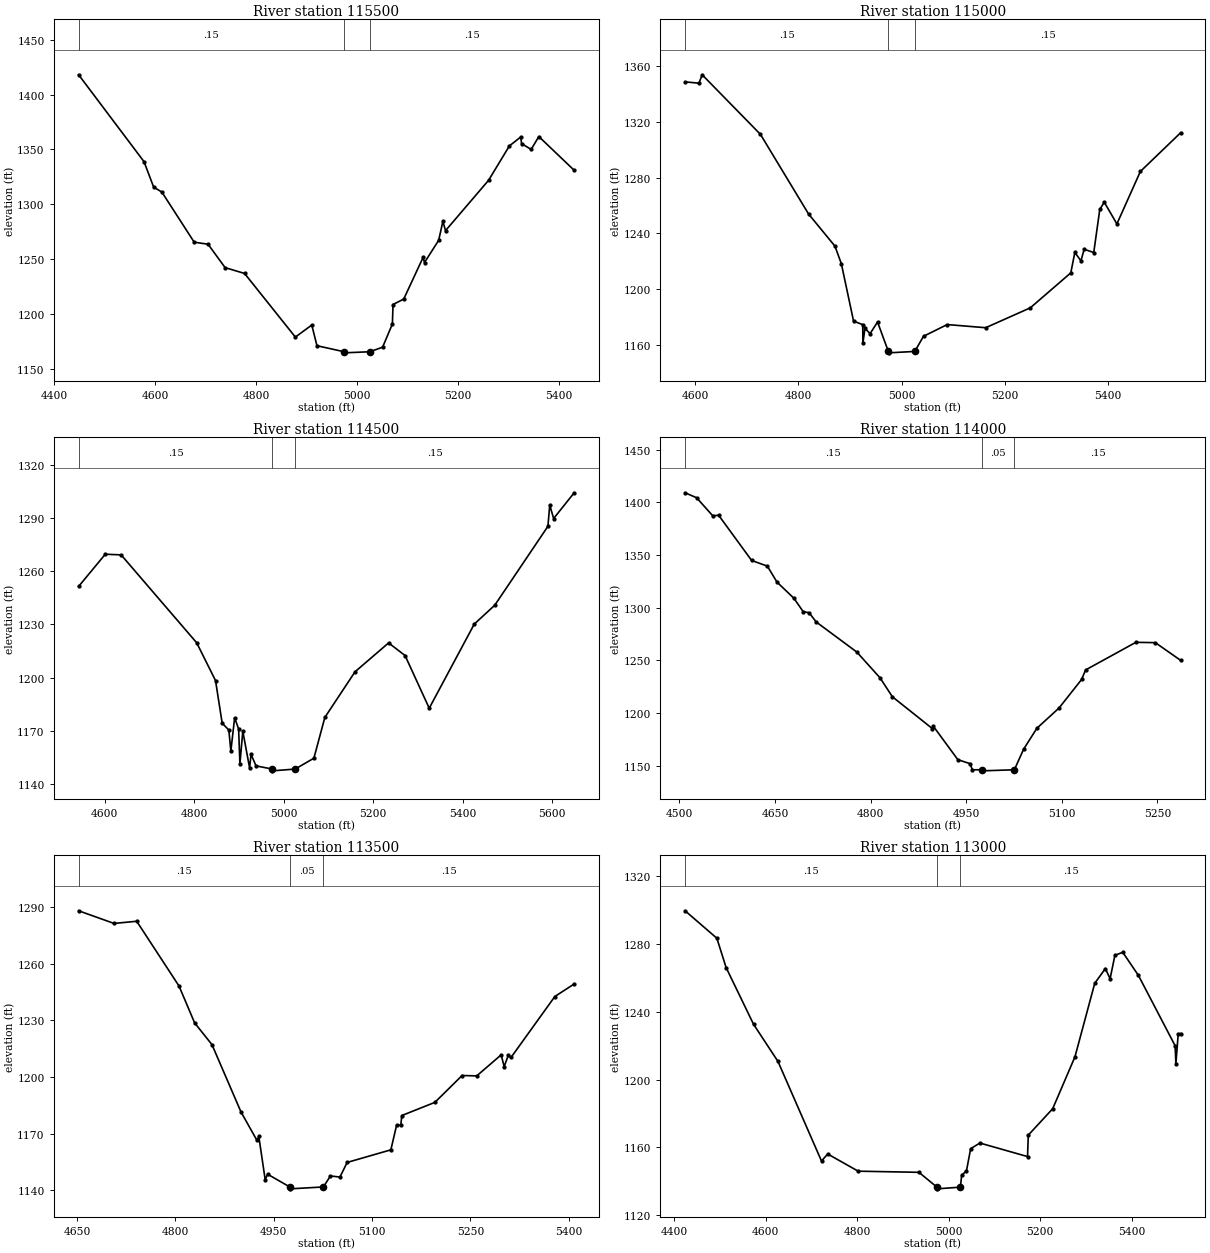
Type RM Length L Ch R = 1,115500,500,500,500
BEGIN DESCRIPTION:
Chauga River 231.0
END DESCRIPTION:
XS GIS Cut Line= 3
      1333509.81      1078435.45      1332994.08      1078631.41
      1332624.14      1078851.18
#Sta/Elev= 30
  4448.3 1418.12  4577.9 1338.82  4596.9 1315.68  4613.3 1311.05  4677.3 1265.37
  4704.8 1263.48  4738.6 1242.13  4777.1 1236.83  4877.8 1178.75  4910.3 1189.75
  4920.6 1170.88  4974.4 1165.38  4974.9 1164.38  5025.6 1165.38  5050.7 1169.56
  5070.1 1190.76  5071.3 1208.48  5092.5 1213.43  5130.9 1251.45  5133.7 1246.80
  5161.8 1267.08  5170.1 1284.30  5175.4 1275.90  5260.8 1321.90  5301.9 1353.20
  5324.3 1361.30  5326.1 1355.30  5345.0 1350.01  5360.3 1361.74  5430.3 1330.97
#Mann=3,-1,0
  4448.3    0.15       0  4974.4    0.05       0  5025.6    0.15       0
Bank Sta=4974.4,5025.6
XS Rating Curve= 0
Exp/Cntr=0.3,0.1

Type RM Length L Ch R = 1,115000,500,500,500
BEGIN DESCRIPTION:
Chauga River 230.0
END DESCRIPTION:
XS GIS Cut Line= 3
      1333091.08      1077842.01      1332840.37      1078178.73
      1332509.69      1078607.15
#Sta/Elev= 30
  4580.2 1348.43  4607.1 1347.48  4613.3 1353.50  4726.3 1310.89  4819.7 1253.86
  4870.9 1230.86  4883.2 1218.35  4906.9 1177.27  4924.7 1174.73  4925.0 1161.44
  4929.0 1172.12  4938.9 1168.28  4953.4 1176.63  4974.4 1155.57  4974.9 1154.57
  5025.6 1155.57  5042.6 1166.42  5088.5 1174.80  5163.1 1172.54  5249.7 1186.78
  5328.2 1211.79  5336.0 1226.39  5347.9 1220.41  5354.1 1228.66  5372.7 1226.35
  5384.4 1257.16  5393.1 1262.33  5417.6 1246.80  5463.1 1284.33  5541.2 1312.02
#Mann=3,-1,0
  4580.2    0.15       0  4974.4    0.05       0  5025.6    0.15       0
Bank Sta=4974.4,5025.6
XS Rating Curve= 0
Exp/Cntr=0.3,0.1

Type RM Length L Ch R = 1,114500,500,500,500
BEGIN DESCRIPTION:
Chauga River 229.0
END DESCRIPTION:
XS GIS Cut Line= 3
      1332741.63      1077811.87      1332357.86      1078062.57
      1331856.02      1078474.58
#Sta/Elev= 30
  4541.6 1251.45  4601.2 1269.60  4636.6 1269.24  4805.5 1219.65  4847.6 1198.33
  4862.5 1174.29  4877.3 1170.44  4881.9 1158.66  4890.3 1177.27  4899.2 1171.11
  4902.1 1151.51  4908.6 1169.75  4923.8 1149.03  4927.0 1156.76  4938.1 1150.23
  4974.4 1148.42  4974.9 1147.42  5025.6 1148.42  5067.5 1154.55  5092.0 1177.57
  5159.6 1203.34  5234.5 1219.57  5271.3 1212.45  5325.3 1182.74  5426.0 1230.20
  5471.8 1240.84  5590.6 1285.34  5594.7 1297.31  5603.4 1289.75  5649.3 1304.26
#Mann=3,-1,0
  4541.6    0.15       0  4974.4    0.05       0  5025.6    0.15       0
Bank Sta=4974.4,5025.6
XS Rating Curve= 0
Exp/Cntr=0.3,0.1

Type RM Length L Ch R = 1,114000,500,500,500
BEGIN DESCRIPTION:
Chauga River 228.0
END DESCRIPTION:
XS GIS Cut Line= 3
      1332886.22      1077486.52      1332404.04      1077580.21
      1332118.11      1077599.78
#Sta/Elev= 30
  4508.8 1409.19  4526.9 1404.47  4552.1 1387.41  4561.5 1387.81  4613.2 1344.96
  4637.9 1339.56  4653.1 1324.35  4679.6 1309.04  4694.0 1296.48  4703.6 1295.23
  4714.4 1286.64  4778.3 1258.01  4814.8 1233.50  4834.2 1215.52  4896.9 1185.35
  4898.2 1187.76  4936.9 1155.84  4955.8 1152.10  4959.8 1146.23  4974.4 1146.23
  4974.9 1145.23  5025.6 1146.23  5040.3 1165.95  5061.0 1185.67  5095.7 1204.85
  5131.2 1232.00  5137.4 1240.99  5216.3 1267.23  5246.9 1266.92  5286.6 1250.11
#Mann=3,-1,0
  4508.8    0.15       0  4974.4    0.05       0  5025.6    0.15       0
Bank Sta=4974.4,5025.6
XS Rating Curve= 0
Exp/Cntr=0.3,0.1

Type RM Length L Ch R = 1,113500,500,500,500
BEGIN DESCRIPTION:
Chauga River 227.0
END DESCRIPTION:
XS GIS Cut Line= 3
      1332271.70      1076888.24      1332140.67      1077210.42
      1332027.70      1077602.78
#Sta/Elev= 30
  4652.2 1288.13  4706.2 1281.42  4740.8 1282.57  4805.4 1248.21  4829.2 1228.68
  4855.6 1217.18  4899.9 1181.47  4924.3 1166.36  4927.1 1168.49  4936.9 1145.44
  4940.5 1148.44  4974.4 1141.68  4974.9 1140.68  5025.6 1141.68  5036.4 1147.50
  5050.9 1146.93  5061.9 1154.68  5128.6 1161.36  5137.3 1174.34  5143.8 1174.51
  5145.3 1179.55  5195.7 1186.52  5237.3 1200.78  5259.6 1200.57  5296.9 1211.72
  5301.5 1205.50  5307.7 1211.42  5312.0 1210.37  5378.8 1242.67  5408.3 1249.31
#Mann=3,-1,0
  4652.2    0.15       0  4974.4    0.05       0  5025.6    0.15       0
Bank Sta=4974.4,5025.6
XS Rating Curve= 0
Exp/Cntr=0.3,0.1

Type RM Length L Ch R = 1,113000,500,500,500
BEGIN DESCRIPTION:
Chauga River 226.0
END DESCRIPTION:
XS GIS Cut Line= 3
      1331813.80      1076557.49      1331654.43      1077111.63
      1331449.28      1077575.71
#Sta/Elev= 30
  4423.4 1299.41  4492.9 1283.23  4513.1 1265.98  4573.1 1232.57  4626.6 1210.64
  4721.8 1151.98  4735.3 1156.16  4802.0 1146.02  4934.9 1145.35  4974.4 1136.62
  4974.9 1135.62  5025.6 1136.62  5028.4 1143.64  5038.9 1146.22  5048.1 1159.31
  5068.4 1162.59  5172.5 1154.62  5174.1 1167.25  5227.5 1182.80  5276.2 1213.37
  5319.5 1256.69  5342.7 1265.37  5353.1 1259.41  5363.6 1273.17  5380.8 1274.96
  5415.0 1261.35  5495.4 1219.87  5497.0 1209.14  5502.1 1226.96  5507.4 1227.09
#Mann=3,-1,0
  4423.4    0.15       0  4974.4    0.05       0  5025.6    0.15       0
Bank Sta=4974.4,5025.6
XS Rating Curve= 0
Exp/Cntr=0.3,0.1

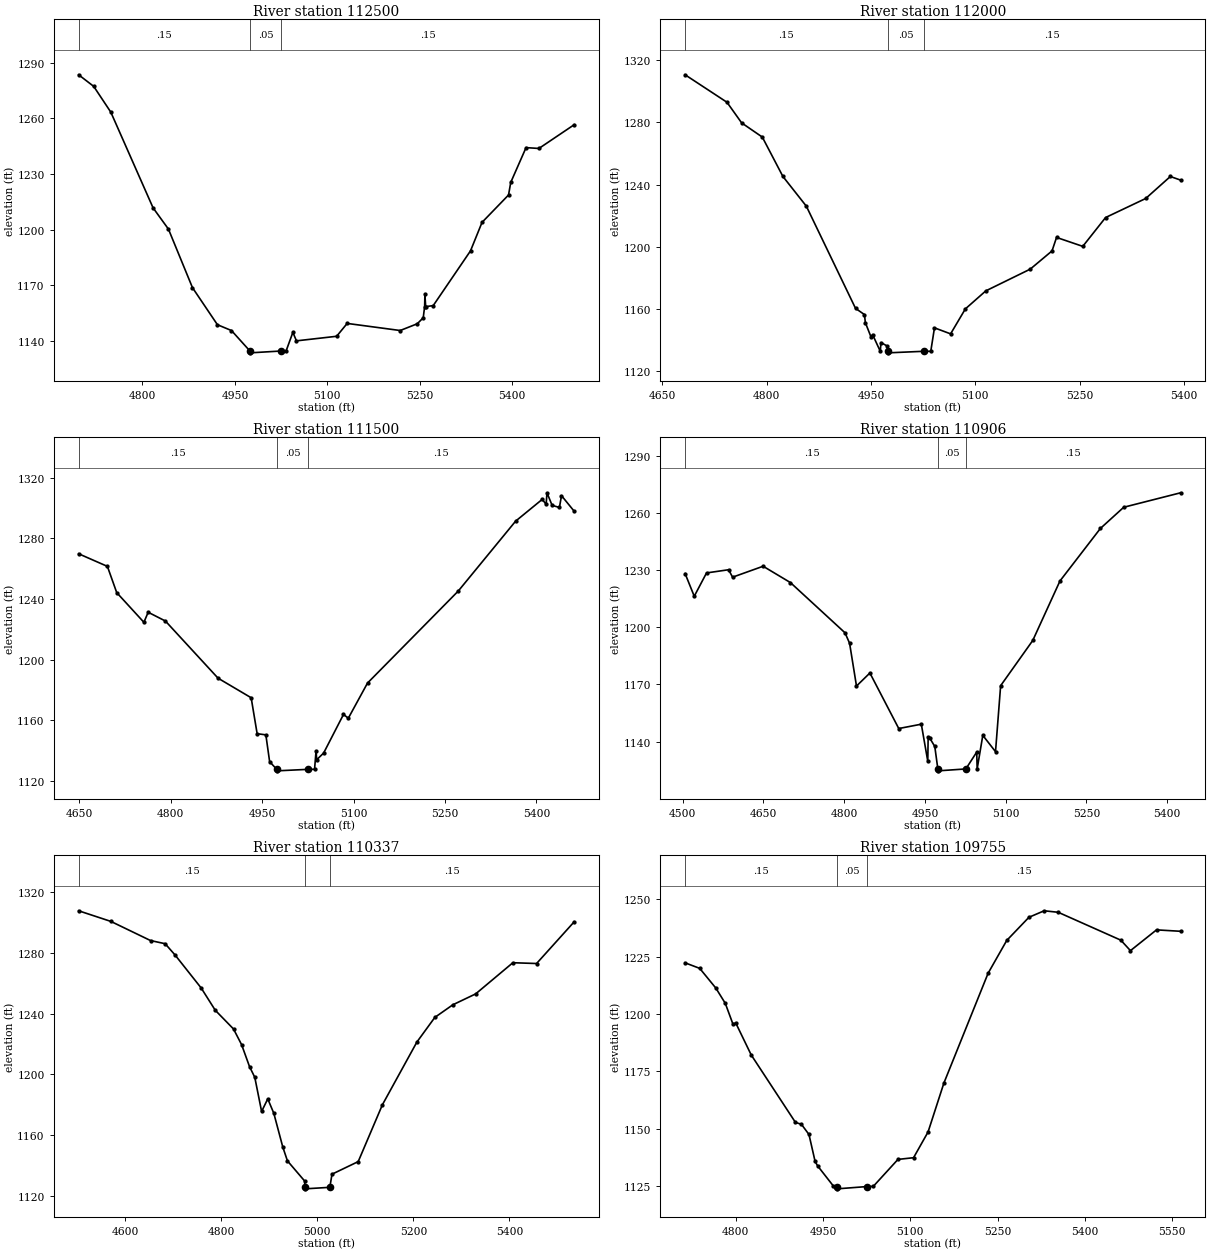
Type RM Length L Ch R = 1,112500,500,500,500
BEGIN DESCRIPTION:
Chauga River 225.0
END DESCRIPTION:
XS GIS Cut Line= 3
      1331298.68      1076569.48      1331229.36      1076864.96
      1331093.82      1077346.76
#Sta/Elev= 30
  4696.5 1283.40  4721.0 1277.14  4748.7 1263.27  4817.3 1211.68  4842.2 1200.25
  4881.2 1168.69  4921.7 1148.72  4944.5 1145.58  4974.4 1134.57  4974.9 1133.57
  5025.6 1134.57  5033.1 1134.57  5044.1 1144.61  5049.9 1140.03  5115.1 1142.49
  5132.2 1149.42  5218.2 1145.60  5245.9 1149.23  5255.6 1152.46  5257.9 1158.51
  5258.3 1165.01  5259.6 1158.47  5271.8 1159.02  5332.3 1188.52  5351.0 1203.87
  5394.0 1218.62  5397.6 1225.41  5422.4 1244.15  5443.3 1243.70  5500.5 1256.49
#Mann=3,-1,0
  4696.5    0.15       0  4974.4    0.05       0  5025.6    0.15       0
Bank Sta=4974.4,5025.6
XS Rating Curve= 0
Exp/Cntr=0.3,0.1

Type RM Length L Ch R = 1,112000,500,500,500
BEGIN DESCRIPTION:
Chauga River 224.0
END DESCRIPTION:
XS GIS Cut Line= 3
      1331123.90      1076515.31      1330830.74      1076636.70
      1330470.27      1076798.45
#Sta/Elev= 30
  4682.7 1310.55  4742.9 1292.88  4764.0 1279.62  4793.7 1270.50  4823.3 1245.19
  4857.0 1226.08  4927.7 1160.41  4940.6 1156.36  4941.8 1151.27  4949.8 1142.18
  4952.2 1143.55  4963.3 1132.80  4964.3 1138.42  4973.3 1136.14  4974.0 1132.80
  4974.5 1131.80  5026.0 1132.80  5035.9 1132.80  5041.2 1147.87  5064.4 1144.00
  5085.6 1160.04  5115.0 1171.63  5178.9 1185.61  5210.2 1197.32  5216.7 1205.99
  5254.4 1200.25  5287.2 1218.78  5344.9 1231.03  5380.3 1245.16  5395.1 1242.83
#Mann=3,-1,0
  4682.7    0.15       0  4974.0    0.05       0  5026.0    0.15       0
Bank Sta=4974,5026
XS Rating Curve= 0
Exp/Cntr=0.3,0.1

Type RM Length L Ch R = 1,111500,594,594,594
BEGIN DESCRIPTION:
Chauga River 223.0
END DESCRIPTION:
XS GIS Cut Line= 3
      1330789.55      1076104.39      1330483.83      1076277.04
      1330102.71      1076538.18
#Sta/Elev= 30
  4648.9 1269.84  4696.1 1261.51  4711.4 1244.18  4756.0 1224.58  4763.0 1231.22
  4791.3 1225.42  4877.7 1187.67  4932.0 1174.76  4941.8 1151.03  4956.1 1150.26
  4962.3 1132.55  4974.0 1127.50  4974.5 1126.50  5026.0 1127.50  5036.0 1127.50
  5038.5 1139.76  5039.5 1133.82  5050.9 1138.24  5083.5 1163.75  5091.4 1161.25
  5122.9 1184.46  5271.8 1245.22  5365.9 1291.37  5409.6 1305.76  5416.0 1302.49
  5417.4 1310.11  5425.8 1301.82  5437.8 1300.40  5441.2 1308.22  5462.0 1297.93
#Mann=3,-1,0
  4648.9    0.15       0  4974.0    0.05       0  5026.0    0.15       0
Bank Sta=4974,5026
XS Rating Curve= 0
Exp/Cntr=0.3,0.1

Type RM Length L Ch R = 1,110906,569,569,569
BEGIN DESCRIPTION:
Chauga River 222.0
END DESCRIPTION:
XS GIS Cut Line= 3
      1330554.58      1075715.78      1330076.28      1075844.83
      1329683.96      1076007.99
#Sta/Elev= 30
  4504.6 1228.17  4521.6 1216.25  4544.4 1228.49  4585.4 1230.17  4592.8 1226.26
  4649.5 1232.00  4700.2 1223.43  4801.6 1197.06  4810.1 1191.56  4822.9 1169.11
  4847.8 1175.96  4901.4 1146.81  4943.3 1149.09  4955.3 1129.66  4956.0 1142.50
  4958.6 1141.95  4968.3 1137.40  4974.0 1125.60  4974.5 1124.60  5026.0 1125.60
  5046.2 1134.45  5047.0 1125.60  5057.5 1143.22  5081.1 1134.66  5090.6 1169.29
  5150.3 1193.05  5200.8 1224.28  5275.9 1251.85  5319.2 1262.97  5424.9 1270.57
#Mann=3,-1,0
  4504.6    0.15       0  4974.0    0.05       0  5026.0    0.15       0
Bank Sta=4974,5026
XS Rating Curve= 0
Exp/Cntr=0.3,0.1

Type RM Length L Ch R = 1,110337,582,582,582
BEGIN DESCRIPTION:
Chauga River 221.0
END DESCRIPTION:
XS GIS Cut Line= 3
      1330374.96      1075225.01      1329887.01      1075320.45
      1329388.79      1075515.13
#Sta/Elev= 30
  4502.8 1307.68  4569.9 1300.69  4652.5 1288.10  4683.0 1286.01  4703.8 1278.53
  4758.1 1256.85  4787.4 1242.21  4825.4 1229.90  4842.3 1219.54  4858.7 1205.17
  4869.7 1198.09  4883.9 1175.62  4896.7 1183.93  4909.3 1174.46  4928.0 1152.25
  4937.7 1143.13  4973.6 1129.85  4974.0 1125.73  4974.5 1124.73  5026.0 1125.73
  5030.5 1134.37  5085.1 1142.65  5135.5 1180.05  5207.3 1221.30  5244.7 1237.53
  5282.1 1245.81  5329.7 1252.99  5407.2 1273.50  5456.6 1272.98  5534.9 1300.42
#Mann=3,-1,0
  4502.8    0.15       0  4974.0    0.05       0  5026.0    0.15       0
Bank Sta=4974,5026
XS Rating Curve= 0
Exp/Cntr=0.3,0.1

Type RM Length L Ch R = 1,109755,419,419,419
BEGIN DESCRIPTION:
Chauga River 220.0
END DESCRIPTION:
XS GIS Cut Line= 3
      1329879.77      1074803.59      1329593.59      1074818.99
      1329042.36      1074939.75
#Sta/Elev= 30
  4713.4 1222.24  4738.5 1219.83  4766.2 1211.23  4782.4 1204.59  4795.4 1195.65
  4800.5 1195.96  4827.0 1182.06  4902.9 1152.68  4913.1 1151.87  4926.1 1147.43
  4936.6 1135.70  4940.9 1133.76  4967.8 1125.02  4974.0 1124.73  4974.5 1123.73
  5026.0 1124.73  5036.5 1124.79  5078.9 1136.56  5105.7 1137.30  5130.6 1148.52
  5157.8 1169.85  5233.7 1217.70  5265.7 1232.00  5303.8 1242.09  5330.0 1244.93
  5354.1 1244.27  5461.6 1232.12  5478.1 1227.55  5522.9 1236.61  5564.3 1235.99
#Mann=3,-1,0
  4713.4    0.15       0  4974.0    0.05       0  5026.0    0.15       0
Bank Sta=4974,5026
XS Rating Curve= 0
Exp/Cntr=0.3,0.1

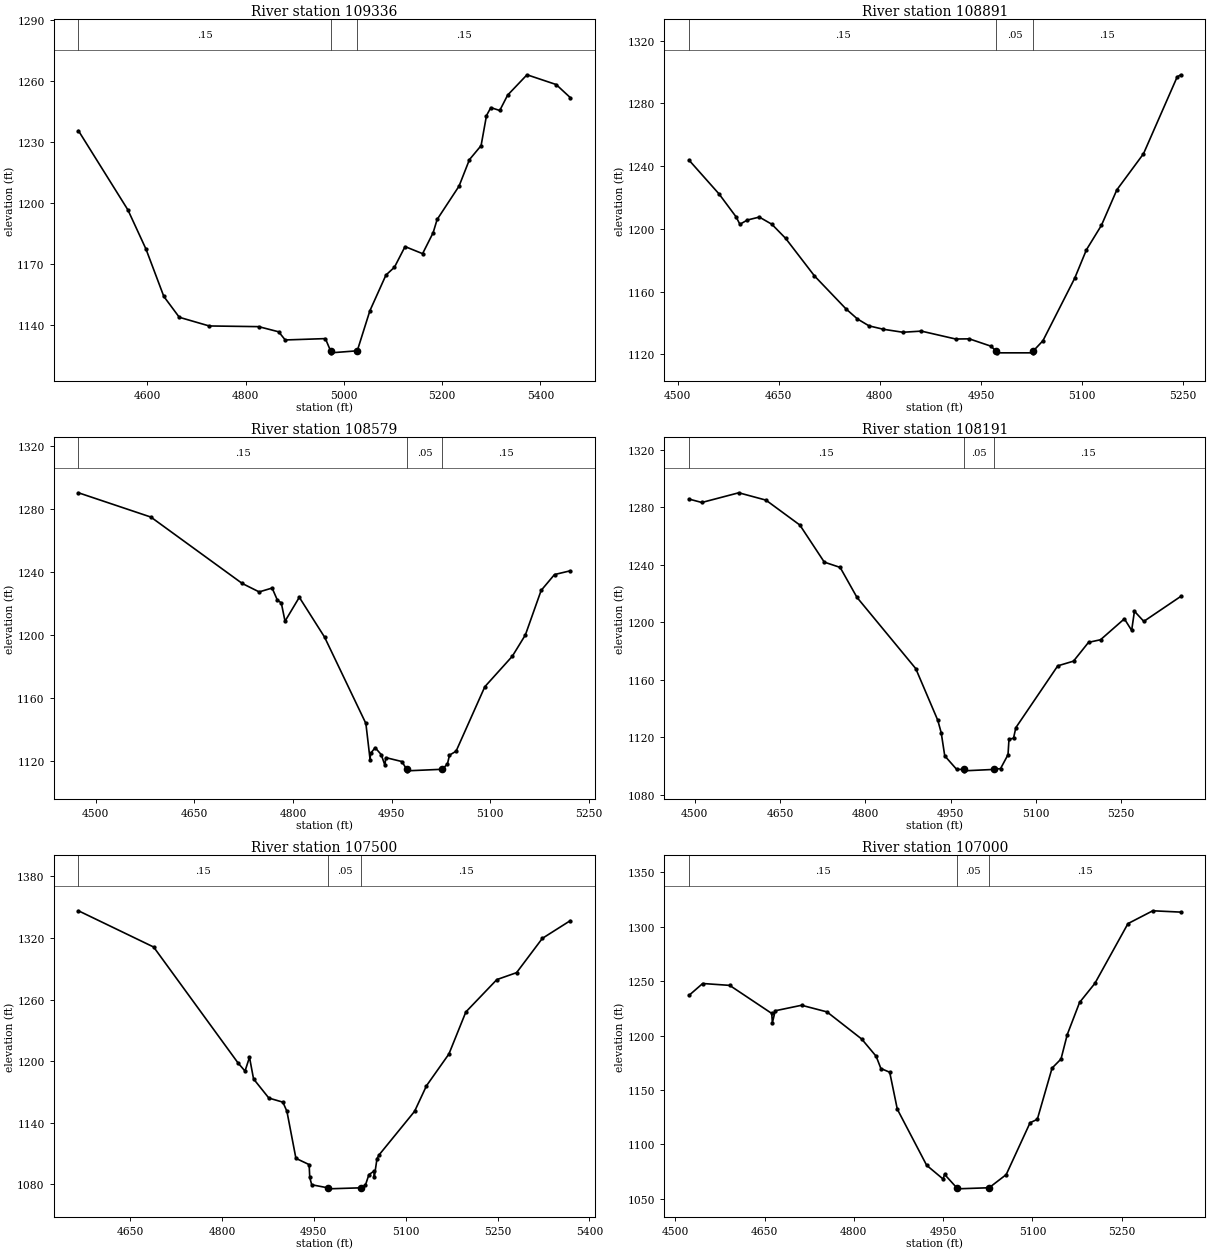
Type RM Length L Ch R = 1,109336,445,445,445
BEGIN DESCRIPTION:
Chauga River 219.0
END DESCRIPTION:
XS GIS Cut Line= 3
      1329943.05      1074779.49      1329537.52      1074422.16
      1329141.80      1074186.07
#Sta/Elev= 30
  4459.5 1235.55  4560.2 1196.61  4597.1 1177.29  4633.3 1154.07  4664.8 1143.81
  4725.7 1139.54  4826.5 1139.20  4867.2 1136.66  4880.5 1132.65  4962.3 1133.32
  4972.8 1127.32  4973.3 1126.32  5027.2 1127.32  5052.9 1147.02  5085.6 1164.57
  5102.9 1168.41  5124.5 1178.57  5160.2 1175.09  5181.7 1185.40  5189.8 1191.89
  5234.4 1208.29  5255.6 1221.33  5279.3 1228.20  5290.3 1242.97  5299.1 1246.91
  5317.3 1245.49  5333.4 1253.06  5372.8 1263.05  5432.1 1258.26  5460.8 1251.85
#Mann=3,-1,0
  4459.5    0.15       0  4972.8    0.05       0  5027.2    0.15       0
Bank Sta=4972.8,5027.2
XS Rating Curve= 0
Exp/Cntr=0.3,0.1

Type RM Length L Ch R = 1,108891,312,312,312
BEGIN DESCRIPTION:
Chauga River 218.0
END DESCRIPTION:
XS GIS Cut Line= 3
      1329982.21      1074779.46      1329931.58      1074299.22
      1329949.08      1074053.44
#Sta/Elev= 30
  4517.1 1243.79  4561.7 1222.22  4586.8 1207.71  4592.5 1202.95  4603.6 1205.66
  4621.3 1207.54  4639.9 1202.96  4660.3 1193.99  4703.1 1170.05  4749.8 1149.07
  4766.7 1142.67  4784.0 1138.23  4805.3 1136.06  4834.2 1134.16  4861.6 1134.89
  4912.5 1129.86  4932.7 1129.96  4964.6 1125.32  4972.8 1122.05  4973.3 1121.05
  5026.7 1121.05  5027.2 1122.05  5041.9 1128.77  5089.0 1168.55  5106.4 1186.70
  5128.7 1202.32  5151.5 1224.87  5191.0 1247.85  5241.0 1296.86  5246.4 1298.19
#Mann=3,-1,0
  4517.1    0.15       0  4972.8    0.05       0  5027.2    0.15       0
Bank Sta=4972.8,5027.2
XS Rating Curve= 0
Exp/Cntr=0.3,0.1

Type RM Length L Ch R = 1,108579,388,388,388
BEGIN DESCRIPTION:
Chauga River 217.0
END DESCRIPTION:
XS GIS Cut Line= 3
      1330391.90      1074783.08      1330235.99      1074280.61
      1330181.04      1074066.14
#Sta/Elev= 30
  4473.9 1290.40  4584.0 1274.95  4722.9 1232.72  4748.6 1227.36  4768.3 1229.82
  4776.3 1222.11  4782.2 1220.42  4787.9 1208.73  4809.6 1223.94  4848.0 1198.61
  4910.8 1143.70  4917.2 1120.69  4917.9 1124.62  4924.9 1128.31  4934.1 1123.89
  4939.8 1117.02  4941.0 1121.99  4965.5 1119.48  4972.8 1114.57  4973.3 1113.57
  5027.2 1114.57  5034.8 1118.04  5037.9 1123.54  5047.9 1126.06  5091.6 1167.06
  5133.4 1186.46  5153.2 1199.97  5177.2 1228.31  5197.5 1238.40  5221.4 1240.77
#Mann=3,-1,0
  4473.9    0.15       0  4972.8    0.05       0  5027.2    0.15       0
Bank Sta=4972.8,5027.2
XS Rating Curve= 0
Exp/Cntr=0.3,0.1

Type RM Length L Ch R = 1,108191,691,691,691
BEGIN DESCRIPTION:
Chauga River 216.0
END DESCRIPTION:
XS GIS Cut Line= 3
      1330904.04      1074596.33      1330587.93      1074196.11
      1330265.43      1074047.48
#Sta/Elev= 30
  4490.0 1285.57  4512.5 1283.21  4577.5 1289.95  4625.2 1284.86  4684.9 1267.55
  4727.9 1241.79  4755.8 1238.11  4785.4 1217.30  4888.8 1167.84  4927.6 1131.90
  4933.6 1123.27  4939.8 1107.23  4960.8 1097.83  4972.8 1097.83  4973.3 1096.83
  5027.2 1097.83  5038.0 1098.42  5051.1 1108.04  5052.8 1118.71  5060.8 1119.52
  5064.9 1126.84  5138.6 1169.75  5166.3 1173.01  5192.7 1186.05  5213.9 1187.89
  5255.8 1202.41  5268.6 1194.36  5273.5 1207.68  5290.0 1200.64  5355.1 1218.01
#Mann=3,-1,0
  4490.0    0.15       0  4972.8    0.05       0  5027.2    0.15       0
Bank Sta=4972.8,5027.2
XS Rating Curve= 0
Exp/Cntr=0.3,0.1

Type RM Length L Ch R = 1,107500,500,500,500
BEGIN DESCRIPTION:
Chauga River 215.0
END DESCRIPTION:
XS GIS Cut Line= 3
      1331283.61      1074047.46      1331034.02      1073692.04
      1330801.62      1073405.81
#Sta/Elev= 30
  4565.7 1346.36  4688.5 1311.08  4826.5 1198.09  4837.7 1190.35  4845.0 1203.81
  4851.6 1182.74  4876.6 1164.09  4899.5 1160.10  4906.1 1151.22  4920.8 1105.42
  4942.4 1099.32  4943.4 1086.80  4946.6 1079.71  4972.8 1076.74  4973.3 1075.74
  5027.2 1076.74  5034.2 1079.18  5040.0 1089.59  5048.1 1092.87  5048.9 1087.74
  5053.2 1105.11  5056.9 1109.00  5114.6 1151.21  5134.0 1176.06  5170.6 1206.96
  5198.3 1247.90  5248.9 1279.39  5281.1 1286.14  5323.2 1319.52  5368.7 1336.70
#Mann=3,-1,0
  4565.7    0.15       0  4972.8    0.05       0  5027.2    0.15       0
Bank Sta=4972.8,5027.2
XS Rating Curve= 0
Exp/Cntr=0.3,0.1

Type RM Length L Ch R = 1,107000,500,500,500
BEGIN DESCRIPTION:
Chauga River 214.0
END DESCRIPTION:
XS GIS Cut Line= 3
      1331542.69      1073806.49      1331395.60      1073352.84
      1331226.35      1073047.28
#Sta/Elev= 30
  4523.1 1237.01  4546.0 1247.90  4591.4 1246.17  4662.0 1220.38  4663.1 1211.78
  4667.9 1222.83  4712.2 1227.89  4754.8 1221.79  4813.2 1196.81  4837.4 1181.00
  4845.4 1169.72  4860.2 1166.30  4873.0 1132.28  4922.3 1080.71  4950.0 1068.03
  4952.3 1072.40  4972.8 1060.06  4973.3 1059.06  5027.2 1060.06  5055.9 1072.12
  5096.0 1119.82  5108.2 1122.99  5133.0 1170.11  5148.0 1178.44  5158.5 1200.92
  5179.2 1230.49  5204.9 1248.00  5260.5 1302.99  5302.2 1314.78  5349.3 1313.55
#Mann=3,-1,0
  4523.1    0.15       0  4972.8    0.05       0  5027.2    0.15       0
Bank Sta=4972.8,5027.2
XS Rating Curve= 0
Exp/Cntr=0.3,0.1