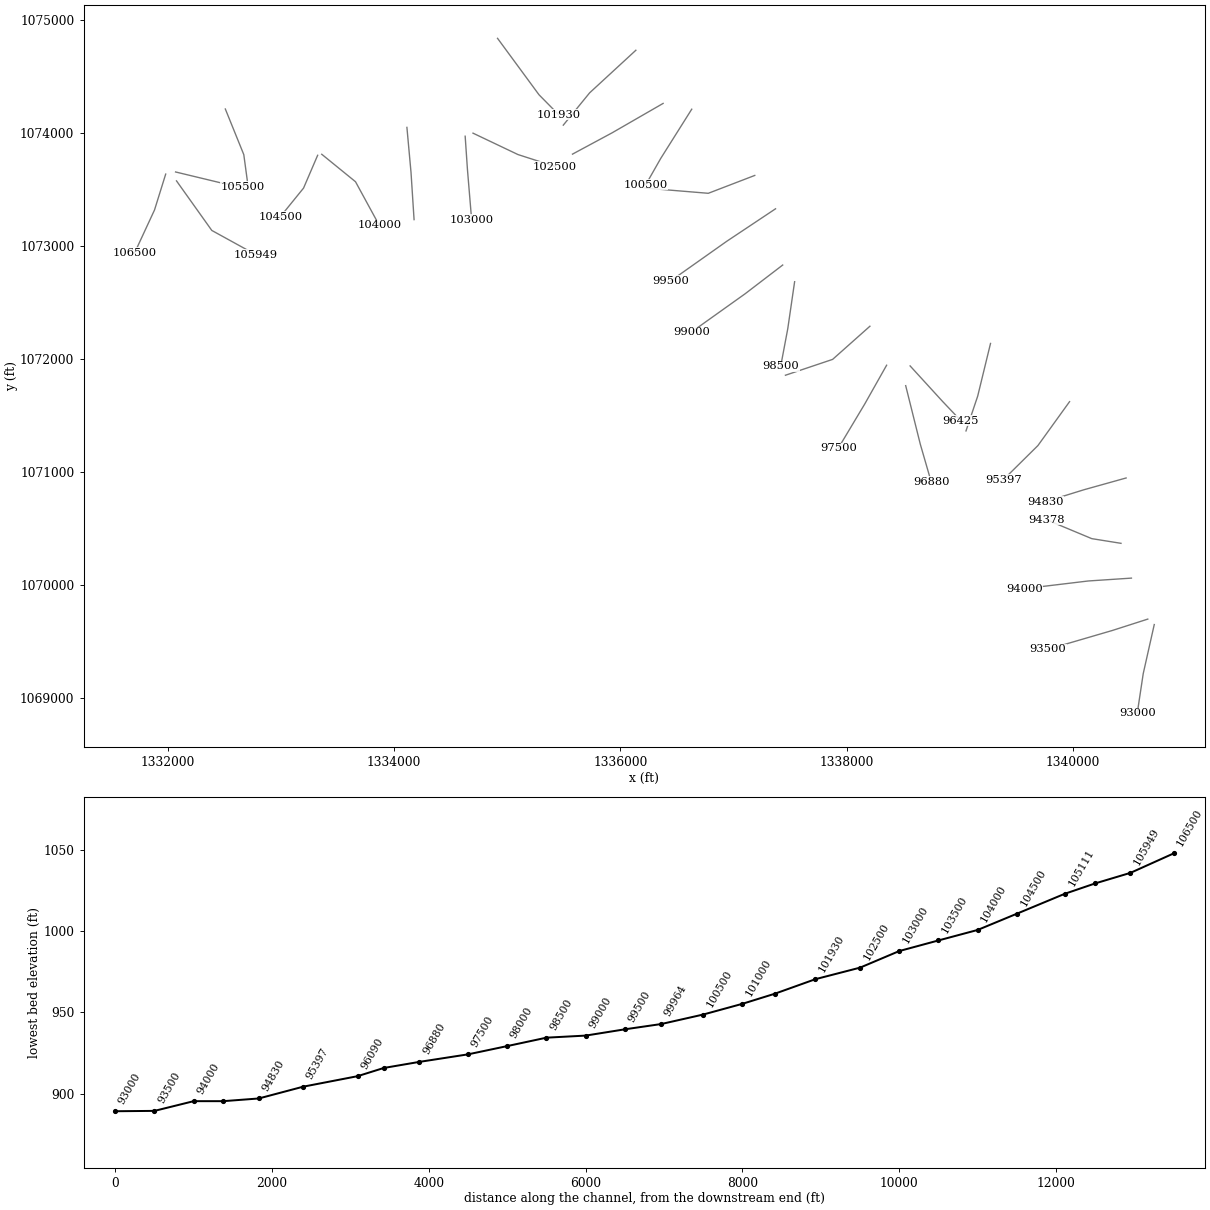
HEC-RAS study Chauga River.prj: Chauga River Limited Detail Study

--- Chauga River.g01 (geometry) --- (continued)

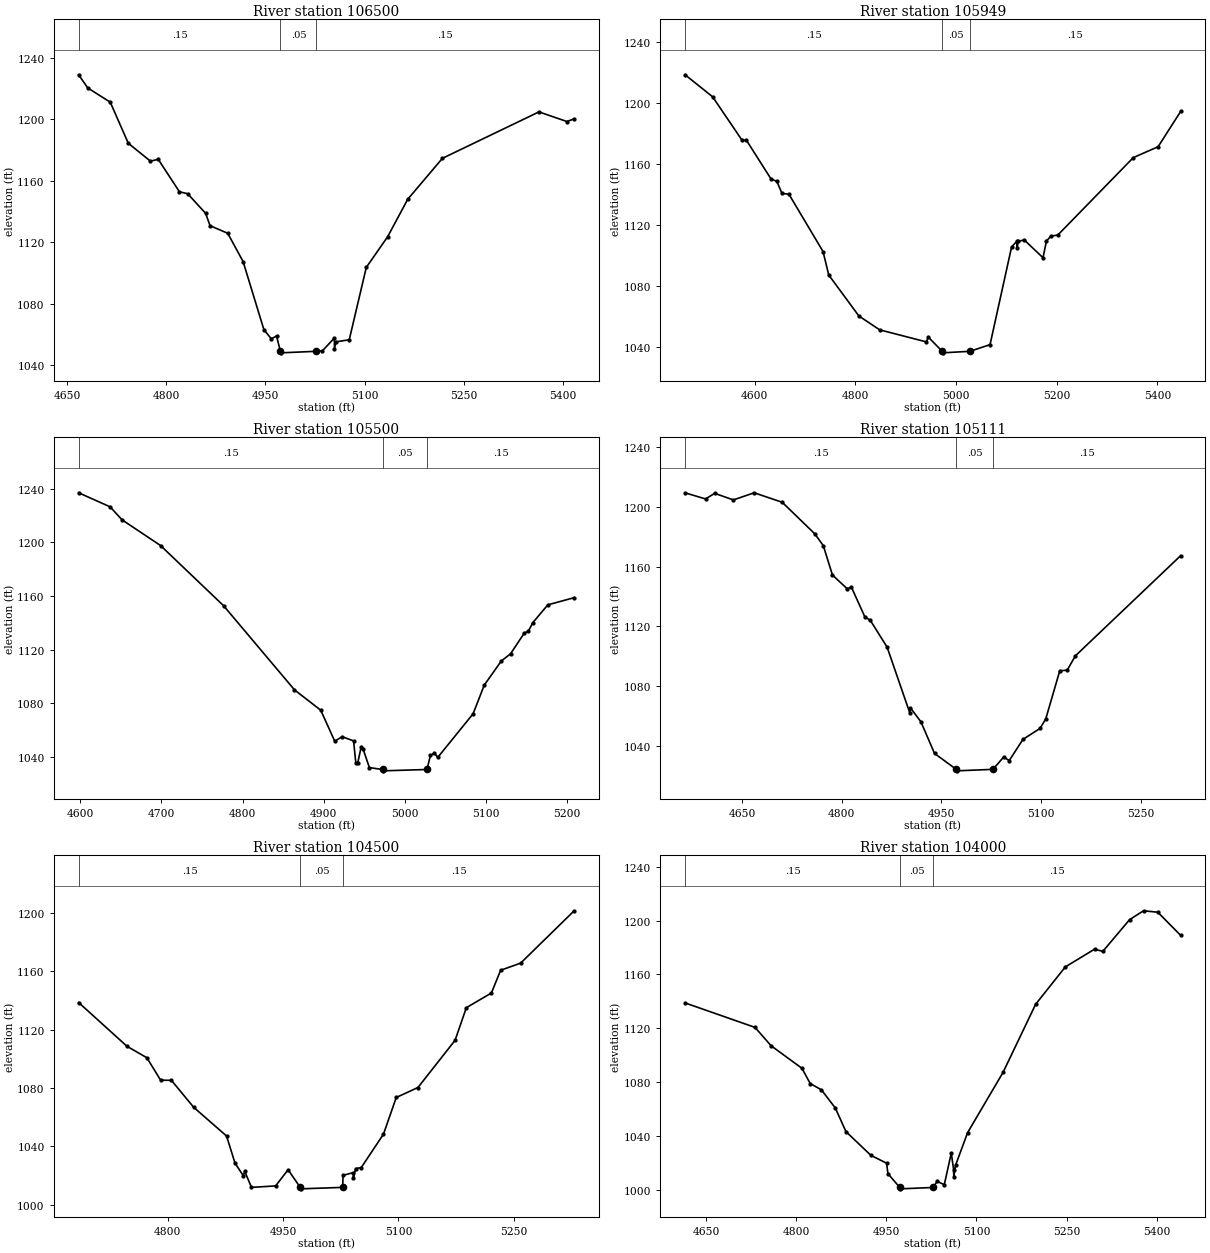
Type RM Length L Ch R = 1,106500,551,551,551
BEGIN DESCRIPTION:
Chauga River 213.0
END DESCRIPTION:
XS GIS Cut Line= 3
      1331979.48      1073635.31      1331880.69      1073317.93
      1331705.36      1072939.47
#Sta/Elev= 30
  4667.6 1229.12  4681.4 1220.55  4715.4 1211.29  4742.7 1184.54  4776.2 1172.86
  4788.0 1174.08  4820.1 1152.90  4832.5 1151.67  4859.6 1138.92  4866.4 1130.85
  4893.1 1125.90  4916.3 1107.52  4947.8 1063.18  4959.0 1057.16  4966.9 1058.98
  4972.8 1049.04  4973.3 1048.04  5027.2 1049.04  5036.2 1049.29  5054.4 1057.69
  5054.5 1050.68  5057.0 1055.23  5076.9 1056.54  5102.7 1103.69  5134.9 1123.59
  5165.3 1148.02  5217.8 1174.70  5363.8 1204.94  5406.2 1198.67  5417.1 1200.45
#Mann=3,-1,0
  4667.6    0.15       0  4972.8    0.05       0  5027.2    0.15       0
Bank Sta=4972.8,5027.2
XS Rating Curve= 0
Exp/Cntr=0.3,0.1

Type RM Length L Ch R = 1,105949,449,449,449
BEGIN DESCRIPTION:
Chauga River 212.0
END DESCRIPTION:
XS GIS Cut Line= 3
      1332074.98      1073575.03      1332387.05      1073136.54
      1332777.83      1072921.38
#Sta/Elev= 30
  4461.8 1218.30  4516.5 1203.85  4575.2 1175.26  4583.6 1175.41  4632.2 1150.15
  4644.0 1148.40  4654.4 1140.49  4667.9 1140.09  4735.8 1102.46  4747.1 1087.08
  4807.0 1060.20  4848.2 1051.14  4941.0 1043.22  4944.8 1046.37  4972.6 1037.05
  4973.1 1036.05  5027.4 1037.05  5067.5 1041.41  5110.3 1105.41  5120.8 1109.24
  5121.5 1104.52  5123.2 1109.16  5135.6 1110.02  5172.7 1098.39  5179.6 1109.40
  5188.6 1112.60  5202.0 1113.21  5352.1 1164.02  5401.3 1171.13  5446.1 1194.24
#Mann=3,-1,0
  4461.8    0.15       0  4972.6    0.05       0  5027.4    0.15       0
Bank Sta=4972.6,5027.4
XS Rating Curve= 0
Exp/Cntr=0.3,0.1

Type RM Length L Ch R = 1,105500,389,389,389
BEGIN DESCRIPTION:
Chauga River 211.0
END DESCRIPTION:
XS GIS Cut Line= 3
      1332066.84      1073654.03      1332457.85      1073559.83
      1332663.31      1073521.48
#Sta/Elev= 30
  4597.8 1237.08  4636.6 1226.60  4651.3 1216.92  4698.8 1197.73  4776.6 1152.78
  4864.0 1090.02  4896.4 1074.82  4913.7 1051.67  4922.8 1055.04  4936.9 1051.91
  4939.7 1035.41  4942.1 1035.62  4946.2 1047.15  4948.8 1045.58  4956.4 1031.99
  4972.6 1030.56  4973.1 1029.56  5027.4 1030.56  5031.7 1041.02  5036.7 1042.78
  5040.7 1039.56  5084.4 1072.21  5098.1 1093.55  5119.2 1111.58  5130.5 1116.87
  5147.6 1132.49  5152.4 1133.70  5158.1 1140.23  5176.5 1153.45  5209.0 1158.80
#Mann=3,-1,0
  4597.8    0.15       0  4972.6    0.05       0  5027.4    0.15       0
Bank Sta=4972.6,5027.4
XS Rating Curve= 0
Exp/Cntr=0.3,0.1

Type RM Length L Ch R = 1,105111,611,611,611
BEGIN DESCRIPTION:
Chauga River 210.0
END DESCRIPTION:
XS GIS Cut Line= 3
      1332506.67      1074211.37      1332670.01      1073807.55
      1332711.53      1073500.35
#Sta/Elev= 30
  4564.4 1209.45  4595.1 1205.35  4609.0 1209.10  4637.0 1204.69  4668.3 1209.48
  4710.5 1203.12  4759.2 1182.13  4772.3 1174.12  4786.1 1154.37  4808.7 1145.00
  4814.4 1146.44  4834.8 1126.39  4843.0 1124.05  4868.3 1106.10  4902.6 1061.81
  4903.5 1065.31  4919.2 1056.02  4939.7 1034.80  4972.4 1024.14  4972.9 1023.14
  5027.6 1024.14  5043.7 1032.39  5052.1 1030.00  5072.7 1044.21  5098.5 1051.59
  5107.1 1058.00  5128.1 1090.13  5139.4 1090.65  5151.6 1100.19  5310.0 1167.33
#Mann=3,-1,0
  4564.4    0.15       0  4972.4    0.05       0  5027.6    0.15       0
Bank Sta=4972.4,5027.6
XS Rating Curve= 0
Exp/Cntr=0.3,0.1

Type RM Length L Ch R = 1,104500,500,500,500
BEGIN DESCRIPTION:
Chauga River 209.0
END DESCRIPTION:
XS GIS Cut Line= 3
      1333323.07      1073801.65      1333198.54      1073511.55
      1332991.67      1073256.37
#Sta/Elev= 30
  4684.3 1138.70  4747.1 1108.68  4773.0 1100.80  4790.9 1085.42  4804.9 1085.30
  4834.0 1066.73  4876.6 1047.11  4887.6 1028.48  4898.4 1019.84  4900.2 1022.92
  4909.0 1011.86  4940.4 1012.87  4956.6 1023.97  4972.4 1011.86  4972.9 1010.86
  5027.6 1011.86  5028.0 1020.09  5041.2 1022.00  5041.5 1018.58  5044.4 1024.76
  5051.7 1025.45  5080.6 1048.38  5097.2 1073.54  5125.4 1080.37  5173.7 1112.79
  5188.3 1135.14  5220.9 1145.22  5232.9 1160.82  5258.9 1165.71  5328.5 1201.63
#Mann=3,-1,0
  4684.3    0.15       0  4972.4    0.05       0  5027.6    0.15       0
Bank Sta=4972.4,5027.6
XS Rating Curve= 0
Exp/Cntr=0.3,0.1

Type RM Length L Ch R = 1,104000,500,500,500
BEGIN DESCRIPTION:
Chauga River 208.0
END DESCRIPTION:
XS GIS Cut Line= 3
      1333359.24      1073810.65      1333657.89      1073567.53
      1333868.30      1073181.10
#Sta/Elev= 30
  4614.9 1138.85  4731.3 1120.70  4758.2 1107.03  4809.5 1090.32  4823.2 1079.04
  4841.9 1074.32  4865.0 1060.88  4882.7 1043.36  4924.2 1025.73  4950.4 1019.89
  4952.6 1012.14  4972.4 1001.85  4972.9 1000.85  5027.6 1001.85  5034.6 1006.37
  5046.5 1003.99  5058.1 1027.36  5062.0 1015.19  5062.3 1009.99  5065.3 1018.42
  5085.3 1042.57  5144.3 1087.30  5198.6 1137.88  5248.0 1165.59  5296.8 1178.79
  5310.4 1177.10  5355.1 1200.72  5378.2 1207.26  5402.0 1206.18  5440.0 1189.02
#Mann=3,-1,0
  4614.9    0.15       0  4972.4    0.05       0  5027.6    0.15       0
Bank Sta=4972.4,5027.6
XS Rating Curve= 0
Exp/Cntr=0.3,0.1

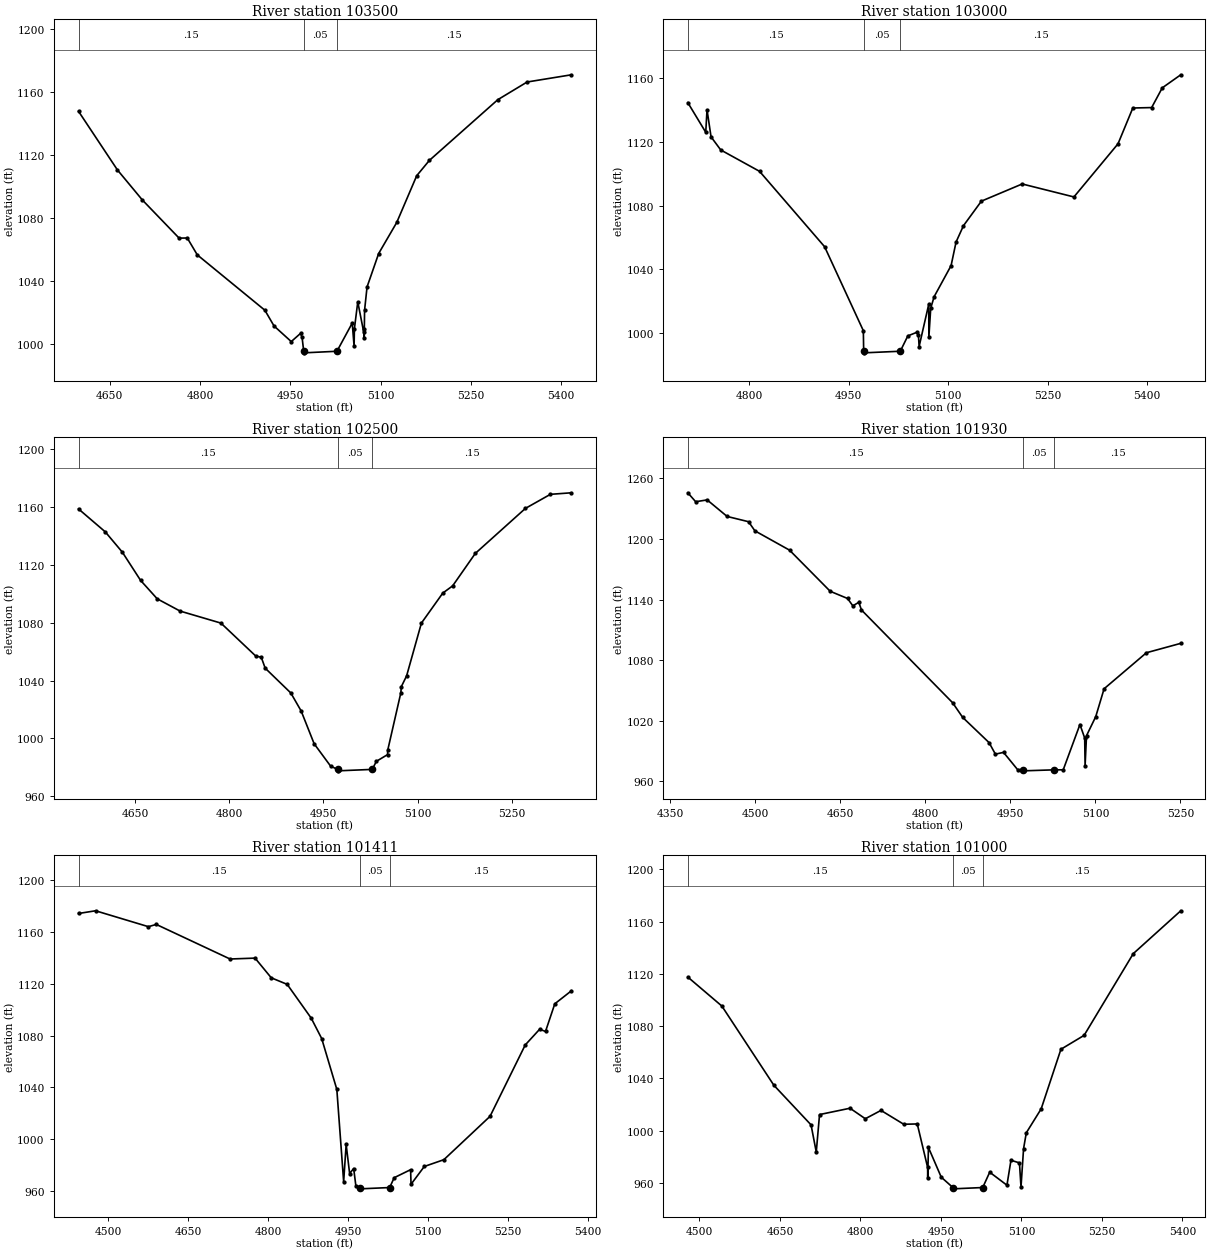
Type RM Length L Ch R = 1,103500,500,500,500
BEGIN DESCRIPTION:
Chauga River 207.0
END DESCRIPTION:
XS GIS Cut Line= 3
      1334112.33      1074048.64      1334148.73      1073648.59
      1334175.60      1073232.26
#Sta/Elev= 30
  4598.3 1147.85  4663.0 1110.56  4704.4 1091.48  4765.4 1067.27  4779.0 1067.34
  4795.6 1056.63  4907.9 1021.44  4923.1 1011.45  4951.7 1001.53  4967.1 1006.72
  4969.7 1004.21  4972.4  995.38  4972.9  994.38  5027.6  995.38  5053.0 1013.28
  5056.1  998.56  5056.6 1009.67  5062.2 1026.78  5071.9 1007.85  5072.8 1009.44
  5072.9 1004.01  5073.5 1021.43  5077.6 1036.21  5096.9 1057.49  5126.9 1077.19
  5160.1 1106.90  5181.1 1116.63  5294.8 1155.21  5343.5 1166.45  5417.2 1171.04
#Mann=3,-1,0
  4598.3    0.15       0  4972.4    0.05       0  5027.6    0.15       0
Bank Sta=4972.4,5027.6
XS Rating Curve= 0
Exp/Cntr=0.3,0.1

Type RM Length L Ch R = 1,103000,500,500,500
BEGIN DESCRIPTION:
Chauga River 206.0
END DESCRIPTION:
XS GIS Cut Line= 3
      1334627.46      1073970.38      1334647.40      1073678.25
      1334684.70      1073229.30
#Sta/Elev= 30
  4707.2 1144.42  4734.3 1125.83  4736.2 1139.94  4742.3 1122.96  4756.9 1114.78
  4815.4 1101.41  4913.5 1054.23  4971.9 1001.69  4972.4  988.84  4972.9  987.84
  5027.6  988.84  5039.0  998.45  5052.2 1000.63  5054.9  999.23  5056.0  991.80
  5070.5 1018.22  5070.7  997.66  5073.5 1015.80  5078.7 1023.02  5104.2 1042.42
  5111.7 1057.18  5122.9 1067.42  5149.9 1082.75  5211.4 1093.50  5289.4 1085.38
  5355.9 1118.63  5378.2 1141.03  5406.6 1141.30  5422.6 1153.64  5450.5 1161.82
#Mann=3,-1,0
  4707.2    0.15       0  4972.4    0.05       0  5027.6    0.15       0
Bank Sta=4972.4,5027.6
XS Rating Curve= 0
Exp/Cntr=0.3,0.1

Type RM Length L Ch R = 1,102500,570,570,570
BEGIN DESCRIPTION:
Chauga River 205.0
END DESCRIPTION:
XS GIS Cut Line= 3
      1334696.75      1073997.45      1335094.26      1073808.12
      1335422.72      1073702.24
#Sta/Elev= 30
  4559.7 1158.52  4602.4 1142.66  4629.6 1128.61  4658.6 1109.17  4685.1 1096.43
  4721.6 1087.95  4786.6 1079.66  4842.3 1056.81  4850.8 1056.14  4857.1 1048.53
  4897.9 1031.42  4914.4 1018.98  4935.1  996.33  4961.3  980.89  4972.4  978.61
  4972.9  977.61  5027.6  978.61  5034.3  984.19  5052.0  988.80  5052.4  991.99
  5073.2 1031.45  5074.1 1035.84  5082.4 1043.17  5106.0 1079.66  5140.1 1100.40
  5155.8 1105.39  5191.9 1127.80  5271.7 1158.88  5311.5 1168.60  5345.1 1169.67
#Mann=3,-1,0
  4559.7    0.15       0  4972.4    0.05       0  5027.6    0.15       0
Bank Sta=4972.4,5027.6
XS Rating Curve= 0
Exp/Cntr=0.3,0.1

Type RM Length L Ch R = 1,101930,519,519,519
BEGIN DESCRIPTION:
Chauga River 204.0
END DESCRIPTION:
XS GIS Cut Line= 3
      1334913.67      1074836.71      1335280.15      1074337.49
      1335455.87      1074158.95
#Sta/Elev= 30
  4380.7 1245.67  4394.6 1236.83  4414.9 1238.61  4450.1 1222.25  4487.9 1217.04
  4499.1 1208.01  4560.2 1188.90  4632.0 1148.18  4662.6 1141.06  4671.9 1133.80
  4682.5 1137.29  4687.1 1129.71  4847.9 1037.93  4865.7 1023.40  4912.3  998.41
  4923.4  987.02  4937.8  988.76  4962.6  971.71  4972.4  971.49  4972.9  970.49
  5027.6  971.49  5043.1  971.49  5072.6 1016.34  5081.0 1002.93  5081.7  975.57
  5084.2 1005.28  5100.5 1024.15  5115.2 1051.70  5189.9 1087.37  5250.5 1096.66
#Mann=3,-1,0
  4380.7    0.15       0  4972.4    0.05       0  5027.6    0.15       0
Bank Sta=4972.4,5027.6
XS Rating Curve= 0
Exp/Cntr=0.3,0.1

Type RM Length L Ch R = 1,101411,411,411,411
BEGIN DESCRIPTION:
Chauga River 203.0
END DESCRIPTION:
XS GIS Cut Line= 3
      1336136.75      1074731.32      1335728.09      1074354.47
      1335495.03      1074068.51
#Sta/Elev= 30
  4444.1 1174.41  4476.1 1176.50  4575.2 1164.21  4590.0 1165.95  4728.4 1139.21
  4775.3 1139.90  4805.7 1124.67  4835.6 1119.60  4880.6 1093.51  4900.3 1077.72
  4928.7 1038.38  4941.5  967.06  4946.2  995.81  4952.7  973.35  4960.3  977.20
  4964.5  963.58  4972.2  962.50  4972.7  961.50  5027.8  962.50  5036.3  970.11
  5067.1  976.32  5067.9  965.02  5092.8  978.79  5129.5  984.04  5216.1 1017.56
  5282.1 1072.73  5309.1 1084.87  5320.2 1083.21  5337.6 1104.57  5368.9 1114.68
#Mann=3,-1,0
  4444.1    0.15       0  4972.2    0.05       0  5027.8    0.15       0
Bank Sta=4972.2,5027.8
XS Rating Curve= 0
Exp/Cntr=0.3,0.1

Type RM Length L Ch R = 1,101000,500,500,500
BEGIN DESCRIPTION:
Chauga River 202.0
END DESCRIPTION:
XS GIS Cut Line= 3
      1336377.74      1074260.75      1335925.77      1073999.98
      1335576.39      1073811.88
#Sta/Elev= 30
  4478.2 1117.56  4541.7 1095.34  4638.6 1034.67  4707.9 1004.31  4717.6  983.51
  4723.7 1012.21  4780.5 1017.07  4809.0 1009.02  4838.2 1015.40  4880.6 1004.79
  4905.8 1005.03  4925.1  971.77  4925.3  963.41  4926.6  987.01  4950.5  964.25
  4972.2  956.32  4972.7  955.32  5027.8  956.32  5040.8  968.06  5072.9  958.11
  5080.4  977.19  5096.2  975.21  5099.1  956.79  5103.9  986.17  5109.0  998.27
  5136.7 1016.59  5173.5 1062.24  5216.7 1072.89  5308.3 1135.49  5396.8 1168.32
#Mann=3,-1,0
  4478.2    0.15       0  4972.2    0.05       0  5027.8    0.15       0
Bank Sta=4972.2,5027.8
XS Rating Curve= 0
Exp/Cntr=0.3,0.1

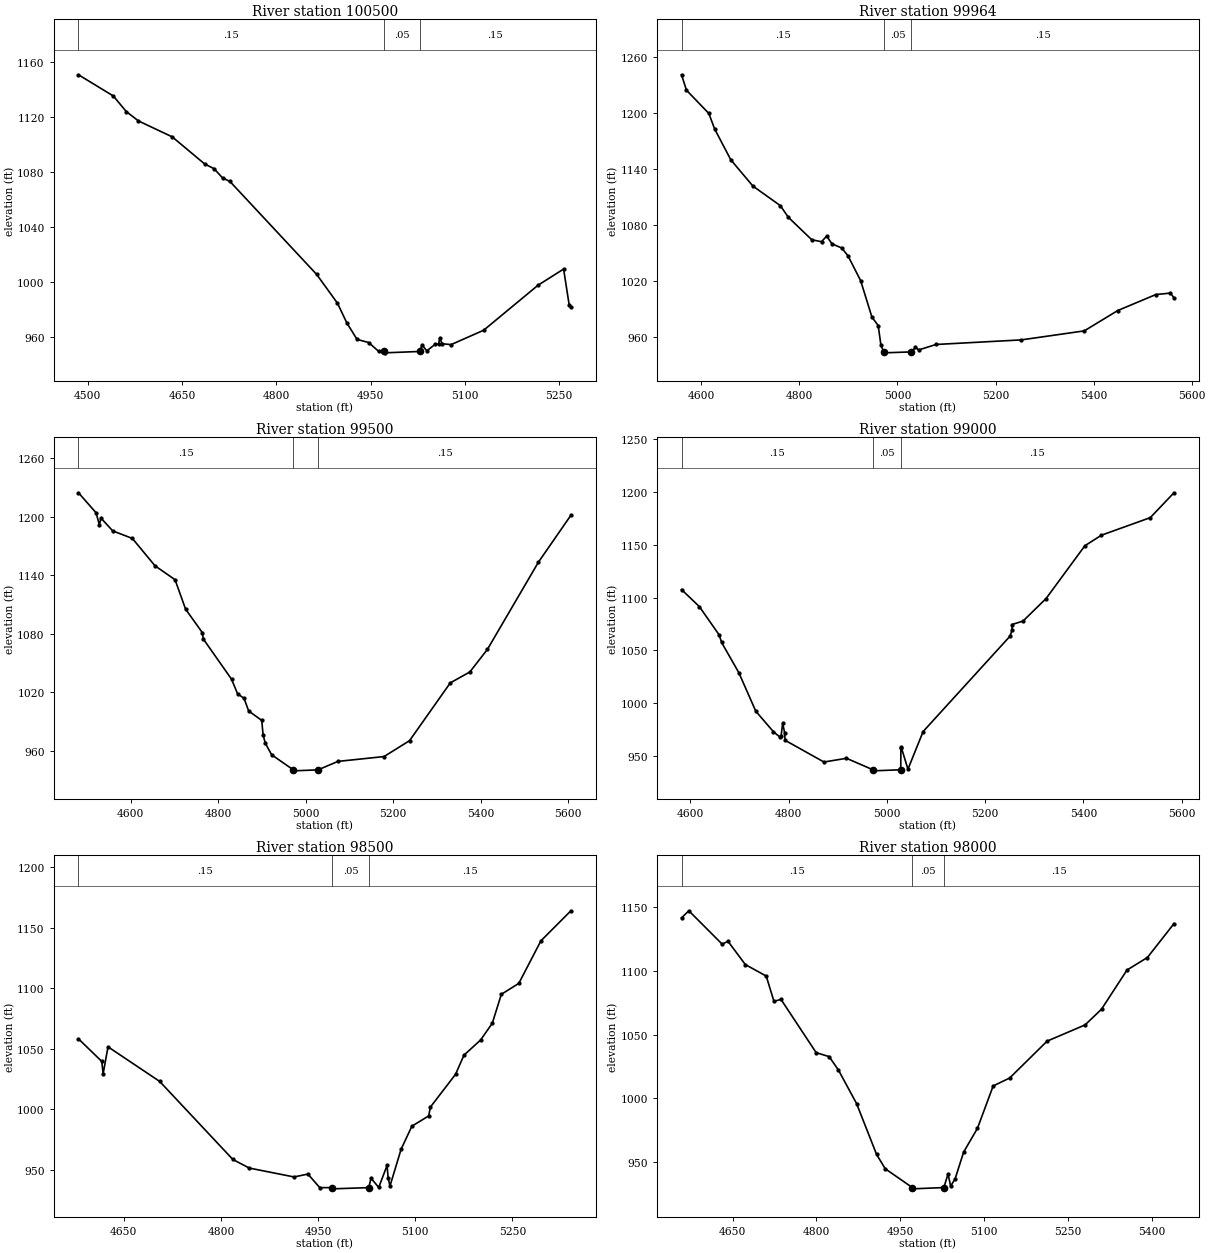
Type RM Length L Ch R = 1,100500,536,536,536
BEGIN DESCRIPTION:
Chauga River 201.0
END DESCRIPTION:
XS GIS Cut Line= 3
      1336630.76      1074209.52      1336356.80      1073774.15
      1336224.08      1073540.75
#Sta/Elev= 30
  4485.6 1150.74  4541.0 1135.33  4561.6 1124.02  4580.9 1117.22  4634.6 1105.64
  4686.1 1085.98  4701.3 1082.47  4714.6 1075.80  4726.4 1073.23  4864.2 1005.72
  4897.4  984.74  4912.2  970.48  4928.5  958.46  4947.0  956.19  4963.0  949.70
  4971.8  949.70  4972.3  948.70  5028.2  949.70  5031.7  954.51  5039.4  950.12
  5053.1  955.08  5058.2  955.00  5059.7  959.16  5064.2  955.29  5078.0  954.68
  5129.8  965.12  5216.2  997.82  5256.9 1009.57  5265.8  983.34  5268.5  982.13
#Mann=3,-1,0
  4485.6    0.15       0  4971.8    0.05       0  5028.2    0.15       0
Bank Sta=4971.8,5028.2
XS Rating Curve= 0
Exp/Cntr=0.3,0.1

Type RM Length L Ch R = 1,99964,464,464,464
BEGIN DESCRIPTION:
Chauga River 200.0
END DESCRIPTION:
XS GIS Cut Line= 3
      1337188.09      1073623.31      1336777.04      1073465.23
      1336215.07      1073511.84
#Sta/Elev= 30
  4559.6 1240.46  4569.7 1223.94  4615.3 1199.07  4627.2 1182.39  4660.1 1149.46
  4705.1 1121.39  4761.1 1100.41  4777.5 1087.90  4825.3 1063.84  4845.2 1061.81
  4855.6 1067.83  4866.5 1059.46  4886.0 1055.17  4898.9 1046.90  4924.9 1020.15
  4947.9  981.09  4960.7  972.07  4966.2  951.37  4971.8  943.84  4972.3  942.84
  5028.2  943.84  5036.7  948.64  5043.6  946.01  5078.7  951.79  5252.4  956.69
  5381.0  966.34  5449.3  988.12  5526.9 1005.22  5556.8 1006.79  5563.9 1001.71
#Mann=3,-1,0
  4559.6    0.15       0  4971.8    0.05       0  5028.2    0.15       0
Bank Sta=4971.8,5028.2
XS Rating Curve= 0
Exp/Cntr=0.3,0.1

Type RM Length L Ch R = 1,99500,500,500,500
BEGIN DESCRIPTION:
Chauga River 199.0
END DESCRIPTION:
XS GIS Cut Line= 3
      1337371.82      1073328.07      1336939.28      1073039.80
      1336443.98      1072689.42
#Sta/Elev= 30
  4480.2 1224.31  4520.4 1203.87  4528.2 1191.28  4531.4 1198.50  4558.5 1185.31
  4603.5 1177.54  4655.2 1149.58  4701.1 1135.30  4725.2 1105.17  4763.5 1081.14
  4765.8 1074.58  4830.3 1033.45  4844.1 1018.56  4859.0 1013.74  4869.5 1000.89
  4899.4  991.25  4902.6  976.20  4907.6  967.84  4922.1  956.02  4971.8  940.58
  4972.3  939.58  5028.2  940.58  5073.7  949.24  5179.2  954.20  5237.5  970.45
  5330.8 1029.66  5375.5 1040.82  5415.7 1063.97  5532.3 1153.19  5606.7 1201.29
#Mann=3,-1,0
  4480.2    0.15       0  4971.8    0.05       0  5028.2    0.15       0
Bank Sta=4971.8,5028.2
XS Rating Curve= 0
Exp/Cntr=0.3,0.1

Type RM Length L Ch R = 1,99000,500,500,500
BEGIN DESCRIPTION:
Chauga River 198.0
END DESCRIPTION:
XS GIS Cut Line= 3
      1337435.12      1072830.43      1337103.35      1072576.32
      1336627.72      1072236.93
#Sta/Elev= 30
  4582.1 1107.61  4618.4 1091.48  4658.8 1064.55  4663.7 1057.43  4698.7 1028.84
  4733.2  992.30  4768.9  972.93  4782.9  967.50  4784.8  969.01  4787.9  980.76
  4792.0  971.82  4792.8  964.69  4872.0  944.07  4917.8  947.61  4971.8  936.71
  4972.3  935.71  5028.2  936.71  5028.6  957.10  5029.4  957.92  5042.9  937.25
  5073.8  972.97  5250.7 1063.44  5254.7 1068.94  5254.8 1074.48  5277.1 1077.74
  5324.0 1099.11  5403.0 1149.17  5436.7 1159.18  5536.1 1175.83  5584.3 1199.41
#Mann=3,-1,0
  4582.1    0.15       0  4971.8    0.05       0  5028.2    0.15       0
Bank Sta=4971.8,5028.2
XS Rating Curve= 0
Exp/Cntr=0.3,0.1

Type RM Length L Ch R = 1,98500,500,500,500
BEGIN DESCRIPTION:
Chauga River 197.0
END DESCRIPTION:
XS GIS Cut Line= 3
      1337540.53      1072682.77      1337479.99      1072267.15
      1337417.03      1071932.73
#Sta/Elev= 30
  4580.0 1058.32  4615.9 1039.75  4618.1 1029.60  4625.6 1051.75  4705.4 1023.16
  4818.4  958.67  4843.8  951.58  4912.8  944.25  4934.2  946.63  4952.6  935.43
  4971.8  935.43  4972.3  934.43  5028.2  935.43  5031.7  943.20  5043.6  935.60
  5056.4  953.72  5058.2  943.39  5060.9  936.71  5078.2  967.24  5094.8  986.21
  5120.7  994.66  5123.3 1001.93  5162.2 1029.06  5175.2 1044.88  5200.8 1057.34
  5218.9 1071.22  5232.9 1095.17  5259.8 1104.13  5294.0 1139.32  5340.3 1164.15
#Mann=3,-1,0
  4580.0    0.15       0  4971.8    0.05       0  5028.2    0.15       0
Bank Sta=4971.8,5028.2
XS Rating Curve= 0
Exp/Cntr=0.3,0.1

Type RM Length L Ch R = 1,98000,500,500,500
BEGIN DESCRIPTION:
Chauga River 196.0
END DESCRIPTION:
XS GIS Cut Line= 3
      1338206.30      1072288.78      1337876.49      1071995.27
      1337459.24      1071854.99
#Sta/Elev= 30
  4558.5 1141.24  4571.6 1146.81  4631.3 1120.69  4641.7 1122.96  4672.7 1104.75
  4710.2 1095.72  4724.0 1075.93  4736.6 1077.48  4799.6 1035.79  4822.8 1032.72
  4839.5 1022.15  4871.9  995.99  4907.7  956.23  4923.2  944.97  4971.8  930.25
  4972.3  929.25  5028.2  930.25  5035.7  940.90  5040.4  931.38  5048.4  937.13
  5063.7  958.09  5088.4  976.63  5116.5 1009.76  5146.0 1015.96  5213.1 1044.82
  5281.1 1057.52  5310.5 1069.82  5356.1 1100.44  5392.6 1110.24  5440.2 1136.72
#Mann=3,-1,0
  4558.5    0.15       0  4971.8    0.05       0  5028.2    0.15       0
Bank Sta=4971.8,5028.2
XS Rating Curve= 0
Exp/Cntr=0.3,0.1

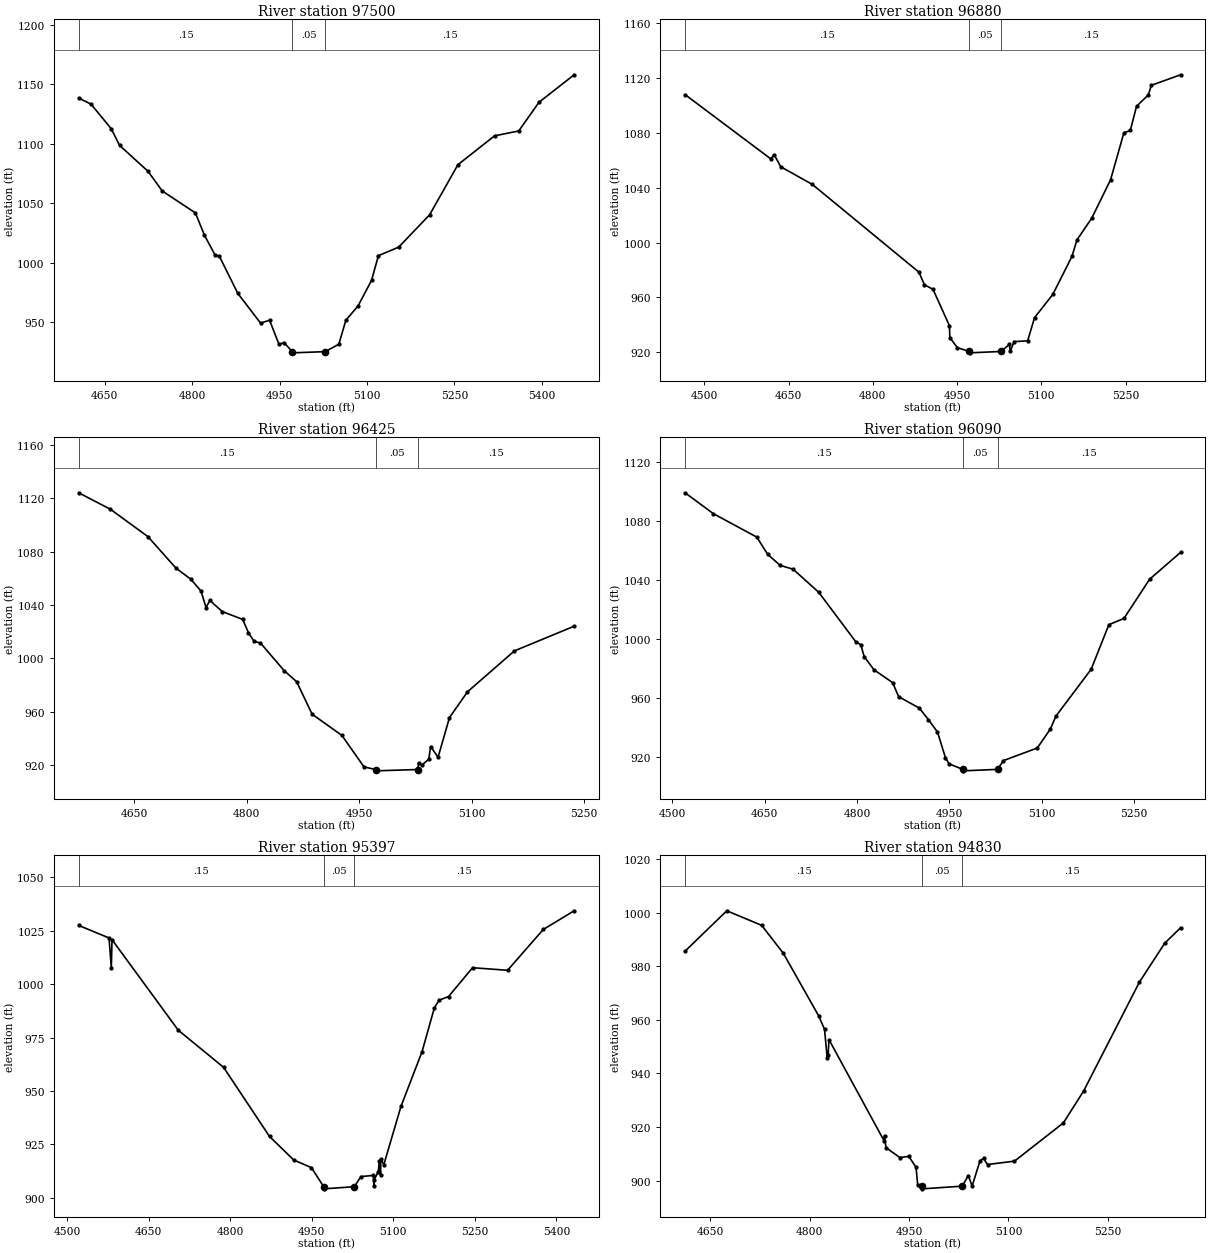
Type RM Length L Ch R = 1,97500,620,620,620
BEGIN DESCRIPTION:
Chauga River 195.0
END DESCRIPTION:
XS GIS Cut Line= 3
      1338353.92      1071943.57      1338160.00      1071599.56
      1337926.12      1071208.46
#Sta/Elev= 30
  4605.1 1138.32  4626.4 1133.11  4661.0 1112.53  4675.3 1098.53  4724.2 1076.71
  4748.7 1060.15  4805.5 1041.75  4821.1 1022.99  4839.1 1006.52  4846.7 1005.27
  4878.3  974.15  4917.5  949.06  4932.8  951.62  4949.0  931.30  4957.6  932.78
  4971.8  925.15  4972.3  924.15  5028.2  925.15  5051.7  931.34  5063.8  951.57
  5084.8  963.63  5107.9  985.08  5119.7 1005.84  5154.4 1012.95  5207.5 1040.11
  5256.2 1082.27  5319.0 1106.50  5360.6 1110.62  5395.3 1134.70  5455.7 1157.82
#Mann=3,-1,0
  4605.1    0.15       0  4971.8    0.05       0  5028.2    0.15       0
Bank Sta=4971.8,5028.2
XS Rating Curve= 0
Exp/Cntr=0.3,0.1

Type RM Length L Ch R = 1,96880,455,455,455
BEGIN DESCRIPTION:
Chauga River 194.0
END DESCRIPTION:
XS GIS Cut Line= 3
      1338522.60      1071762.82      1338651.85      1071244.59
      1338748.53      1070910.29
#Sta/Elev= 30
  4465.9 1108.00  4618.4 1061.09  4624.4 1064.22  4636.1 1055.35  4692.6 1042.39
  4882.2  978.37  4892.0  969.16  4907.2  965.87  4936.4  939.32  4937.2  930.57
  4950.7  923.27  4971.8  920.51  4972.3  919.51  5028.2  920.51  5043.3  925.73
  5044.5  920.51  5051.6  927.72  5075.7  928.26  5087.9  945.18  5120.5  962.19
  5154.5  989.85  5163.5 1001.97  5189.9 1017.92  5223.3 1045.87  5246.9 1080.04
  5258.4 1081.85  5269.5 1099.49  5290.5 1107.81  5295.9 1114.81  5348.0 1122.48
#Mann=3,-1,0
  4465.9    0.15       0  4971.8    0.05       0  5028.2    0.15       0
Bank Sta=4971.8,5028.2
XS Rating Curve= 0
Exp/Cntr=0.3,0.1

Type RM Length L Ch R = 1,96425,335,335,335
BEGIN DESCRIPTION:
Chauga River 193.0
END DESCRIPTION:
XS GIS Cut Line= 3
      1338561.77      1071937.52      1338847.86      1071624.18
      1339010.65      1071452.49
#Sta/Elev= 30
  4575.7 1123.98  4618.0 1111.67  4668.1 1091.16  4705.4 1067.61  4725.4 1059.21
  4739.0 1050.32  4745.6 1038.01  4750.7 1043.37  4767.2 1035.05  4794.6 1029.12
  4802.2 1019.13  4809.7 1012.70  4818.2 1011.49  4849.7  990.84  4866.5  982.48
  4887.1  958.15  4926.8  942.30  4956.3  918.67  4971.8  916.75  4972.3  915.75
  5028.2  916.75  5029.0  921.77  5033.3  919.94  5042.7  924.49  5045.1  933.95
  5055.1  925.95  5070.3  955.63  5094.3  974.93  5156.9 1005.58  5236.6 1024.07
#Mann=3,-1,0
  4575.7    0.15       0  4971.8    0.05       0  5028.2    0.15       0
Bank Sta=4971.8,5028.2
XS Rating Curve= 0
Exp/Cntr=0.3,0.1

Type RM Length L Ch R = 1,96090,693,693,693
BEGIN DESCRIPTION:
Chauga River 192.0
END DESCRIPTION:
XS GIS Cut Line= 3
      1339272.71      1072136.31      1339159.41      1071670.59
      1339055.81      1071362.12
#Sta/Elev= 30
  4520.7 1099.42  4566.5 1085.27  4637.1 1069.33  4654.9 1057.61  4675.0 1050.15
  4696.1 1047.54  4737.8 1031.83  4797.9  998.28  4805.9  996.37  4811.5  988.26
  4827.3  979.33  4857.8  970.51  4867.5  961.01  4900.9  953.32  4915.7  945.49
  4930.5  937.07  4943.5  919.58  4949.4  915.40  4971.8  911.68  4972.3  910.68
  5028.2  911.68  5037.5  917.60  5092.6  926.20  5113.9  939.07  5122.9  947.83
  5180.2  979.68  5208.8 1009.86  5233.4 1014.14  5275.0 1040.73  5325.4 1058.98
#Mann=3,-1,0
  4520.7    0.15       0  4971.8    0.05       0  5028.2    0.15       0
Bank Sta=4971.8,5028.2
XS Rating Curve= 0
Exp/Cntr=0.3,0.1

Type RM Length L Ch R = 1,95397,567,567,567
BEGIN DESCRIPTION:
Chauga River 191.0
END DESCRIPTION:
XS GIS Cut Line= 3
      1339971.63      1071621.23      1339691.81      1071232.58
      1339384.23      1070928.38
#Sta/Elev= 30
  4521.1 1027.48  4577.0 1021.59  4581.2 1007.65  4582.5 1020.80  4704.3  978.46
  4787.8  961.04  4872.2  928.72  4916.8  917.70  4949.4  914.13  4971.8  905.21
  4972.3  904.21  5028.2  905.21  5040.3  909.95  5063.0  910.48  5064.5  905.36
  5064.6  908.33  5072.3  912.29  5074.2  917.35  5076.6  910.53  5076.9  918.31
  5082.4  915.49  5114.2  942.91  5152.8  968.39  5175.3  988.77  5184.0  992.45
  5201.6  994.20  5245.7 1007.67  5310.1 1006.47  5375.8 1025.57  5432.6 1034.31
#Mann=3,-1,0
  4521.1    0.15       0  4971.8    0.05       0  5028.2    0.15       0
Bank Sta=4971.8,5028.2
XS Rating Curve= 0
Exp/Cntr=0.3,0.1

Type RM Length L Ch R = 1,94830,452,452,452
BEGIN DESCRIPTION:
Chauga River 190.0
END DESCRIPTION:
XS GIS Cut Line= 3
      1340471.68      1070945.81      1340098.30      1070841.40
      1339754.72      1070734.93
#Sta/Elev= 30
  4612.3  985.64  4675.2 1000.69  4727.8  995.25  4760.5  984.81  4813.8  961.46
  4822.6  956.45  4826.7  945.62  4828.0  946.79  4829.3  952.61  4912.3  914.92
  4913.1  916.81  4915.2  912.32  4936.2  908.62  4949.6  909.06  4960.6  905.00
  4963.2  898.21  4969.7  897.94  4970.2  896.94  5030.3  897.94  5039.5  901.91
  5045.2  897.94  5057.1  907.44  5062.4  908.28  5068.4  906.02  5109.1  907.27
  5182.9  921.55  5213.6  933.55  5297.5  974.06  5335.6  988.56  5359.7  994.38
#Mann=3,-1,0
  4612.3    0.15       0  4969.7    0.05       0  5030.3    0.15       0
Bank Sta=4969.7,5030.3
XS Rating Curve= 0
Exp/Cntr=0.3,0.1

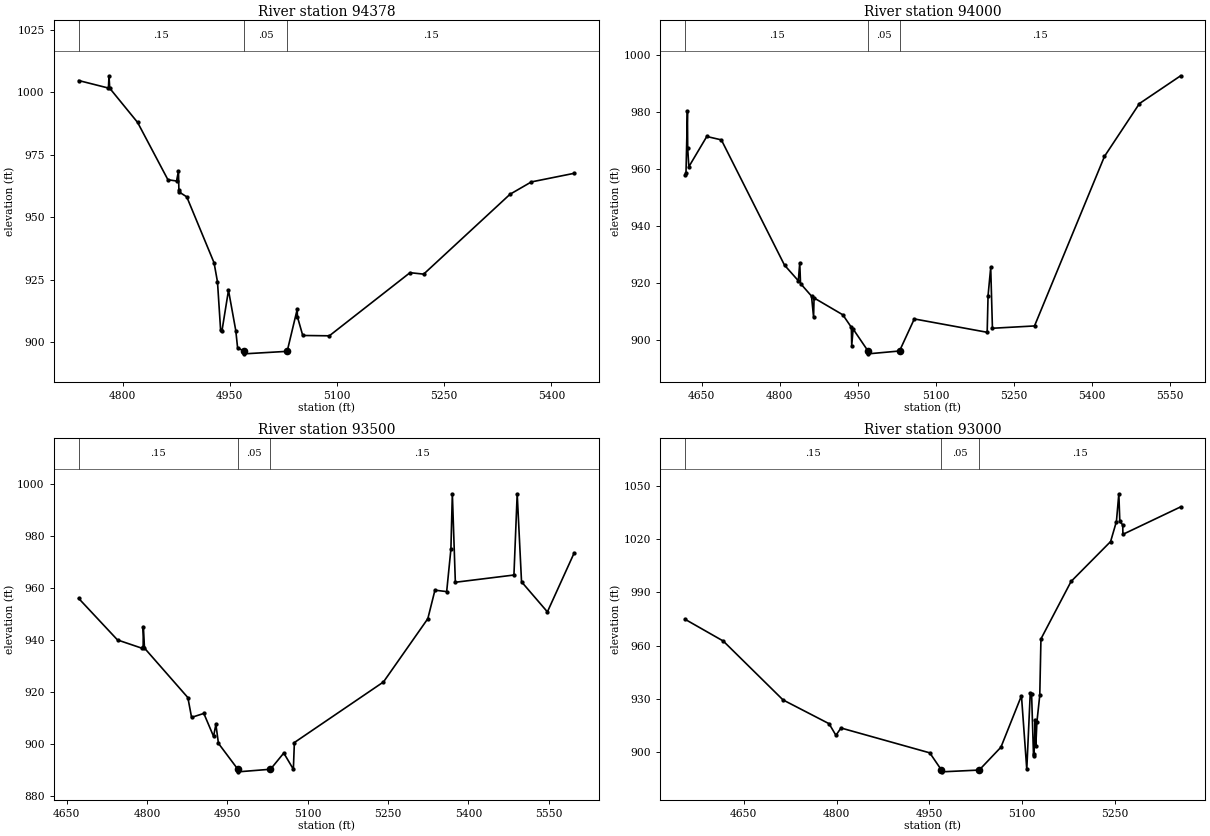
Type RM Length L Ch R = 1,94378,378,378,378
BEGIN DESCRIPTION:
Chauga River 189.0
END DESCRIPTION:
XS GIS Cut Line= 3
      1340426.47      1070367.41      1340168.26      1070408.79
      1339769.74      1070575.29
#Sta/Elev= 30
  4738.5 1004.77  4780.2 1001.75  4781.0 1006.67  4782.0 1001.68  4821.0  987.99
  4863.4  965.04  4875.5  964.51  4878.2  968.47  4878.8  960.75  4879.6  960.03
  4889.8  958.17  4928.0  931.76  4932.8  924.10  4937.2  904.65  4939.1  904.56
  4948.2  920.74  4958.4  904.58  4960.9  897.78  4969.7  896.28  4970.2  895.28
  5030.3  896.28  5044.3  913.06  5044.7  910.07  5052.1  902.64  5089.3  902.50
  5202.2  927.79  5221.3  927.21  5342.2  959.22  5372.0  964.15  5431.9  967.60
#Mann=3,-1,0
  4738.5    0.15       0  4969.7    0.05       0  5030.3    0.15       0
Bank Sta=4969.7,5030.3
XS Rating Curve= 0
Exp/Cntr=0.3,0.1

Type RM Length L Ch R = 1,94000,500,500,500
BEGIN DESCRIPTION:
Chauga River 188.0
END DESCRIPTION:
XS GIS Cut Line= 3
      1340518.68      1070059.53      1340137.62      1070034.21
      1339570.99      1069966.15
#Sta/Elev= 30
  4618.1  958.13  4619.8  958.68  4622.6  980.41  4623.1  967.39  4625.3  960.95
  4659.8  971.57  4687.8  970.38  4809.2  926.41  4835.8  920.93  4838.5  927.25
  4840.0  919.95  4861.1  915.55  4865.1  908.15  4866.0  914.90  4921.3  908.98
  4937.7  904.60  4938.4  898.20  4941.1  903.99  4969.7  896.28  4970.2  895.28
  5030.3  896.28  5058.7  907.53  5198.8  902.84  5200.5  915.73  5205.6  925.59
  5208.9  904.26  5289.8  905.07  5424.3  964.59  5491.5  983.13  5570.7  992.88
#Mann=3,-1,0
  4618.1    0.15       0  4969.7    0.05       0  5030.3    0.15       0
Bank Sta=4969.7,5030.3
XS Rating Curve= 0
Exp/Cntr=0.3,0.1

Type RM Length L Ch R = 1,93500,500,500,500
BEGIN DESCRIPTION:
Chauga River 187.0
END DESCRIPTION:
XS GIS Cut Line= 3
      1340663.28      1069696.83      1340351.21      1069596.50
      1339777.64      1069428.73
#Sta/Elev= 30
  4672.2  956.12  4744.8  940.10  4791.2  936.86  4792.7  937.28  4792.9  945.26
  4795.2  936.95  4876.2  917.89  4883.1  910.27  4906.0  911.79  4924.2  902.94
  4928.5  907.56  4933.3  900.26  4969.5  890.29  4970.0  889.29  5030.5  890.29
  5055.3  896.53  5073.2  890.29  5075.1  900.58  5241.5  923.92  5324.3  948.29
  5337.6  959.28  5359.5  958.72  5367.4  975.03  5370.1  996.41  5375.7  962.32
  5485.1  965.11  5491.2  996.41  5499.3  962.50  5547.6  950.91  5597.6  973.62
#Mann=3,-1,0
  4672.2    0.15       0  4969.5    0.05       0  5030.5    0.15       0
Bank Sta=4969.5,5030.5
XS Rating Curve= 0
Exp/Cntr=0.3,0.1

Type RM Length L Ch R = 1,93000,500,500,500
BEGIN DESCRIPTION:
Chauga River 186.0
END DESCRIPTION:
XS GIS Cut Line= 3
      1340720.51      1069648.61      1340623.04      1069214.52
      1340569.90      1068862.41
#Sta/Elev= 30
  4555.1  974.90  4616.8  962.67  4713.4  929.54  4787.8  916.16  4798.9  909.63
  4807.1  913.74  4950.6  899.75  4969.5  890.07  4970.0  889.07  5030.5  890.07
  5065.6  902.92  5098.8  931.90  5107.4  890.47  5113.0  933.34  5115.2  932.68
  5118.3  897.95  5119.2  899.32  5121.1  917.99  5122.0  903.62  5123.8  917.22
  5128.4  932.18  5130.3  963.87  5179.0  996.20  5242.9 1018.65  5252.3 1029.94
  5256.2 1045.54  5257.8 1029.97  5262.5 1028.03  5262.8 1022.71  5356.1 1038.17
#Mann=3,-1,0
  4555.1    0.15       0  4969.5    0.05       0  5030.5    0.15       0
Bank Sta=4969.5,5030.5
XS Rating Curve= 0
Exp/Cntr=0.3,0.1