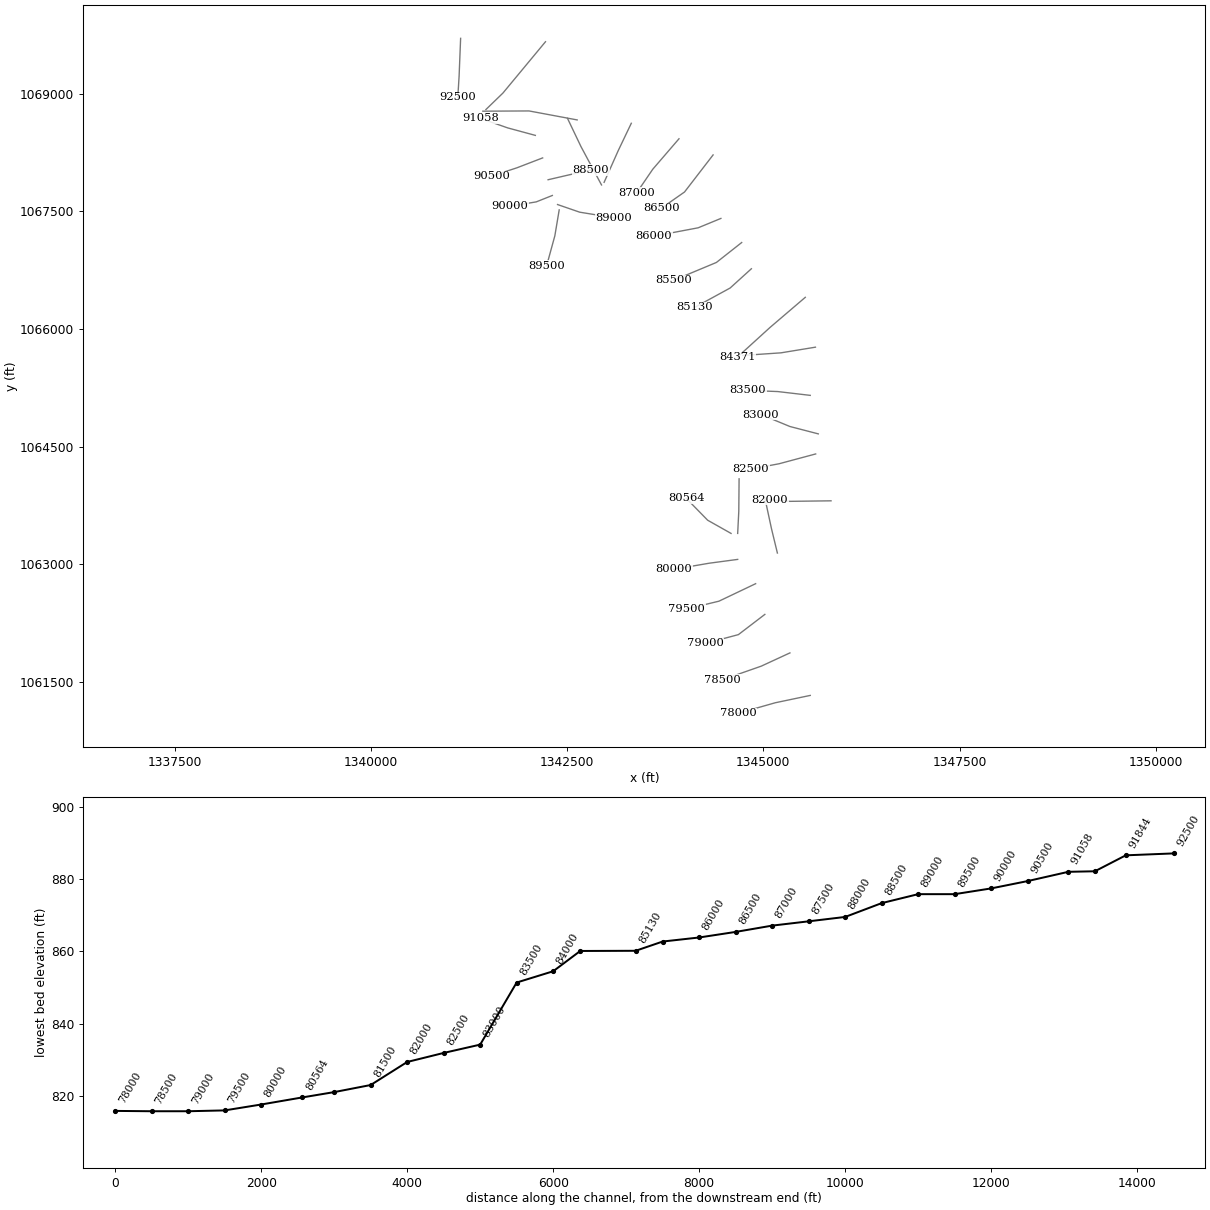
HEC-RAS study Chauga River.prj: Chauga River Limited Detail Study

--- Chauga River.g01 (geometry) --- (continued)

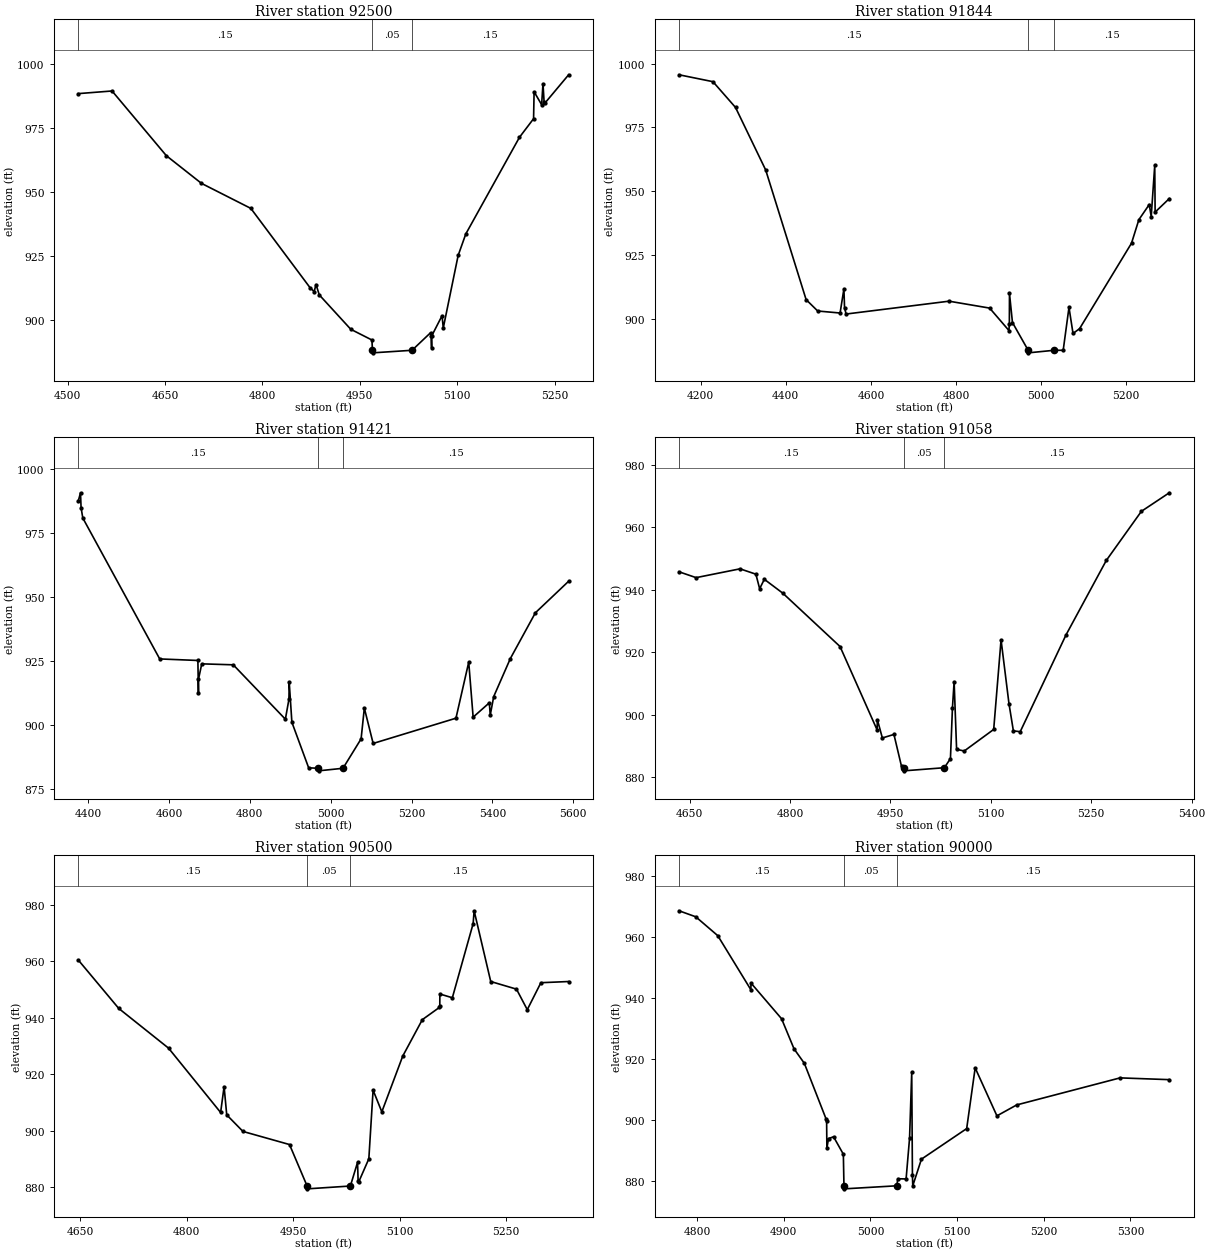
Type RM Length L Ch R = 1,92500,656,656,656
BEGIN DESCRIPTION:
Chauga River 185.0
END DESCRIPTION:
XS GIS Cut Line= 3
      1341142.26      1069705.82      1341122.85      1069222.71
      1341106.11      1068951.53
#Sta/Elev= 30
  4516.5  988.51  4568.4  989.54  4652.1  964.20  4706.1  953.39  4782.2  943.59
  4873.3  912.59  4879.7  911.04  4882.6  913.80  4887.6  909.74  4936.1  896.29
  4968.7  892.09  4969.5  888.07  4970.0  887.07  5030.5  888.07  5059.0  894.93
  5060.0  893.62  5060.6  889.04  5060.8  893.71  5076.7  901.59  5078.6  896.82
  5101.5  925.17  5113.3  933.60  5196.0  971.43  5217.7  978.69  5218.5  989.23
  5230.1  984.18  5232.2  992.40  5233.9  985.24  5235.9  985.02  5271.7  995.88
#Mann=3,-1,0
  4516.5    0.15       0  4969.5    0.05       0  5030.5    0.15       0
Bank Sta=4969.5,5030.5
XS Rating Curve= 0
Exp/Cntr=0.3,0.1

Type RM Length L Ch R = 1,91844,423,423,423
BEGIN DESCRIPTION:
Chauga River 184.0
END DESCRIPTION:
XS GIS Cut Line= 3
      1342223.76      1069662.50      1341680.90      1069007.39
      1341464.61      1068797.92
#Sta/Elev= 30
  4149.2  995.61  4228.9  992.90  4281.9  982.80  4352.8  958.26  4447.8  907.41
  4475.0  902.95  4527.6  902.16  4536.6  911.64  4538.1  904.20  4541.7  901.76
  4783.5  906.80  4879.0  904.09  4924.3  895.30  4925.3  897.86  4925.6  909.84
  4932.6  898.43  4969.5  887.54  4970.0  886.54  5030.5  887.54  5051.8  887.54
  5065.4  904.36  5074.9  894.14  5090.3  896.02  5212.3  929.54  5229.6  938.77
  5254.0  944.71  5258.6  939.99  5266.9  960.08  5267.8  941.74  5301.1  947.05
#Mann=3,-1,0
  4149.2    0.15       0  4969.5    0.05       0  5030.5    0.15       0
Bank Sta=4969.5,5030.5
XS Rating Curve= 0
Exp/Cntr=0.3,0.1

Type RM Length L Ch R = 1,91421,363,363,363
BEGIN DESCRIPTION:
Chauga River 183.0
END DESCRIPTION:
XS GIS Cut Line= 3
      1342627.43      1068665.35      1342014.04      1068779.94
      1341425.45      1068776.82
#Sta/Elev= 30
  4376.0  987.75  4381.3  990.84  4382.7  984.98  4387.0  980.96  4577.2  925.88
  4671.6  925.28  4673.0  912.46  4673.1  917.95  4681.2  923.96  4759.1  923.58
  4888.0  902.32  4896.8  910.11  4897.5  916.83  4904.1  901.12  4945.6  883.31
  4969.5  883.13  4970.0  882.13  5030.5  883.13  5075.3  894.63  5083.3  906.65
  5105.1  892.84  5309.9  902.71  5341.5  924.62  5352.4  903.12  5392.5  908.73
  5394.7  903.93  5403.3  911.17  5444.5  926.05  5506.4  943.93  5588.6  956.25
#Mann=3,-1,0
  4376.0    0.15       0  4969.5    0.05       0  5030.5    0.15       0
Bank Sta=4969.5,5030.5
XS Rating Curve= 0
Exp/Cntr=0.3,0.1

Type RM Length L Ch R = 1,91058,558,558,558
BEGIN DESCRIPTION:
Chauga River 182.0
END DESCRIPTION:
XS GIS Cut Line= 3
      1342094.25      1068468.33      1341741.17      1068563.94
      1341395.32      1068685.24
#Sta/Elev= 30
  4634.2  945.68  4659.7  943.81  4725.3  946.63  4749.0  944.92  4754.6  940.26
  4761.6  943.28  4789.3  938.82  4874.7  921.76  4930.0  895.11  4930.5  898.32
  4937.9  892.50  4955.2  893.63  4966.5  883.41  4969.5  882.98  4970.0  881.98
  5030.5  882.98  5039.6  885.89  5042.6  902.19  5045.1  910.51  5048.8  888.86
  5060.2  888.33  5104.2  895.23  5115.2  923.90  5127.0  903.52  5133.6  894.78
  5143.8  894.50  5212.2  925.47  5272.4  949.32  5324.8  965.03  5366.5  970.97
#Mann=3,-1,0
  4634.2    0.15       0  4969.5    0.05       0  5030.5    0.15       0
Bank Sta=4969.5,5030.5
XS Rating Curve= 0
Exp/Cntr=0.3,0.1

Type RM Length L Ch R = 1,90500,500,500,500
BEGIN DESCRIPTION:
Chauga River 181.0
END DESCRIPTION:
XS GIS Cut Line= 3
      1342187.61      1068180.95      1341858.25      1068054.23
      1341536.94      1067949.00
#Sta/Elev= 30
  4647.1  960.44  4704.0  943.33  4774.2  929.26  4847.6  906.47  4852.5  915.63
  4856.2  905.62  4879.1  899.75  4944.7  895.11  4969.5  880.42  4970.0  879.42
  5030.5  880.42  5040.6  888.82  5041.4  882.11  5042.2  881.85  5056.5  890.06
  5062.5  914.37  5074.8  906.69  5104.3  926.45  5131.9  939.35  5155.8  943.66
  5156.5  944.09  5156.6  948.44  5174.2  947.11  5203.5  973.37  5204.9  977.92
  5228.3  952.86  5264.6  950.16  5279.8  942.89  5299.0  952.44  5338.1  952.86
#Mann=3,-1,0
  4647.1    0.15       0  4969.5    0.05       0  5030.5    0.15       0
Bank Sta=4969.5,5030.5
XS Rating Curve= 0
Exp/Cntr=0.3,0.1

Type RM Length L Ch R = 1,90000,500,500,500
BEGIN DESCRIPTION:
Chauga River 180.0
END DESCRIPTION:
XS GIS Cut Line= 3
      1342311.14      1067701.98      1342106.03      1067620.25
      1341765.85      1067563.39
#Sta/Elev= 30
  4779.2  968.56  4798.5  966.59  4823.9  960.40  4862.1  942.67  4862.2  944.87
  4897.5  933.17  4911.9  923.29  4923.8  918.54  4948.8  900.36  4949.5  899.50
  4949.8  890.73  4951.7  893.88  4957.5  894.46  4968.8  888.74  4969.5  878.39
  4970.0  877.39  5030.5  878.39  5031.6  880.70  5041.2  880.63  5045.2  894.01
  5047.7  915.58  5048.5  881.97  5048.9  878.39  5058.9  887.12  5111.1  897.14
  5120.9  917.05  5146.0  901.32  5168.8  904.90  5288.1  913.77  5344.9  913.19
#Mann=3,-1,0
  4779.2    0.15       0  4969.5    0.05       0  5030.5    0.15       0
Bank Sta=4969.5,5030.5
XS Rating Curve= 0
Exp/Cntr=0.3,0.1

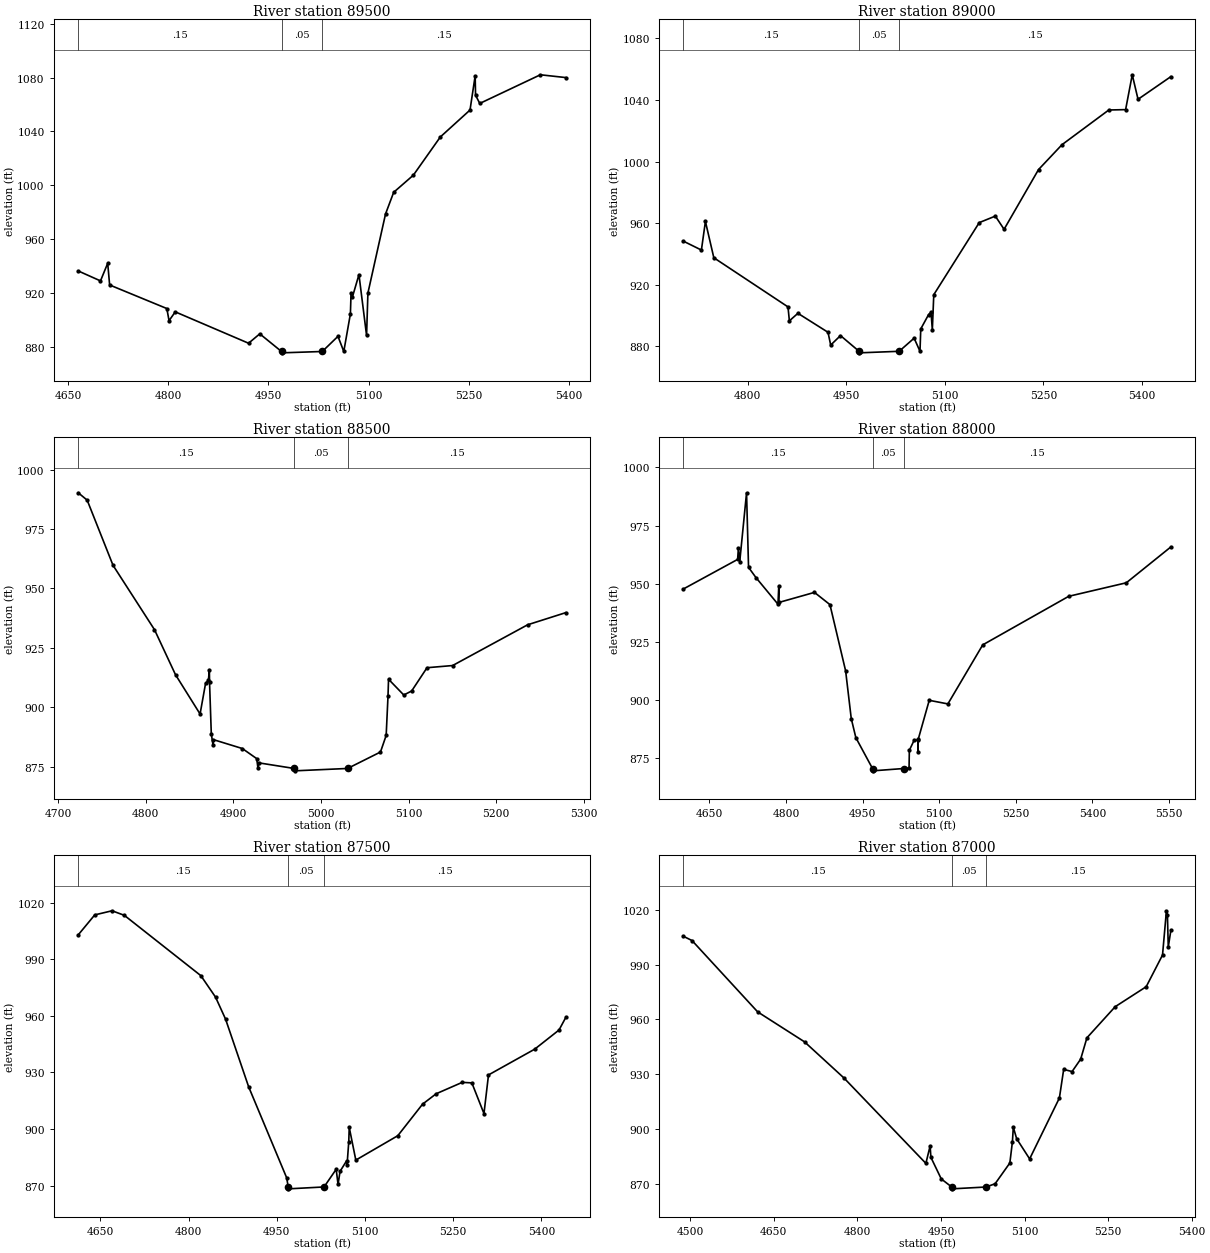
Type RM Length L Ch R = 1,89500,500,500,500
BEGIN DESCRIPTION:
Chauga River 179.0
END DESCRIPTION:
XS GIS Cut Line= 3
      1342398.47      1067518.19      1342343.11      1067188.10
      1342238.80      1066807.22
#Sta/Elev= 30
  4665.3  936.55  4698.6  929.17  4709.4  942.23  4712.3  926.14  4797.9  908.66
  4801.2  899.65  4810.5  906.20  4920.2  882.93  4937.0  889.89  4969.5  876.80
  4970.0  875.80  5030.5  876.80  5054.0  888.04  5062.7  876.80  5072.6  904.72
  5073.6  920.32  5075.6  917.19  5085.4  933.83  5096.8  888.68  5098.8  920.14
  5125.2  978.86  5137.4  994.91  5166.8 1007.59  5207.2 1035.95  5251.6 1055.91
  5259.3 1081.32  5259.9 1066.90  5266.2 1060.81  5356.9 1082.07  5394.9 1080.00
#Mann=3,-1,0
  4665.3    0.15       0  4969.5    0.05       0  5030.5    0.15       0
Bank Sta=4969.5,5030.5
XS Rating Curve= 0
Exp/Cntr=0.3,0.1

Type RM Length L Ch R = 1,89000,500,500,500
BEGIN DESCRIPTION:
Chauga River 178.0
END DESCRIPTION:
XS GIS Cut Line= 3
      1342377.40      1067586.28      1342659.06      1067488.96
      1343097.39      1067417.58
#Sta/Elev= 30
  4702.0  948.31  4729.5  942.52  4735.6  961.08  4748.4  937.53  4861.3  905.62
  4863.4  896.57  4876.4  901.46  4922.2  889.14  4926.3  880.84  4941.2  887.00
  4969.5  876.80  4970.0  875.80  5030.5  876.80  5053.3  885.32  5062.2  876.80
  5063.4  891.34  5075.3  900.62  5079.0  902.18  5081.0  890.76  5083.2  913.55
  5152.4  960.34  5176.9  964.57  5190.2  956.00  5242.6  994.75  5278.4 1010.94
  5349.6 1033.45  5375.2 1033.69  5385.3 1056.31  5394.1 1040.39  5444.1 1055.12
#Mann=3,-1,0
  4702.0    0.15       0  4969.5    0.05       0  5030.5    0.15       0
Bank Sta=4969.5,5030.5
XS Rating Curve= 0
Exp/Cntr=0.3,0.1

Type RM Length L Ch R = 1,88500,500,500,500
BEGIN DESCRIPTION:
Chauga River 177.0
END DESCRIPTION:
XS GIS Cut Line= 3
      1342256.87      1067902.59      1342526.48      1067965.28
      1342799.17      1068026.12
#Sta/Elev= 30
  4723.2  990.23  4733.4  987.13  4762.9  959.73  4810.2  932.67  4834.2  913.72
  4862.2  897.21  4868.5  910.15  4871.7  911.31  4872.8  915.89  4873.0  910.56
  4875.0  888.92  4876.9  884.31  4877.5  886.43  4910.4  882.70  4926.8  878.46
  4928.3  874.32  4929.3  876.67  4969.5  874.32  4970.0  873.32  5030.5  874.32
  5068.0  881.23  5074.5  888.20  5076.6  904.73  5077.2  911.83  5094.6  905.20
  5103.6  906.90  5121.1  916.68  5150.3  917.59  5235.9  934.73  5279.4  939.83
#Mann=3,-1,0
  4723.2    0.15       0  4969.5    0.05       0  5030.5    0.15       0
Bank Sta=4969.5,5030.5
XS Rating Curve= 0
Exp/Cntr=0.3,0.1

Type RM Length L Ch R = 1,88000,500,500,500
BEGIN DESCRIPTION:
Chauga River 176.0
END DESCRIPTION:
XS GIS Cut Line= 3
      1342503.92      1068685.82      1342676.56      1068324.22
      1342937.71      1067836.31
#Sta/Elev= 30
  4599.3  947.70  4705.5  960.42  4707.1  965.41  4709.7  959.52  4723.0  989.08
  4726.9  957.01  4741.4  952.61  4784.5  941.16  4786.1  949.13  4786.5  941.93
  4855.9  946.24  4886.2  940.98  4916.9  912.47  4927.9  891.98  4936.9  883.76
  4969.5  870.50  4970.0  869.50  5030.5  870.50  5041.0  870.65  5041.6  878.34
  5051.3  882.82  5058.2  882.59  5058.7  877.45  5058.9  883.02  5080.5  899.83
  5117.0  898.28  5185.2  923.67  5353.5  944.56  5466.2  950.37  5553.4  965.80
#Mann=3,-1,0
  4599.3    0.15       0  4969.5    0.05       0  5030.5    0.15       0
Bank Sta=4969.5,5030.5
XS Rating Curve= 0
Exp/Cntr=0.3,0.1

Type RM Length L Ch R = 1,87500,500,500,500
BEGIN DESCRIPTION:
Chauga River 175.0
END DESCRIPTION:
XS GIS Cut Line= 3
      1343317.27      1068622.56      1343150.30      1068272.88
      1342970.86      1067869.49
#Sta/Elev= 30
  4612.5 1002.88  4640.6 1013.46  4670.0 1015.64  4690.9 1013.23  4821.0  981.26
  4846.0  969.87  4863.0  958.24  4902.3  922.33  4967.0  874.08  4969.5  869.29
  4970.0  868.29  5030.5  869.29  5051.1  878.65  5054.3  870.65  5057.7  877.57
  5068.8  883.11  5069.6  880.97  5072.5  893.25  5073.3  900.87  5084.5  883.52
  5155.9  896.45  5198.0  913.17  5221.1  918.67  5265.4  924.71  5281.8  924.44
  5302.4  908.17  5310.1  928.65  5388.7  942.31  5430.0  952.45  5441.5  959.10
#Mann=3,-1,0
  4612.5    0.15       0  4969.5    0.05       0  5030.5    0.15       0
Bank Sta=4969.5,5030.5
XS Rating Curve= 0
Exp/Cntr=0.3,0.1

Type RM Length L Ch R = 1,87000,500,500,500
BEGIN DESCRIPTION:
Chauga River 174.0
END DESCRIPTION:
XS GIS Cut Line= 3
      1343924.98      1068424.98      1343590.82      1068036.53
      1343386.58      1067736.92
#Sta/Elev= 30
  4487.6 1005.54  4503.2 1003.19  4621.0  964.09  4705.1  947.67  4775.9  927.85
  4922.9  881.06  4930.5  890.64  4931.9  884.35  4950.5  872.54  4969.3  868.10
  4969.8  867.10  5030.7  868.10  5047.1  869.88  5073.6  881.27  5078.2  892.91
  5079.8  900.87  5085.8  894.57  5109.1  883.51  5162.5  916.88  5170.2  932.56
  5185.3  931.39  5200.7  938.20  5211.9  949.87  5262.6  966.92  5318.3  977.89
  5347.6  995.25  5354.6 1019.51  5356.4 1017.26  5357.9  999.62  5362.6 1008.84
#Mann=3,-1,0
  4487.6    0.15       0  4969.3    0.05       0  5030.7    0.15       0
Bank Sta=4969.3,5030.7
XS Rating Curve= 0
Exp/Cntr=0.3,0.1

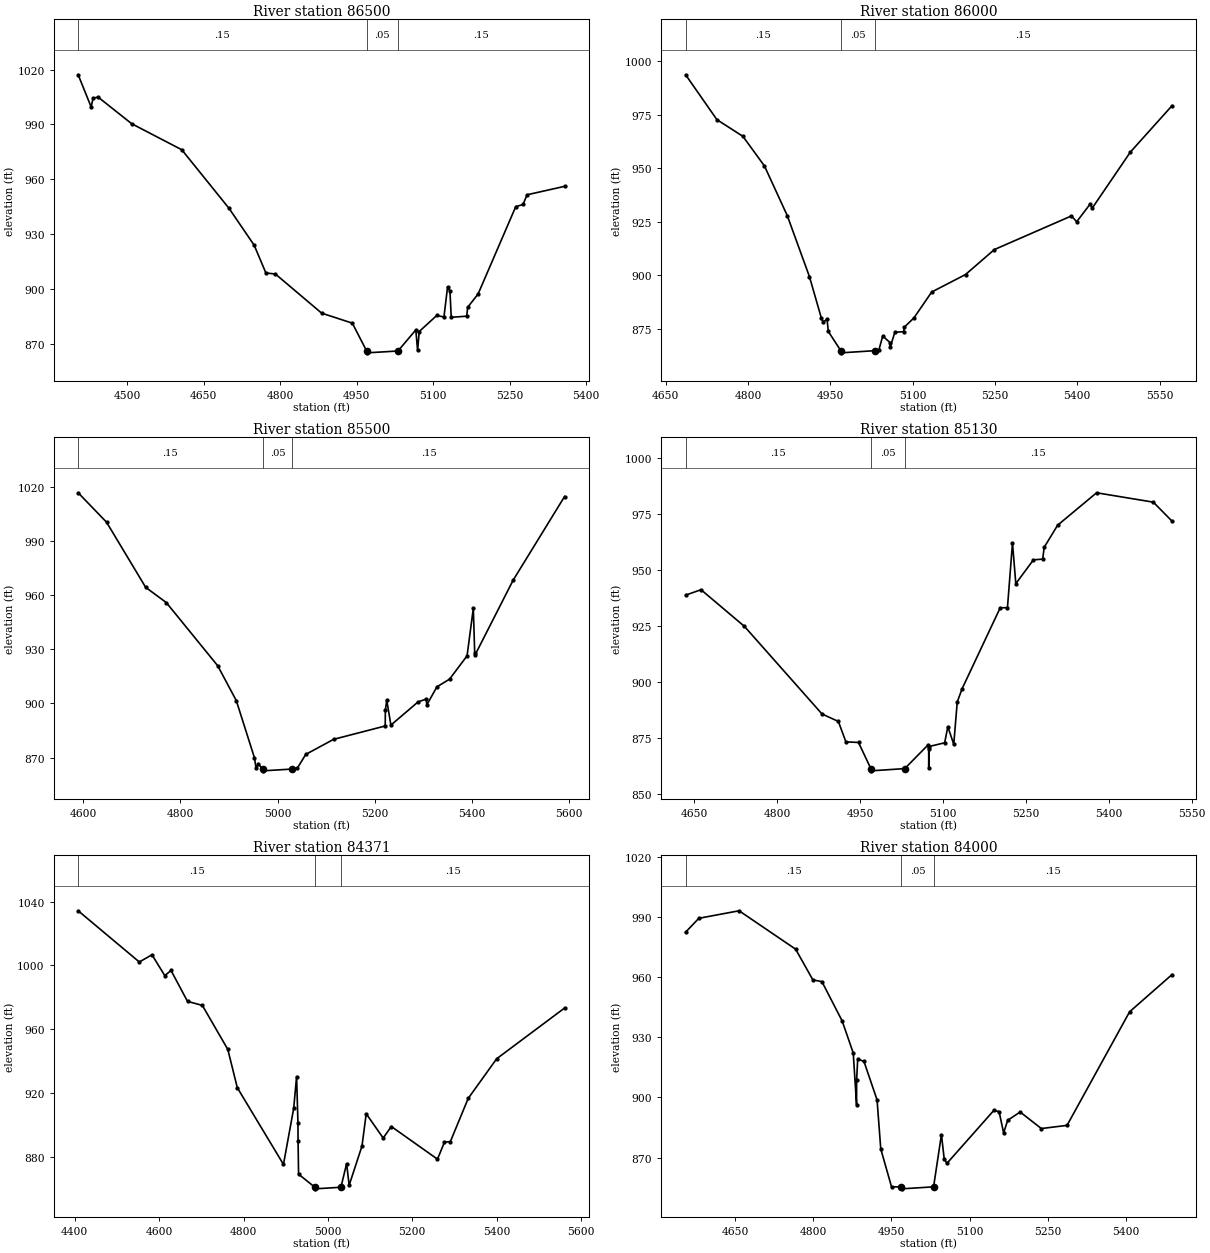
Type RM Length L Ch R = 1,86500,500,500,500
BEGIN DESCRIPTION:
Chauga River 173.0
END DESCRIPTION:
XS GIS Cut Line= 3
      1344359.57      1068218.87      1343995.62      1067746.27
      1343702.87      1067541.09
#Sta/Elev= 30
  4403.5 1017.12  4428.9  999.58  4432.8 1004.33  4442.5 1004.96  4508.5  990.40
  4606.7  976.20  4699.6  944.14  4748.7  924.09  4771.6  908.98  4790.4  908.36
  4881.0  887.03  4941.2  881.56  4969.3  866.36  4969.8  865.36  5030.7  866.36
  5065.7  877.87  5069.2  866.68  5072.4  877.00  5107.0  885.79  5120.9  884.89
  5128.0  901.35  5132.7  898.92  5135.2  884.75  5165.5  885.36  5167.4  890.23
  5187.8  897.44  5261.7  945.14  5276.1  946.33  5283.8  951.62  5357.5  956.23
#Mann=3,-1,0
  4403.5    0.15       0  4969.3    0.05       0  5030.7    0.15       0
Bank Sta=4969.3,5030.7
XS Rating Curve= 0
Exp/Cntr=0.3,0.1

Type RM Length L Ch R = 1,86000,500,500,500
BEGIN DESCRIPTION:
Chauga River 172.0
END DESCRIPTION:
XS GIS Cut Line= 3
      1344459.02      1067409.16      1344169.29      1067289.67
      1343606.47      1067183.21
#Sta/Elev= 30
  4686.6  993.56  4743.6  972.61  4791.0  964.83  4830.2  951.01  4871.7  927.89
  4912.1  899.43  4934.1  879.85  4937.3  878.20  4944.3  879.47  4946.5  873.81
  4969.3  864.82  4969.8  863.82  5030.7  864.82  5038.8  865.27  5045.7  871.68
  5059.1  868.56  5059.5  866.68  5067.8  873.39  5083.9  873.72  5085.0  875.80
  5102.6  880.14  5134.9  892.20  5196.5  900.35  5249.1  912.01  5389.4  927.69
  5399.1  924.99  5424.0  933.37  5427.0  931.20  5496.8  957.47  5572.8  979.14
#Mann=3,-1,0
  4686.6    0.15       0  4969.3    0.05       0  5030.7    0.15       0
Bank Sta=4969.3,5030.7
XS Rating Curve= 0
Exp/Cntr=0.3,0.1

Type RM Length L Ch R = 1,85500,370,370,370
BEGIN DESCRIPTION:
Chauga River 171.0
END DESCRIPTION:
XS GIS Cut Line= 3
      1344724.12      1067101.89      1344401.82      1066847.66
      1343856.49      1066619.87
#Sta/Elev= 30
  4589.5 1016.63  4647.9 1000.35  4728.5  964.27  4770.9  955.87  4876.8  920.87
  4915.1  901.56  4952.5  869.88  4955.8  864.13  4960.3  866.56  4969.3  863.70
  4969.8  862.70  5030.7  863.70  5040.6  864.13  5058.1  871.80  5115.4  880.14
  5221.7  887.54  5222.0  896.22  5224.8  901.80  5233.4  888.03  5289.5  900.89
  5306.0  902.43  5307.4  899.25  5328.1  909.19  5354.2  913.46  5390.2  926.35
  5403.1  952.68  5405.9  928.18  5406.4  926.71  5484.9  968.15  5591.0 1014.57
#Mann=3,-1,0
  4589.5    0.15       0  4969.3    0.05       0  5030.7    0.15       0
Bank Sta=4969.3,5030.7
XS Rating Curve= 0
Exp/Cntr=0.3,0.1

Type RM Length L Ch R = 1,85130,759,759,759
BEGIN DESCRIPTION:
Chauga River 170.0
END DESCRIPTION:
XS GIS Cut Line= 3
      1344847.61      1066767.48      1344576.56      1066521.68
      1344125.04      1066275.02
#Sta/Elev= 30
  4634.1  938.69  4661.9  941.13  4740.5  924.73  4881.0  885.55  4910.5  882.23
  4924.2  873.09  4947.0  872.83  4969.3  861.14  4969.8  860.14  5030.7  861.14
  5073.2  871.81  5074.0  869.97  5074.1  861.49  5074.7  871.02  5102.9  872.67
  5108.7  879.87  5119.4  872.00  5125.7  890.93  5134.5  896.85  5203.4  933.00
  5216.6  933.12  5225.7  962.03  5231.7  943.83  5263.6  954.47  5280.4  954.81
  5283.1  960.10  5307.4  969.96  5377.9  984.46  5480.6  980.27  5514.5  971.77
#Mann=3,-1,0
  4634.1    0.15       0  4969.3    0.05       0  5030.7    0.15       0
Bank Sta=4969.3,5030.7
XS Rating Curve= 0
Exp/Cntr=0.3,0.1

Type RM Length L Ch R = 1,84371,371,371,371
BEGIN DESCRIPTION:
Chauga River 169.0
END DESCRIPTION:
XS GIS Cut Line= 3
      1345534.47      1066402.98      1345084.61      1066018.46
      1344669.88      1065640.82
#Sta/Elev= 30
  4408.2 1034.26  4553.1 1002.18  4583.1 1006.70  4613.5  993.63  4628.2  996.88
  4667.3  977.52  4702.5  974.98  4762.8  947.43  4785.3  923.44  4894.7  875.39
  4919.0  910.60  4925.8  930.44  4929.0  901.58  4929.3  890.18  4930.5  869.28
  4969.1  861.09  4969.6  860.09  5030.9  861.09  5044.3  875.87  5050.4  862.36
  5080.8  886.93  5090.8  907.12  5131.0  891.91  5150.3  899.13  5259.7  878.67
  5276.2  889.30  5290.2  889.67  5332.5  916.74  5399.9  941.56  5560.9  973.35
#Mann=3,-1,0
  4408.2    0.15       0  4969.1    0.05       0  5030.9    0.15       0
Bank Sta=4969.1,5030.9
XS Rating Curve= 0
Exp/Cntr=0.3,0.1

Type RM Length L Ch R = 1,84000,500,500,500
BEGIN DESCRIPTION:
Chauga River 168.0
END DESCRIPTION:
XS GIS Cut Line= 3
      1345663.96      1065767.34      1345224.25      1065695.12
      1344736.18      1065661.91
#Sta/Elev= 30
  4554.4  982.34  4579.8  989.24  4657.1  992.98  4765.8  973.85  4798.9  958.57
  4816.3  957.68  4855.2  938.12  4876.5  922.16  4882.9  896.39  4883.0  908.61
  4885.1  919.11  4897.1  917.96  4922.3  898.77  4929.4  874.37  4950.1  855.48
  4969.1  855.48  4969.6  854.48  5030.9  855.48  5046.0  881.47  5051.3  869.46
  5056.5  867.15  5146.6  893.51  5156.8  892.96  5165.5  882.33  5173.3  888.61
  5197.3  892.75  5238.0  884.51  5287.4  886.09  5407.6  942.66  5489.2  961.21
#Mann=3,-1,0
  4554.4    0.15       0  4969.1    0.05       0  5030.9    0.15       0
Bank Sta=4969.1,5030.9
XS Rating Curve= 0
Exp/Cntr=0.3,0.1

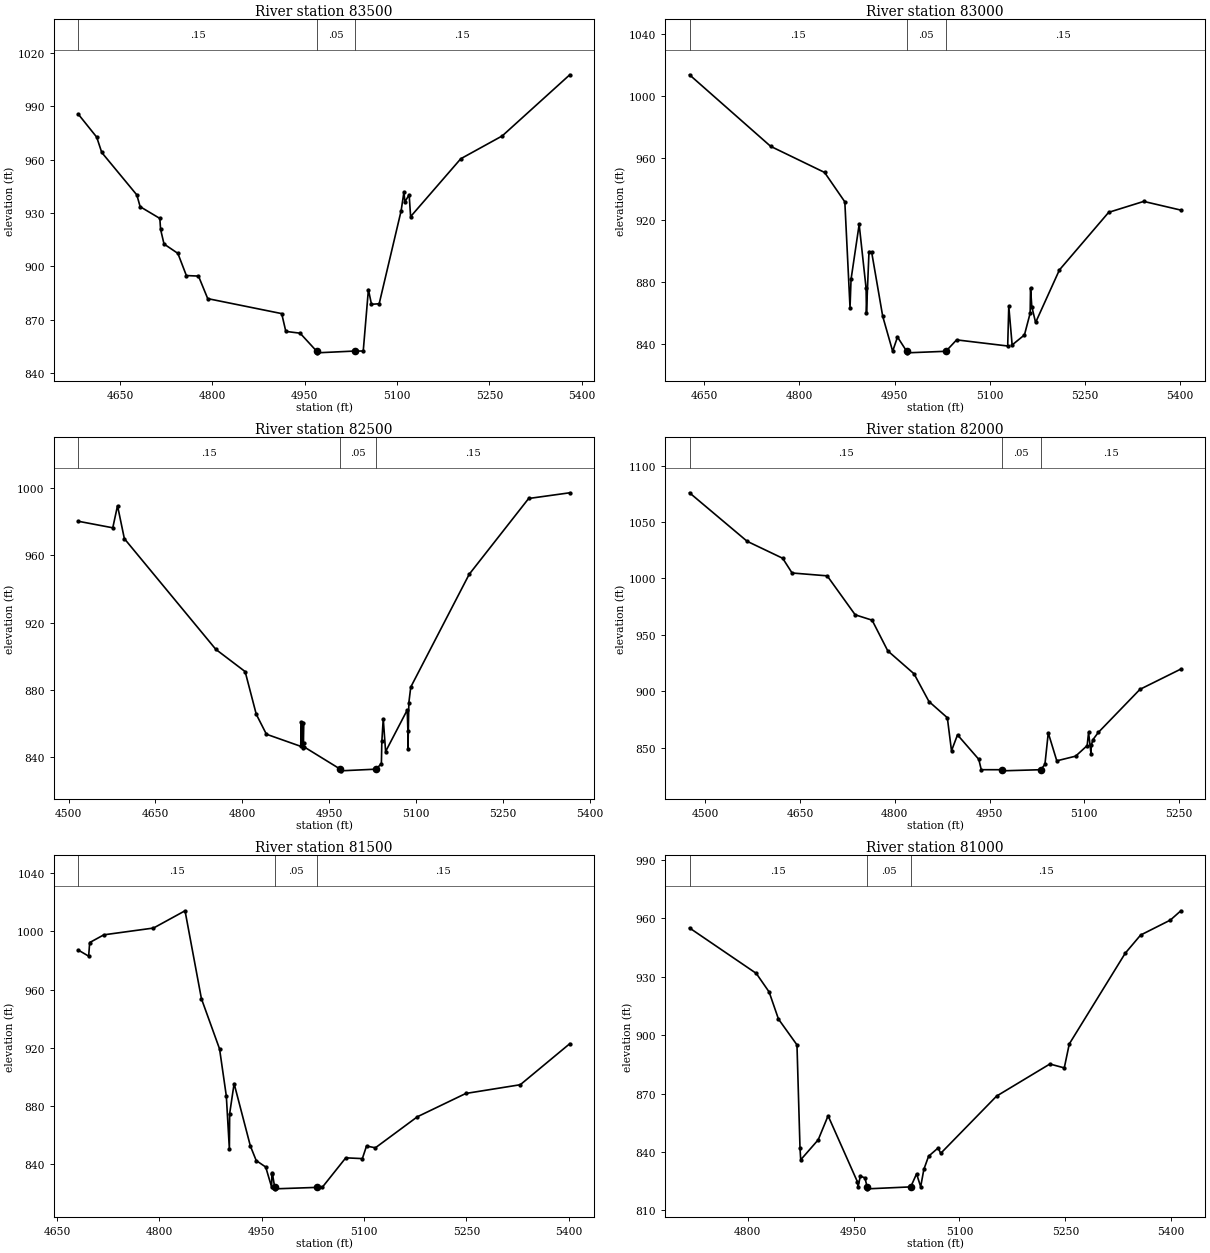
Type RM Length L Ch R = 1,83500,500,500,500
BEGIN DESCRIPTION:
Chauga River 167.0
END DESCRIPTION:
XS GIS Cut Line= 3
      1345597.70      1065152.80      1345182.74      1065201.43
      1344802.42      1065216.06
#Sta/Elev= 30
  4582.2  985.41  4611.9  972.59  4620.1  963.97  4677.1  940.12  4682.5  933.50
  4714.5  926.90  4715.7  920.78  4721.3  912.52  4743.8  907.26  4757.6  894.80
  4777.3  894.50  4792.3  881.83  4912.5  873.41  4919.2  863.41  4942.4  862.40
  4969.1  852.36  4969.6  851.36  5030.9  852.36  5045.0  852.38  5053.4  886.93
  5058.4  878.64  5070.9  878.95  5106.6  931.23  5111.1  941.71  5112.7  936.23
  5119.6  940.23  5122.0  927.92  5203.5  960.45  5270.9  973.29  5380.6 1007.64
#Mann=3,-1,0
  4582.2    0.15       0  4969.1    0.05       0  5030.9    0.15       0
Bank Sta=4969.1,5030.9
XS Rating Curve= 0
Exp/Cntr=0.3,0.1

Type RM Length L Ch R = 1,83000,500,500,500
BEGIN DESCRIPTION:
Chauga River 166.0
END DESCRIPTION:
XS GIS Cut Line= 3
      1345700.18      1064661.76      1345338.98      1064755.62
      1344968.16      1064908.77
#Sta/Elev= 30
  4626.8 1013.48  4754.7  967.34  4839.7  950.51  4871.6  931.55  4879.8  863.33
  4881.4  881.54  4894.2  917.00  4905.1  875.88  4905.7  859.59  4909.7  899.49
  4913.9  899.11  4931.3  857.78  4947.0  835.19  4954.6  844.40  4969.1  835.19
  4969.6  834.19  5030.9  835.19  5047.8  842.55  5128.3  838.60  5130.0  864.26
  5135.3  839.27  5154.7  845.73  5163.7  859.79  5164.3  876.04  5166.3  863.92
  5172.3  853.76  5209.8  887.64  5287.4  924.77  5342.7  931.83  5401.2  926.22
#Mann=3,-1,0
  4626.8    0.15       0  4969.1    0.05       0  5030.9    0.15       0
Bank Sta=4969.1,5030.9
XS Rating Curve= 0
Exp/Cntr=0.3,0.1

Type RM Length L Ch R = 1,82500,500,500,500
BEGIN DESCRIPTION:
Chauga River 165.0
END DESCRIPTION:
XS GIS Cut Line= 3
      1345666.97      1064405.69      1345200.54      1064280.66
      1344841.57      1064212.90
#Sta/Elev= 30
  4517.1  980.30  4576.4  976.42  4584.6  989.56  4596.4  969.96  4754.3  904.13
  4804.9  890.91  4824.1  865.53  4841.6  853.67  4900.8  846.47  4902.0  861.04
  4902.6  847.73  4904.7  845.60  4905.6  860.62  4905.7  848.22  4906.5  846.17
  4969.1  832.89  4969.6  831.89  5030.9  832.89  5040.1  836.20  5040.9  849.47
  5043.3  862.87  5047.4  843.37  5084.7  868.05  5085.9  855.31  5086.0  844.93
  5087.5  872.38  5090.8  881.70  5191.6  948.74  5294.3  993.85  5365.3  997.25
#Mann=3,-1,0
  4517.1    0.15       0  4969.1    0.05       0  5030.9    0.15       0
Bank Sta=4969.1,5030.9
XS Rating Curve= 0
Exp/Cntr=0.3,0.1

Type RM Length L Ch R = 1,82000,500,500,500
BEGIN DESCRIPTION:
Chauga River 164.0
END DESCRIPTION:
XS GIS Cut Line= 3
      1345862.79      1063808.03      1345337.83      1063801.24
      1345085.63      1063820.07
#Sta/Elev= 30
  4475.0 1076.03  4566.3 1032.98  4622.5 1017.95  4637.4 1004.89  4693.0 1002.35
  4737.3  967.80  4764.1  963.03  4788.9  935.82  4830.5  915.45  4854.1  890.88
  4883.2  876.50  4889.8  847.17  4899.3  861.30  4933.0  839.60  4936.9  830.39
  4969.1  830.39  4969.6  829.39  5030.9  830.39  5037.7  835.10  5043.0  863.04
  5056.5  838.27  5086.3  842.41  5104.6  851.79  5106.8  863.50  5110.7  844.47
  5111.1  852.09  5113.8  857.13  5122.2  863.43  5188.2  901.68  5252.9  919.66
#Mann=3,-1,0
  4475.0    0.15       0  4969.1    0.05       0  5030.9    0.15       0
Bank Sta=4969.1,5030.9
XS Rating Curve= 0
Exp/Cntr=0.3,0.1

Type RM Length L Ch R = 1,81500,500,500,500
BEGIN DESCRIPTION:
Chauga River 163.0
END DESCRIPTION:
XS GIS Cut Line= 3
      1345178.99      1063142.28      1345103.95      1063451.81
      1345019.33      1063844.19
#Sta/Elev= 30
  4681.5  987.12  4696.5  983.00  4698.0  992.35  4718.8  997.67  4791.5 1002.33
  4837.7 1014.20  4861.7  953.79  4888.3  919.20  4898.2  886.84  4902.7  850.17
  4903.1  874.74  4909.6  895.39  4933.4  852.53  4942.0  842.46  4955.9  838.02
  4964.6  824.16  4964.9  833.00  4965.5  834.14  4969.1  824.02  4969.6  823.02
  5030.9  824.02  5038.7  824.02  5073.2  844.34  5097.5  843.81  5103.6  852.45
  5116.6  851.24  5178.1  872.57  5249.1  888.60  5328.9  894.60  5401.4  922.81
#Mann=3,-1,0
  4681.5    0.15       0  4969.1    0.05       0  5030.9    0.15       0
Bank Sta=4969.1,5030.9
XS Rating Curve= 0
Exp/Cntr=0.3,0.1

Type RM Length L Ch R = 1,81000,436,436,436
BEGIN DESCRIPTION:
Chauga River 162.0
END DESCRIPTION:
XS GIS Cut Line= 3
      1344672.89      1063392.27      1344687.09      1063674.52
      1344690.97      1064088.20
#Sta/Elev= 30
  4717.4  955.05  4812.0  931.71  4830.2  922.19  4843.5  908.23  4869.7  894.99
  4874.0  841.97  4875.0  835.97  4899.8  846.24  4913.8  858.58  4955.4  824.64
  4956.3  822.06  4959.5  827.60  4966.0  826.69  4969.1  822.06  4969.6  821.06
  5030.9  822.06  5039.2  828.78  5045.0  822.12  5049.5  831.05  5056.2  837.80
  5069.7  842.05  5073.4  839.28  5152.6  868.69  5228.1  885.17  5248.5  883.17
  5255.6  895.47  5334.9  942.07  5356.7  951.39  5398.8  959.08  5413.7  963.86
#Mann=3,-1,0
  4717.4    0.15       0  4969.1    0.05       0  5030.9    0.15       0
Bank Sta=4969.1,5030.9
XS Rating Curve= 0
Exp/Cntr=0.3,0.1

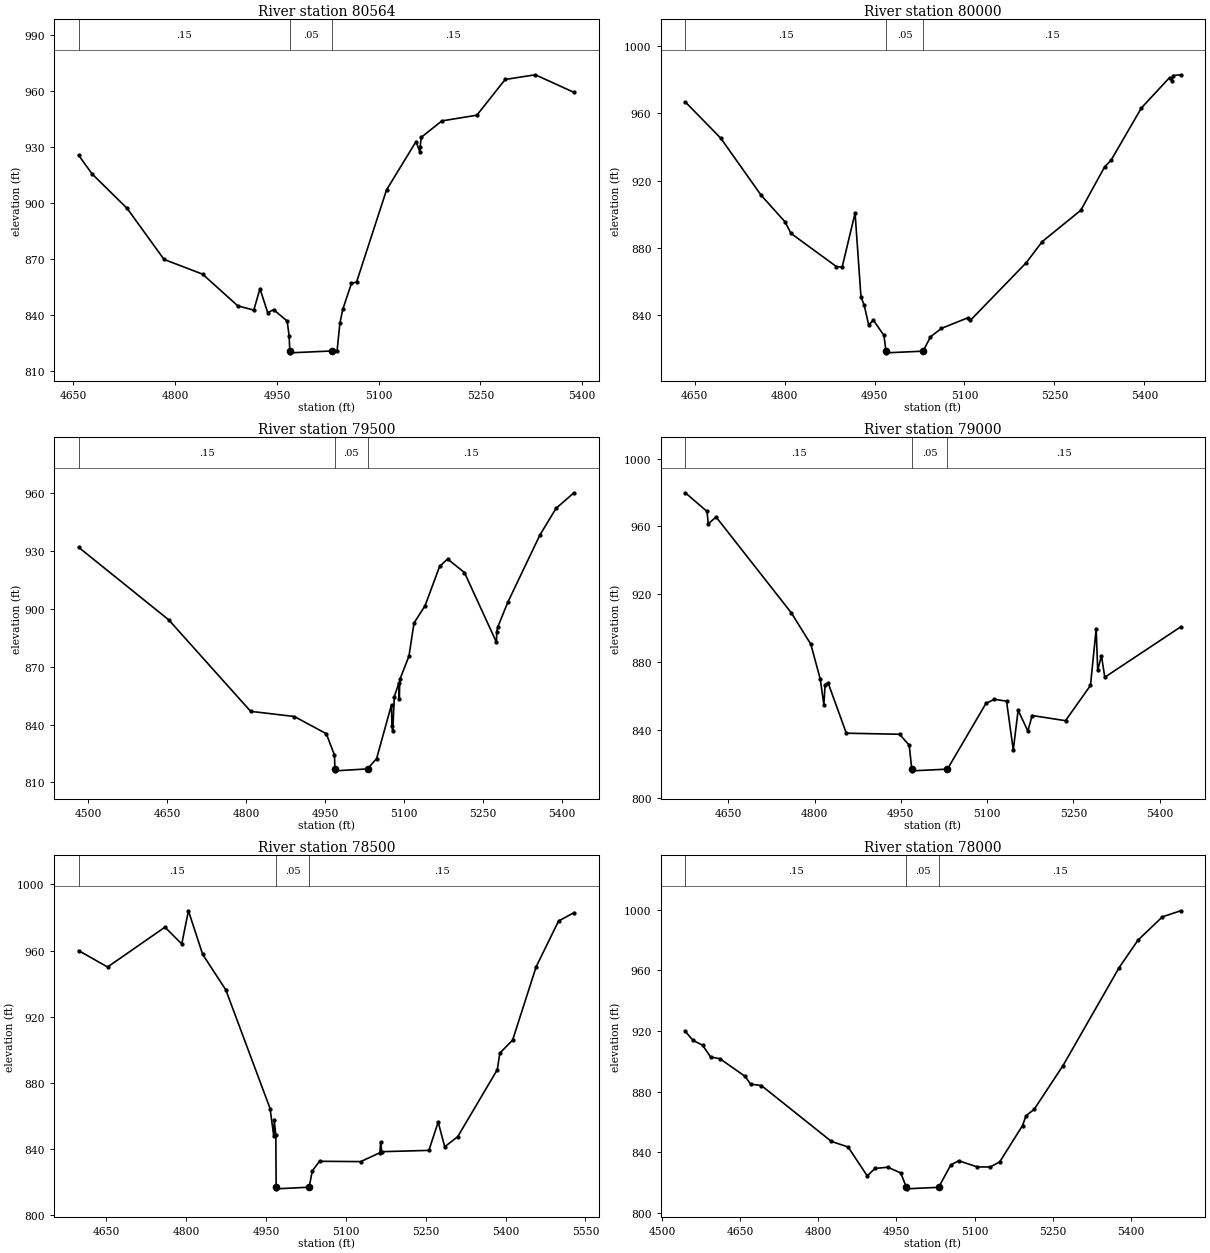
Type RM Length L Ch R = 1,80564,564,564,564
BEGIN DESCRIPTION:
Chauga River 161.0
END DESCRIPTION:
XS GIS Cut Line= 3
      1344588.56      1063392.30      1344290.40      1063560.63
      1344019.21      1063838.13
#Sta/Elev= 30
  4657.6  925.51  4677.5  915.48  4729.2  897.00  4783.5  869.68  4840.5  861.74
  4892.3  844.77  4915.9  842.51  4925.0  853.96  4936.5  841.08  4945.1  842.73
  4965.1  836.64  4968.0  828.71  4969.0  820.59  4969.5  819.59  5031.0  820.59
  5038.7  820.59  5042.9  835.55  5047.1  842.90  5059.9  856.82  5067.5  857.60
  5111.7  906.98  5155.2  932.87  5160.9  927.07  5161.1  930.01  5163.0  935.17
  5193.2  943.91  5244.8  946.98  5286.6  966.13  5331.0  968.64  5388.0  959.22
#Mann=3,-1,0
  4657.6    0.15       0  4969.0    0.05       0  5031.0    0.15       0
Bank Sta=4969,5031
XS Rating Curve= 0
Exp/Cntr=0.3,0.1

Type RM Length L Ch R = 1,80000,500,500,500
BEGIN DESCRIPTION:
Chauga River 160.0
END DESCRIPTION:
XS GIS Cut Line= 3
      1344672.89      1063060.93      1344310.43      1063012.37
      1343856.48      1062934.40
#Sta/Elev= 30
  4634.3  966.68  4693.4  945.16  4760.7  911.28  4800.4  895.54  4810.7  888.56
  4886.3  868.90  4895.9  868.55  4917.5  900.67  4927.3  850.91  4932.8  845.80
  4940.2  834.22  4948.1  837.01  4965.7  827.96  4969.0  818.63  4969.5  817.63
  5031.0  818.63  5043.3  827.14  5061.4  832.13  5105.6  838.45  5109.8  836.92
  5203.2  871.24  5229.6  883.69  5294.0  902.31  5333.8  928.13  5344.5  932.05
  5395.1  963.11  5442.2  981.20  5446.1  979.32  5448.6  982.40  5460.6  982.83
#Mann=3,-1,0
  4634.3    0.15       0  4969.0    0.05       0  5031.0    0.15       0
Bank Sta=4969,5031
XS Rating Curve= 0
Exp/Cntr=0.3,0.1

Type RM Length L Ch R = 1,79500,500,500,500
BEGIN DESCRIPTION:
Chauga River 159.0
END DESCRIPTION:
XS GIS Cut Line= 3
      1344901.81      1062751.23      1344433.94      1062528.00
      1344022.20      1062428.91
#Sta/Elev= 30
  4481.6  931.87  4652.8  894.30  4808.7  846.85  4891.9  844.15  4952.6  835.24
  4968.1  824.16  4969.0  817.00  4969.5  816.00  5031.0  817.00  5048.2  822.32
  5076.6  850.30  5077.3  839.44  5078.9  836.41  5081.9  854.47  5090.7  861.60
  5091.4  853.42  5092.4  863.36  5109.7  875.41  5119.4  892.64  5140.3  901.55
  5168.1  921.99  5183.2  925.80  5215.3  918.78  5276.1  882.66  5276.7  888.12
  5278.6  890.50  5297.7  903.38  5358.9  938.31  5389.6  952.10  5423.5  960.13
#Mann=3,-1,0
  4481.6    0.15       0  4969.0    0.05       0  5031.0    0.15       0
Bank Sta=4969,5031
XS Rating Curve= 0
Exp/Cntr=0.3,0.1

Type RM Length L Ch R = 1,79000,500,500,500
BEGIN DESCRIPTION:
Chauga River 158.0
END DESCRIPTION:
XS GIS Cut Line= 3
      1345019.34      1062359.63      1344681.97      1062101.65
      1344260.23      1061989.10
#Sta/Elev= 30
  4575.3  979.83  4613.0  968.83  4615.2  961.51  4628.8  965.54  4759.4  909.08
  4793.4  890.55  4809.8  870.07  4816.2  854.75  4818.3  866.68  4823.4  867.78
  4855.2  837.98  4947.8  837.35  4964.6  830.85  4969.0  816.77  4969.5  815.77
  5031.0  816.77  5098.0  855.55  5112.6  857.96  5133.8  856.87  5145.5  828.03
  5153.9  851.51  5170.8  839.27  5178.4  848.41  5236.3  845.36  5279.7  866.15
  5289.6  899.47  5292.3  875.05  5298.8  883.69  5304.6  871.00  5436.5  900.70
#Mann=3,-1,0
  4575.3    0.15       0  4969.0    0.05       0  5031.0    0.15       0
Bank Sta=4969,5031
XS Rating Curve= 0
Exp/Cntr=0.3,0.1

Type RM Length L Ch R = 1,78500,500,500,500
BEGIN DESCRIPTION:
Chauga River 157.0
END DESCRIPTION:
XS GIS Cut Line= 3
      1345338.67      1061868.60      1344973.71      1061699.81
      1344474.96      1061524.99
#Sta/Elev= 30
  4597.9  959.97  4652.3  950.03  4760.1  974.15  4791.7  963.99  4804.2  984.07
  4831.0  957.65  4874.4  936.21  4957.6  864.38  4964.5  847.67  4965.4  857.21
  4968.4  848.13  4969.0  816.77  4969.5  815.77  5031.0  816.77  5036.9  826.62
  5050.5  832.44  5127.9  832.26  5163.9  837.63  5165.4  844.28  5167.3  838.26
  5256.0  839.05  5273.4  856.17  5285.7  841.23  5310.1  847.33  5384.5  887.90
  5389.2  897.89  5413.3  905.83  5457.5  950.19  5499.6  977.89  5528.5  982.89
#Mann=3,-1,0
  4597.9    0.15       0  4969.0    0.05       0  5031.0    0.15       0
Bank Sta=4969,5031
XS Rating Curve= 0
Exp/Cntr=0.3,0.1

Type RM Length L Ch R = 1,78000,500,500,500
BEGIN DESCRIPTION:
Chauga River 156.0
END DESCRIPTION:
XS GIS Cut Line= 3
      1345597.74      1061326.35      1345152.33      1061232.92
      1344675.93      1061097.40
#Sta/Elev= 30
  4544.9  919.76  4559.6  913.86  4578.1  910.62  4593.5  902.82  4611.2  901.73
  4659.8  890.05  4670.1  884.98  4690.9  884.02  4825.0  847.20  4857.3  843.45
  4893.9  824.41  4908.8  829.31  4933.4  830.12  4958.3  826.32  4969.0  816.86
  4969.5  815.86  5031.0  816.86  5054.1  831.55  5069.4  834.39  5105.2  830.31
  5130.0  830.30  5148.1  833.63  5191.9  857.61  5198.6  864.09  5214.3  868.35
  5269.5  897.14  5377.2  961.80  5413.4  979.97  5460.3  995.36  5495.3  999.35
#Mann=3,-1,0
  4544.9    0.15       0  4969.0    0.05       0  5031.0    0.15       0
Bank Sta=4969,5031
XS Rating Curve= 0
Exp/Cntr=0.3,0.1