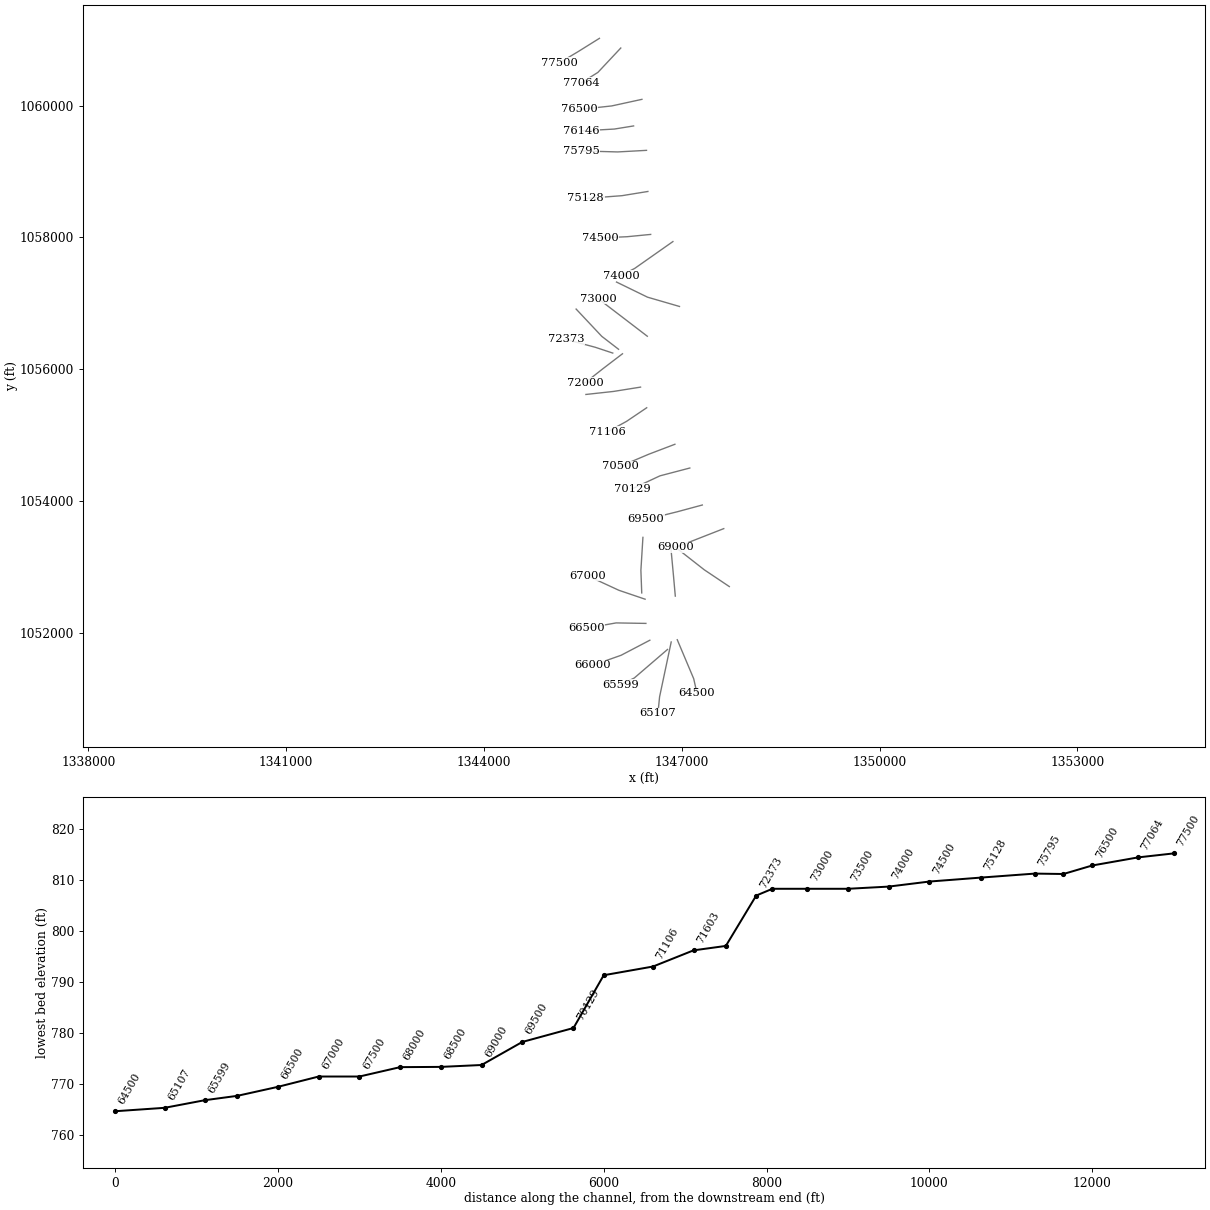
HEC-RAS study Chauga River.prj: Chauga River Limited Detail Study

--- Chauga River.g01 (geometry) --- (continued)

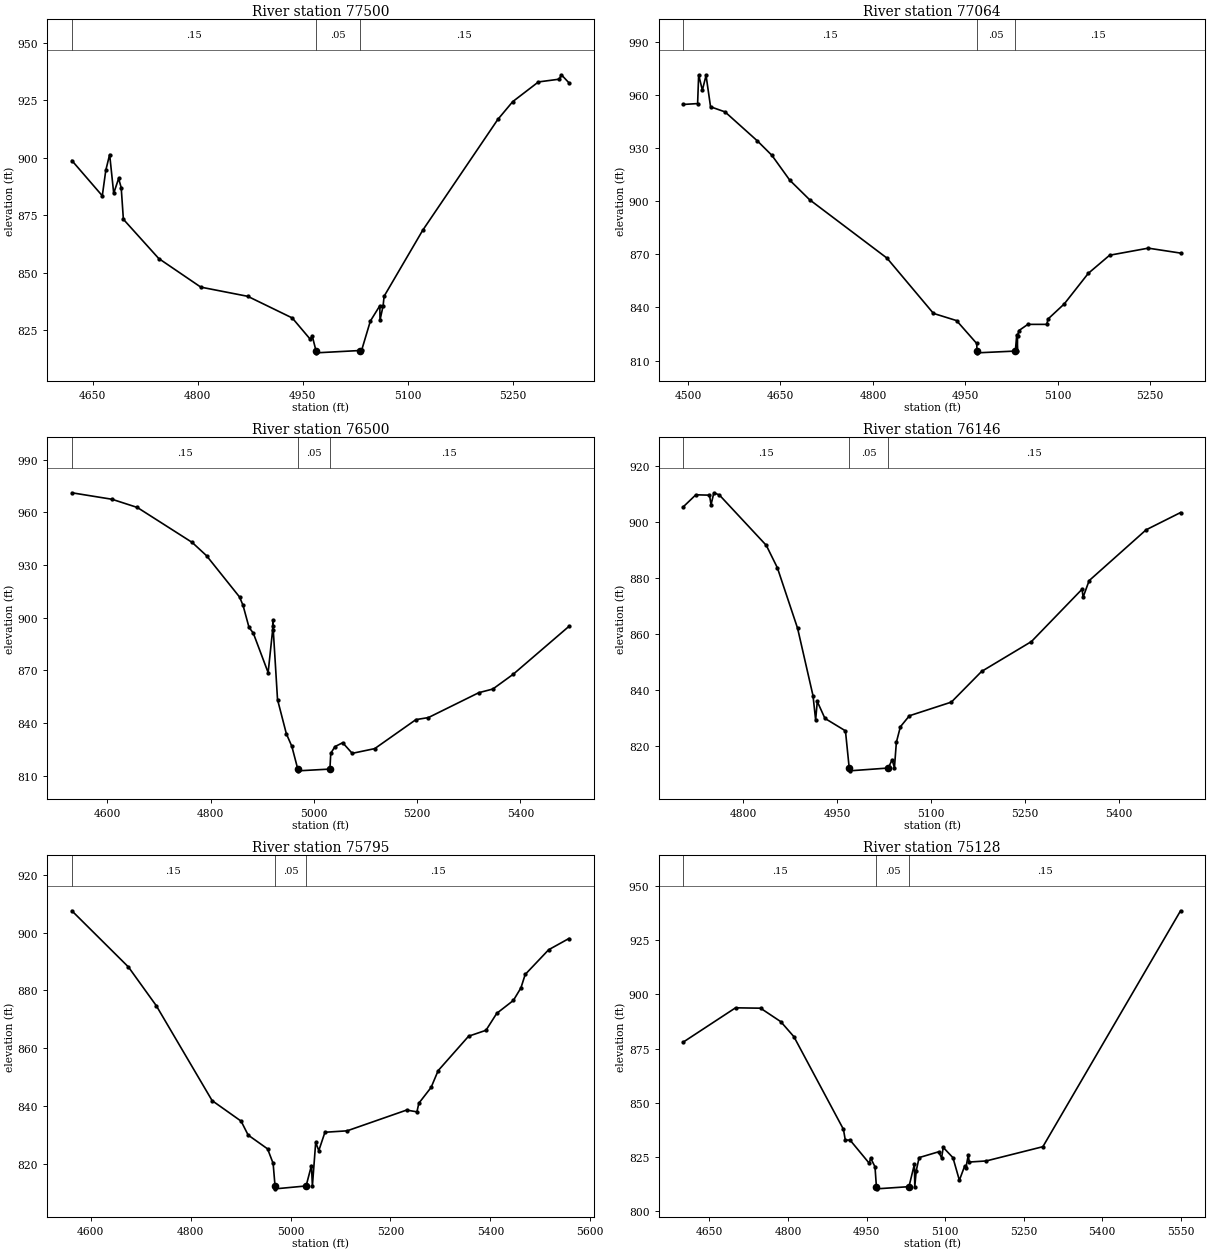
Type RM Length L Ch R = 1,77500,436,436,436
BEGIN DESCRIPTION:
Chauga River 155.0
END DESCRIPTION:
XS GIS Cut Line= 3
      1345751.36      1061022.08      1345429.30      1060820.95
      1345145.87      1060651.55
#Sta/Elev= 30
  4620.3  898.76  4663.8  883.42  4668.8  894.51  4674.3  901.36  4680.1  884.49
  4687.1  890.94  4690.8  886.98  4693.9  873.22  4744.4  856.17  4804.5  843.73
  4871.5  839.74  4935.1  830.33  4961.0  821.00  4963.5  822.63  4968.9  816.18
  4969.4  815.18  5031.1  816.18  5034.1  816.25  5046.6  828.99  5060.1  835.63
  5060.4  829.43  5064.8  835.55  5066.2  839.75  5121.4  868.46  5228.6  916.60
  5249.9  924.34  5286.6  932.90  5316.2  934.09  5319.4  936.01  5330.2  932.51
#Mann=3,-1,0
  4620.3    0.15       0  4968.9    0.05       0  5031.1    0.15       0
Bank Sta=4968.9,5031.1
XS Rating Curve= 0
Exp/Cntr=0.3,0.1

Type RM Length L Ch R = 1,77064,564,564,564
BEGIN DESCRIPTION:
Chauga River 154.0
END DESCRIPTION:
XS GIS Cut Line= 3
      1346075.02      1060875.02      1345727.89      1060504.80
      1345474.25      1060346.10
#Sta/Elev= 30
  4492.5  954.54  4515.5  955.02  4517.2  971.27  4523.2  962.59  4529.2  970.90
  4536.5  953.22  4560.0  950.33  4612.6  933.93  4636.1  925.80  4665.1  911.78
  4697.2  900.79  4822.8  867.84  4898.2  836.65  4935.7  832.59  4968.4  819.68
  4968.9  815.40  4969.4  814.40  5031.1  815.40  5033.3  824.37  5034.5  815.40
  5034.6  823.92  5037.0  826.99  5051.4  830.46  5082.1  830.46  5084.1  833.47
  5110.5  842.01  5149.5  859.26  5184.1  869.47  5246.8  873.46  5299.2  870.67
#Mann=3,-1,0
  4492.5    0.15       0  4968.9    0.05       0  5031.1    0.15       0
Bank Sta=4968.9,5031.1
XS Rating Curve= 0
Exp/Cntr=0.3,0.1

Type RM Length L Ch R = 1,76500,354,354,354
BEGIN DESCRIPTION:
Chauga River 153.0
END DESCRIPTION:
XS GIS Cut Line= 3
      1346396.02      1060096.04      1345938.20      1059996.13
      1345447.13      1059942.41
#Sta/Elev= 30
  4531.4  971.15  4609.3  967.45  4658.2  962.79  4764.4  942.88  4792.2  935.33
  4856.1  911.82  4862.9  907.06  4874.5  894.48  4882.7  891.28  4911.5  868.75
  4920.2  892.89  4920.7  898.78  4921.0  895.14  4929.7  853.38  4946.8  833.91
  4957.4  826.78  4968.9  813.81  4969.4  812.81  5031.1  813.81  5032.8  822.82
  5040.9  826.61  5055.9  828.82  5074.3  822.77  5117.9  825.46  5197.7  841.98
  5221.8  843.14  5319.4  857.31  5346.6  859.39  5386.0  867.79  5494.0  895.08
#Mann=3,-1,0
  4531.4    0.15       0  4968.9    0.05       0  5031.1    0.15       0
Bank Sta=4968.9,5031.1
XS Rating Curve= 0
Exp/Cntr=0.3,0.1

Type RM Length L Ch R = 1,76146,351,351,351
BEGIN DESCRIPTION:
Chauga River 152.0
END DESCRIPTION:
XS GIS Cut Line= 3
      1346269.48      1059692.37      1345977.48      1059645.09
      1345480.27      1059617.06
#Sta/Elev= 30
  4704.2  905.35  4724.0  909.58  4745.8  909.45  4748.3  906.06  4752.8  910.30
  4761.6  909.51  4836.5  891.55  4854.2  883.55  4886.5  861.95  4911.1  837.93
  4915.3  829.27  4917.9  835.87  4930.1  829.85  4962.9  825.40  4968.9  812.14
  4969.4  811.14  5031.1  812.14  5037.5  815.09  5041.1  812.22  5044.2  821.32
  5050.6  826.85  5065.0  830.78  5132.0  835.65  5180.3  846.59  5259.9  857.25
  5340.8  875.93  5342.3  873.01  5352.0  878.97  5443.0  897.09  5498.0  903.25
#Mann=3,-1,0
  4704.2    0.15       0  4968.9    0.05       0  5031.1    0.15       0
Bank Sta=4968.9,5031.1
XS Rating Curve= 0
Exp/Cntr=0.3,0.1

Type RM Length L Ch R = 1,75795,667,667,667
BEGIN DESCRIPTION:
Chauga River 151.0
END DESCRIPTION:
XS GIS Cut Line= 3
      1346465.32      1059321.84      1346028.18      1059297.82
      1345471.18      1059312.80
#Sta/Elev= 30
  4562.2  907.58  4675.5  888.10  4731.3  874.67  4843.0  841.79  4901.0  834.68
  4915.1  829.85  4954.0  825.07  4965.1  820.04  4968.9  812.22  4969.4  811.22
  5031.1  812.22  5041.8  819.30  5043.7  812.22  5050.3  827.33  5056.5  824.46
  5068.8  830.83  5113.1  831.32  5232.3  838.52  5252.9  837.90  5256.8  840.90
  5281.3  846.37  5295.4  852.18  5356.3  864.11  5391.1  866.16  5412.7  872.04
  5445.9  876.50  5461.1  880.87  5469.6  885.51  5516.6  894.08  5557.2  897.97
#Mann=3,-1,0
  4562.2    0.15       0  4968.9    0.05       0  5031.1    0.15       0
Bank Sta=4968.9,5031.1
XS Rating Curve= 0
Exp/Cntr=0.3,0.1

Type RM Length L Ch R = 1,75128,628,628,628
BEGIN DESCRIPTION:
Chauga River 150.0
END DESCRIPTION:
XS GIS Cut Line= 3
      1346486.42      1058697.65      1346091.89      1058633.59
      1345543.55      1058592.22
#Sta/Elev= 30
  4600.3  878.11  4699.8  893.85  4747.6  893.68  4786.2  887.48  4811.3  880.55
  4905.9  837.87  4909.5  832.89  4918.5  832.92  4955.2  822.22  4957.9  824.60
  4966.2  820.60  4968.9  811.43  4969.4  810.43  5031.1  811.43  5041.5  821.78
  5042.2  811.43  5045.0  818.79  5050.5  824.83  5087.6  827.49  5093.5  824.69
  5096.5  829.54  5115.1  824.79  5127.4  814.39  5137.5  820.93  5139.6  819.83
  5144.4  826.02  5146.3  822.78  5178.6  823.28  5286.9  829.85  5549.9  938.57
#Mann=3,-1,0
  4600.3    0.15       0  4968.9    0.05       0  5031.1    0.15       0
Bank Sta=4968.9,5031.1
XS Rating Curve= 0
Exp/Cntr=0.3,0.1

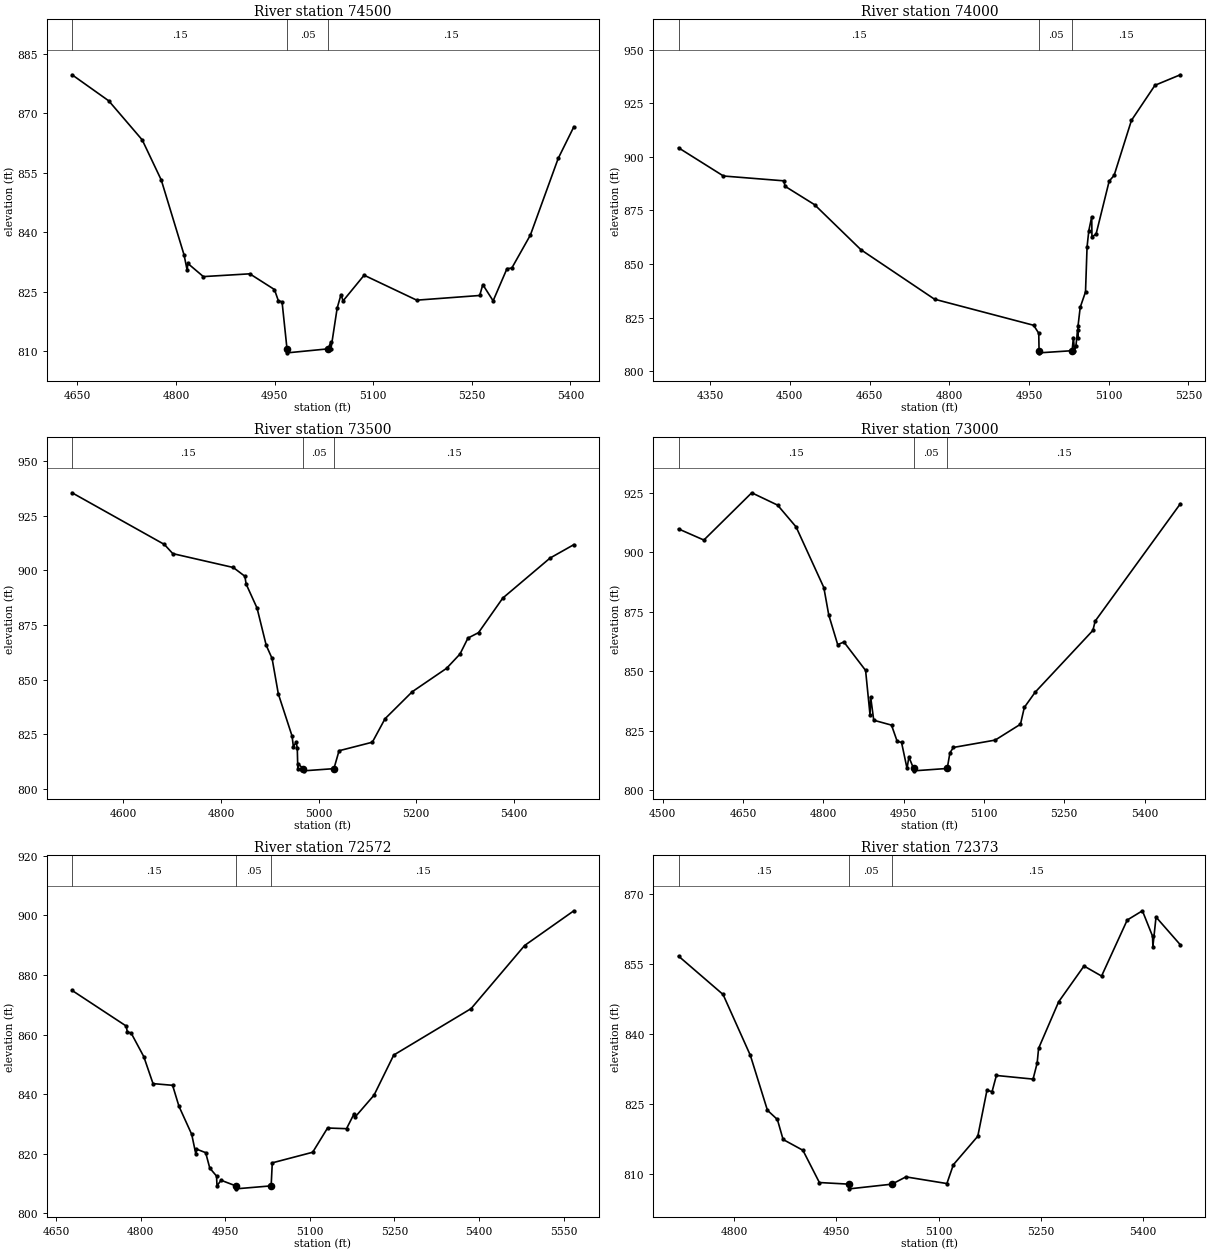
Type RM Length L Ch R = 1,74500,500,500,500
BEGIN DESCRIPTION:
Chauga River 149.0
END DESCRIPTION:
XS GIS Cut Line= 3
      1346528.60      1058045.75      1346172.29      1058011.00
      1345767.52      1057992.51
#Sta/Elev= 30
  4642.0  879.76  4697.8  873.19  4748.7  863.34  4777.7  853.22  4812.3  834.37
  4817.1  830.45  4818.0  832.21  4841.7  828.88  4912.3  829.58  4949.8  825.62
  4955.7  822.81  4961.4  822.49  4968.9  810.66  4969.4  809.66  5031.1  810.66
  5035.5  812.32  5035.8  810.72  5045.2  820.94  5051.0  824.33  5054.2  822.76
  5086.2  829.23  5166.2  822.94  5262.0  824.12  5266.7  826.86  5282.4  822.77
  5303.5  830.89  5310.8  831.03  5339.1  839.36  5381.4  858.68  5405.2  866.65
#Mann=3,-1,0
  4642.0    0.15       0  4968.9    0.05       0  5031.1    0.15       0
Bank Sta=4968.9,5031.1
XS Rating Curve= 0
Exp/Cntr=0.3,0.1

Type RM Length L Ch R = 1,74000,500,500,500
BEGIN DESCRIPTION:
Chauga River 148.0
END DESCRIPTION:
XS GIS Cut Line= 3
      1346865.98      1057937.30      1346285.55      1057529.27
      1346076.71      1057422.16
#Sta/Elev= 30
  4290.5  904.21  4375.0  891.07  4488.7  888.82  4490.8  886.30  4546.4  877.72
  4633.8  856.70  4772.2  833.66  4958.7  821.51  4968.3  817.80  4968.9  809.67
  4969.4  808.67  5031.1  809.67  5033.5  815.81  5035.5  809.67  5038.2  811.80
  5041.5  819.33  5041.9  815.73  5042.2  821.15  5046.3  829.87  5056.3  837.06
  5059.2  858.03  5062.5  865.58  5068.0  872.13  5068.4  862.69  5076.2  864.03
  5100.8  888.68  5110.1  891.35  5142.7  916.99  5187.0  933.35  5234.7  938.24
#Mann=3,-1,0
  4290.5    0.15       0  4968.9    0.05       0  5031.1    0.15       0
Bank Sta=4968.9,5031.1
XS Rating Curve= 0
Exp/Cntr=0.3,0.1

Type RM Length L Ch R = 1,73500,500,500,500
BEGIN DESCRIPTION:
Chauga River 147.0
END DESCRIPTION:
XS GIS Cut Line= 3
      1346965.44      1056952.20      1346480.44      1057093.28
      1346010.46      1057322.74
#Sta/Elev= 30
  4494.9  935.41  4684.0  911.78  4701.3  907.58  4825.2  901.24  4849.0  897.22
  4851.5  893.68  4873.9  882.68  4892.7  865.63  4904.7  859.64  4917.5  843.43
  4945.7  824.11  4948.3  819.33  4954.0  821.30  4956.3  818.71  4957.4  809.24
  4958.1  811.40  4968.6  809.24  4969.1  808.24  5031.4  809.24  5041.9  817.43
  5110.1  821.33  5136.1  832.06  5191.9  844.42  5262.2  855.12  5289.7  861.66
  5306.0  868.95  5327.7  871.45  5377.4  887.26  5474.3  905.56  5523.0  911.69
#Mann=3,-1,0
  4494.9    0.15       0  4968.6    0.05       0  5031.4    0.15       0
Bank Sta=4968.6,5031.4
XS Rating Curve= 0
Exp/Cntr=0.3,0.1

Type RM Length L Ch R = 1,73000,428,428,428
BEGIN DESCRIPTION:
Chauga River 146.0
END DESCRIPTION:
XS GIS Cut Line= 3
      1346477.40      1056500.32      1346104.05      1056786.32
      1345733.26      1057069.73
#Sta/Elev= 30
  4529.7  909.89  4577.0  905.22  4666.4  925.08  4714.7  919.89  4749.2  910.74
  4801.0  885.27  4810.2  873.74  4826.9  861.27  4838.5  862.38  4879.0  850.43
  4887.3  831.66  4888.4  839.36  4894.2  829.51  4927.4  827.45  4938.0  820.61
  4946.1  820.21  4956.4  809.24  4959.8  814.06  4968.6  809.24  4969.1  808.24
  5031.4  809.24  5036.5  815.83  5043.0  818.07  5121.0  821.16  5168.2  827.82
  5175.4  834.90  5195.7  841.30  5303.4  867.23  5307.7  871.16  5466.7  920.45
#Mann=3,-1,0
  4529.7    0.15       0  4968.6    0.05       0  5031.4    0.15       0
Bank Sta=4968.6,5031.4
XS Rating Curve= 0
Exp/Cntr=0.3,0.1

Type RM Length L Ch R = 1,72572,199,199,199
BEGIN DESCRIPTION:
Chauga River 145.0
END DESCRIPTION:
XS GIS Cut Line= 3
      1346041.43      1056302.50      1345786.76      1056498.73
      1345397.84      1056912.70
#Sta/Elev= 30
  4678.5  874.80  4774.5  862.85  4776.4  860.84  4783.1  860.54  4805.6  852.60
  4822.0  843.54  4856.7  842.97  4868.0  835.93  4890.6  826.51  4898.0  819.80
  4899.0  821.57  4915.3  820.38  4922.6  815.21  4934.6  812.52  4935.4  809.24
  4942.6  811.12  4968.6  809.24  4969.1  808.24  5031.4  809.24  5033.4  816.96
  5105.0  820.51  5131.4  828.65  5165.0  828.42  5177.9  833.23  5179.8  832.23
  5213.8  839.67  5248.7  853.12  5385.9  868.71  5480.7  889.87  5568.0  901.52
#Mann=3,-1,0
  4678.5    0.15       0  4968.6    0.05       0  5031.4    0.15       0
Bank Sta=4968.6,5031.4
XS Rating Curve= 0
Exp/Cntr=0.3,0.1

Type RM Length L Ch R = 1,72373,373,373,373
BEGIN DESCRIPTION:
Chauga River 144.5
END DESCRIPTION:
XS GIS Cut Line= 3
      1345953.41      1056244.82      1345685.71      1056333.46
      1345246.11      1056451.24
#Sta/Elev= 30
  4718.0  856.71  4783.4  848.50  4823.5  835.47  4848.6  823.72  4863.2  821.75
  4871.6  817.47  4900.7  815.16  4924.9  808.26  4968.6  807.91  4969.1  806.91
  5031.4  807.91  5052.0  809.47  5112.2  808.04  5121.7  812.07  5157.6  818.17
  5171.0  827.96  5178.6  827.73  5184.9  831.17  5238.8  830.39  5244.8  833.83
  5246.9  836.97  5276.4  846.94  5313.6  854.59  5339.4  852.44  5377.1  864.43
  5399.4  866.41  5414.3  860.97  5414.8  858.74  5419.4  865.07  5455.1  859.13
#Mann=3,-1,0
  4718.0    0.15       0  4968.6    0.05       0  5031.4    0.15       0
Bank Sta=4968.6,5031.4
XS Rating Curve= 0
Exp/Cntr=0.3,0.1

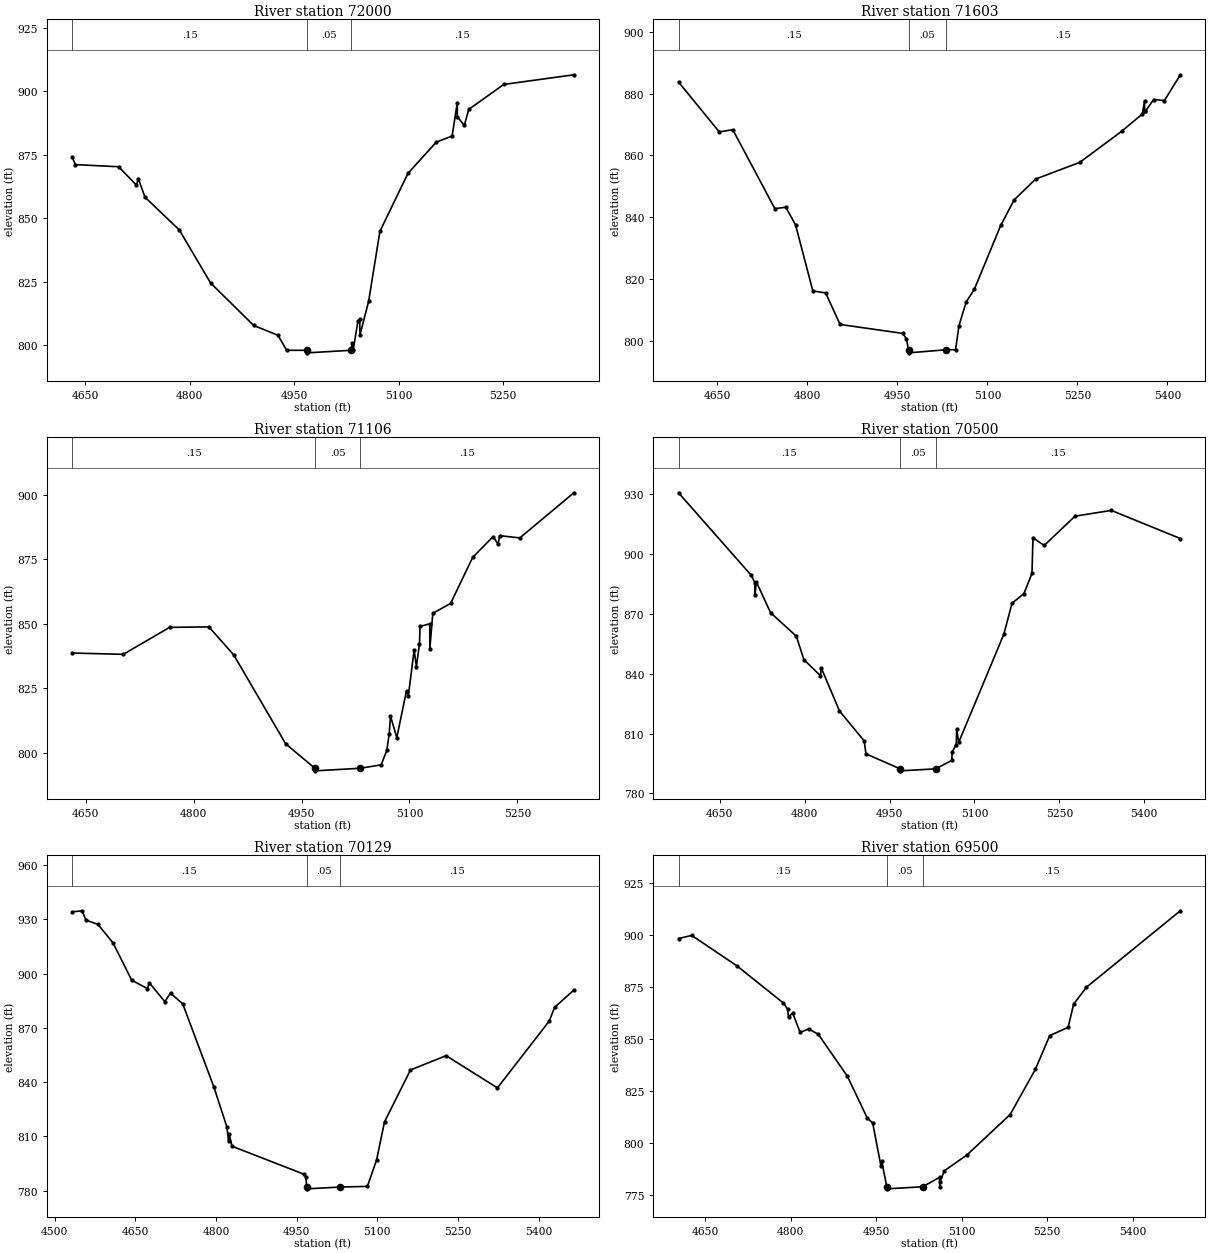
Type RM Length L Ch R = 1,72000,397,397,397
BEGIN DESCRIPTION:
Chauga River 144.0
END DESCRIPTION:
XS GIS Cut Line= 3
      1346100.84      1056234.06      1345807.82      1056010.12
      1345531.47      1055792.42
#Sta/Elev= 30
  4631.2  874.19  4636.0  871.14  4698.0  870.30  4723.7  863.06  4726.3  865.67
  4735.9  858.32  4785.2  845.41  4830.2  824.50  4892.1  807.80  4926.9  803.95
  4939.4  798.03  4968.6  798.03  4969.1  797.03  5031.4  798.03  5033.8  801.00
  5035.0  798.30  5041.7  809.45  5044.2  810.25  5044.7  804.10  5057.1  817.35
  5073.3  844.89  5113.6  867.70  5154.2  879.99  5177.0  882.40  5184.4  895.58
  5184.5  889.98  5194.5  886.61  5200.9  892.89  5251.2  902.71  5351.8  906.51
#Mann=3,-1,0
  4631.2    0.15       0  4968.6    0.05       0  5031.4    0.15       0
Bank Sta=4968.6,5031.4
XS Rating Curve= 0
Exp/Cntr=0.3,0.1

Type RM Length L Ch R = 1,71603,497,497,497
BEGIN DESCRIPTION:
Chauga River 143.0
END DESCRIPTION:
XS GIS Cut Line= 3
      1346374.91      1055727.94      1345965.51      1055662.46
      1345546.52      1055616.48
#Sta/Elev= 30
  4585.4  883.77  4653.2  867.64  4675.8  868.34  4745.9  842.81  4764.1  843.26
  4780.3  837.60  4809.2  816.18  4830.5  815.55  4854.6  805.34  4959.0  802.45
  4965.0  800.73  4968.6  797.16  4969.1  796.16  5031.4  797.16  5047.0  797.16
  5052.7  804.99  5064.8  812.67  5078.2  816.70  5122.2  837.36  5144.6  845.64
  5180.5  852.38  5254.0  857.78  5323.5  867.79  5358.1  873.41  5361.9  877.62
  5362.0  874.29  5363.0  874.24  5377.1  878.11  5395.0  877.77  5421.5  886.11
#Mann=3,-1,0
  4585.4    0.15       0  4968.6    0.05       0  5031.4    0.15       0
Bank Sta=4968.6,5031.4
XS Rating Curve= 0
Exp/Cntr=0.3,0.1

Type RM Length L Ch R = 1,71106,606,606,606
BEGIN DESCRIPTION:
Chauga River 142.0
END DESCRIPTION:
XS GIS Cut Line= 3
      1346468.29      1055414.62      1346162.70      1055208.16
      1345874.83      1055050.11
#Sta/Elev= 30
  4631.2  838.66  4702.4  838.15  4766.6  848.60  4821.3  848.80  4855.8  837.93
  4928.0  803.47  4968.6  793.99  4969.1  792.99  5031.4  793.99  5060.7  795.30
  5068.5  800.92  5071.9  807.36  5073.6  814.22  5082.4  805.83  5095.9  824.13
  5098.3  821.86  5106.5  839.85  5109.6  833.36  5113.9  842.20  5114.7  848.96
  5128.2  850.00  5128.3  840.31  5132.4  854.05  5157.2  857.90  5187.8  875.73
  5216.2  883.80  5223.1  880.85  5225.3  884.16  5253.3  883.28  5328.4  900.78
#Mann=3,-1,0
  4631.2    0.15       0  4968.6    0.05       0  5031.4    0.15       0
Bank Sta=4968.6,5031.4
XS Rating Curve= 0
Exp/Cntr=0.3,0.1

Type RM Length L Ch R = 1,70500,371,371,371
BEGIN DESCRIPTION:
Chauga River 141.0
END DESCRIPTION:
XS GIS Cut Line= 3
      1346896.14      1054860.36      1346500.86      1054709.76
      1346073.74      1054528.99
#Sta/Elev= 30
  4577.0  930.83  4705.6  889.38  4711.8  885.70  4712.1  879.68  4714.5  886.12
  4739.7  870.61  4785.2  858.85  4798.5  847.09  4827.8  839.01  4829.4  842.83
  4861.4  821.35  4905.2  806.27  4908.2  799.82  4968.6  792.28  4969.1  791.28
  5031.4  792.28  5060.2  796.57  5060.3  800.75  5067.8  804.35  5068.5  812.22
  5072.2  805.64  5151.9  859.83  5166.4  875.42  5187.3  880.17  5201.6  890.34
  5203.4  908.25  5223.2  904.38  5277.8  919.10  5341.8  921.98  5463.8  907.87
#Mann=3,-1,0
  4577.0    0.15       0  4968.6    0.05       0  5031.4    0.15       0
Bank Sta=4968.6,5031.4
XS Rating Curve= 0
Exp/Cntr=0.3,0.1

Type RM Length L Ch R = 1,70129,629,629,629
BEGIN DESCRIPTION:
Chauga River 140.0
END DESCRIPTION:
XS GIS Cut Line= 3
      1347122.18      1054499.92      1346669.71      1054381.15
      1346247.82      1054184.18
#Sta/Elev= 30
  4532.2  934.09  4550.9  934.71  4557.8  929.57  4580.4  927.17  4608.5  916.88
  4643.0  896.38  4672.4  891.65  4675.8  894.90  4704.8  884.45  4715.3  889.16
  4738.0  883.26  4795.7  837.48  4820.2  815.17  4823.3  807.39  4824.6  811.09
  4829.7  804.50  4963.4  789.03  4967.1  787.52  4968.6  781.93  4969.1  780.93
  5031.4  781.93  5081.5  782.28  5098.6  796.88  5113.4  817.98  5161.7  846.67
  5228.0  854.59  5323.4  836.75  5419.9  873.75  5429.8  881.30  5465.6  890.88
#Mann=3,-1,0
  4532.2    0.15       0  4968.6    0.05       0  5031.4    0.15       0
Bank Sta=4968.6,5031.4
XS Rating Curve= 0
Exp/Cntr=0.3,0.1

Type RM Length L Ch R = 1,69500,500,500,500
BEGIN DESCRIPTION:
Chauga River 139.0
END DESCRIPTION:
XS GIS Cut Line= 3
      1347311.86      1053938.54      1346928.69      1053835.04
      1346459.32      1053718.62
#Sta/Elev= 30
  4603.1  898.31  4626.2  899.83  4705.3  885.27  4787.1  867.37  4794.4  864.51
  4796.1  860.71  4803.3  862.55  4816.5  853.30  4831.8  854.94  4848.5  852.31
  4899.2  832.31  4934.4  812.09  4943.8  809.80  4958.1  789.36  4959.5  791.54
  4968.6  779.19  4969.1  778.19  5031.4  779.19  5061.1  783.69  5061.5  779.22
  5062.0  781.61  5069.5  786.83  5109.3  794.48  5185.0  813.86  5229.1  835.48
  5254.5  851.75  5286.7  855.68  5296.4  866.85  5318.9  874.96  5483.6  911.65
#Mann=3,-1,0
  4603.1    0.15       0  4968.6    0.05       0  5031.4    0.15       0
Bank Sta=4968.6,5031.4
XS Rating Curve= 0
Exp/Cntr=0.3,0.1

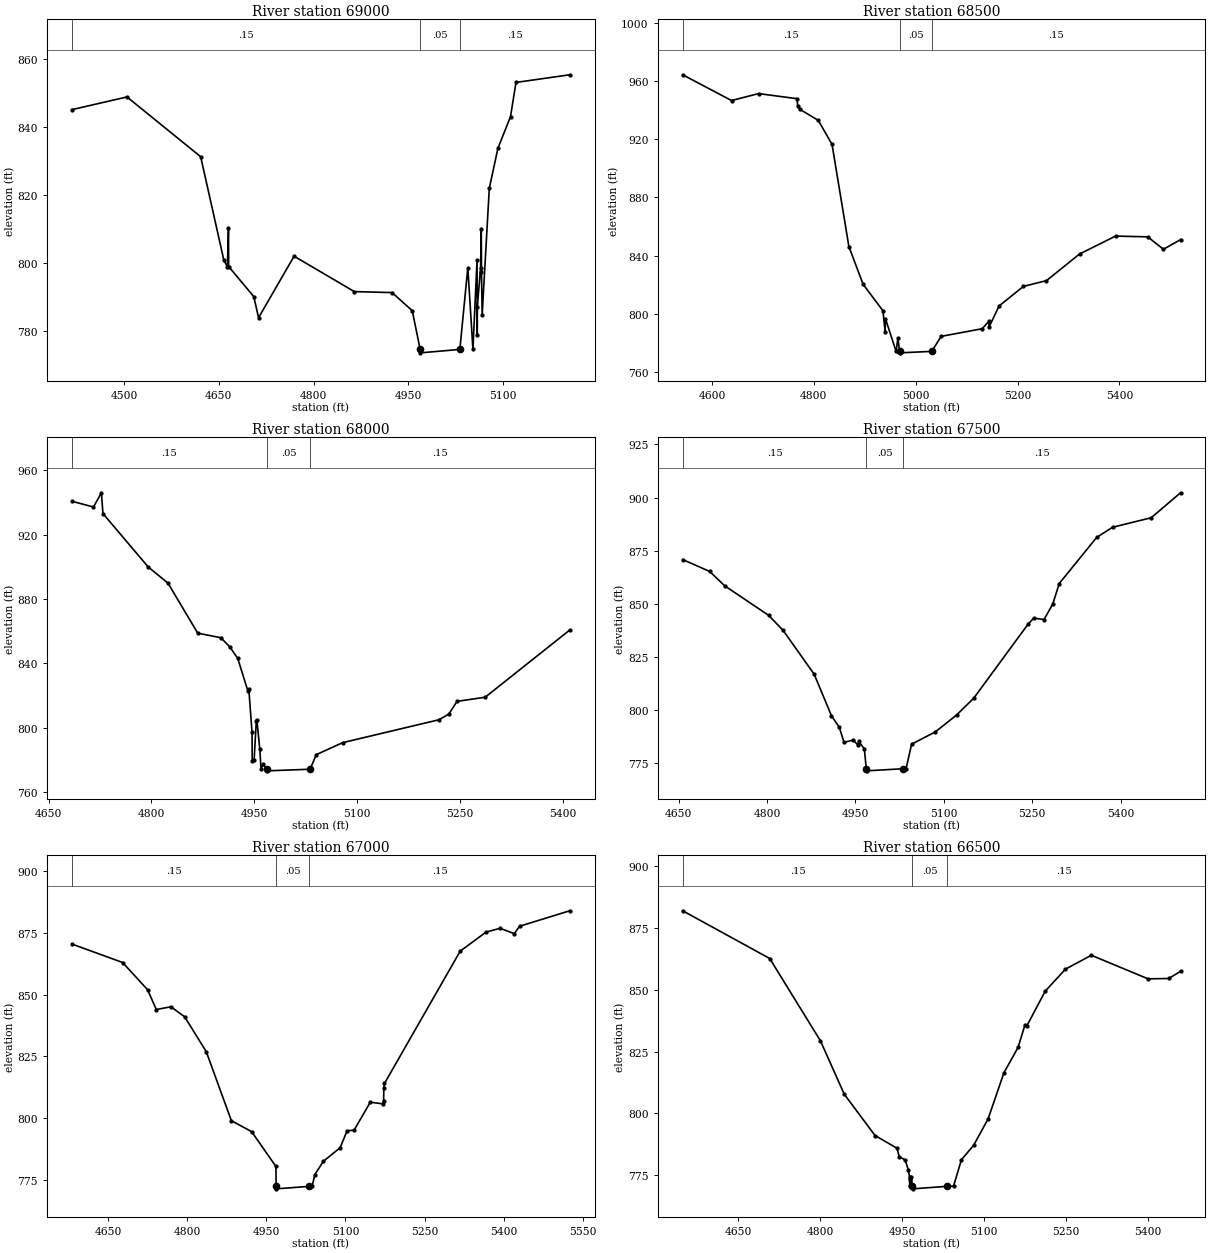
Type RM Length L Ch R = 1,69000,500,500,500
BEGIN DESCRIPTION:
Chauga River 138.0
END DESCRIPTION:
XS GIS Cut Line= 3
      1347637.18      1053580.04      1347094.79      1053367.62
      1346902.17      1053296.88
#Sta/Elev= 30
  4417.5  845.09  4504.7  848.82  4621.3  831.27  4657.8  801.03  4663.6  798.88
  4665.3  810.29  4665.6  799.01  4705.3  790.20  4712.9  783.98  4769.1  802.05
  4864.5  791.65  4924.1  791.37  4956.1  786.05  4968.6  774.67  4969.1  773.67
  5031.4  774.67  5044.0  798.68  5052.1  774.67  5058.6  800.89  5058.9  778.88
  5059.0  787.07  5064.2  798.63  5065.3  809.96  5065.6  797.47  5066.7  784.80
  5078.0  822.02  5091.7  833.79  5111.6  843.06  5120.2  853.08  5205.2  855.33
#Mann=3,-1,0
  4417.5    0.15       0  4968.6    0.05       0  5031.4    0.15       0
Bank Sta=4968.6,5031.4
XS Rating Curve= 0
Exp/Cntr=0.3,0.1

Type RM Length L Ch R = 1,68500,500,500,500
BEGIN DESCRIPTION:
Chauga River 137.0
END DESCRIPTION:
XS GIS Cut Line= 3
      1347721.50      1052700.42      1347341.46      1052955.12
      1346932.24      1053275.80
#Sta/Elev= 30
  4542.5  964.19  4638.4  946.50  4691.4  951.27  4767.1  947.77  4768.1  942.88
  4772.1  940.59  4808.8  932.86  4835.7  916.40  4868.8  846.24  4896.7  820.36
  4935.7  802.15  4940.0  787.45  4940.5  796.78  4961.5  774.30  4965.0  783.31
  4968.5  774.30  4969.0  773.30  5031.5  774.30  5049.9  784.61  5130.4  789.85
  5143.8  794.99  5143.9  790.93  5163.6  805.46  5211.5  818.93  5256.7  822.87
  5321.6  841.13  5392.3  853.44  5455.4  852.94  5486.4  844.41  5519.9  851.02
#Mann=3,-1,0
  4542.5    0.15       0  4968.5    0.05       0  5031.5    0.15       0
Bank Sta=4968.5,5031.5
XS Rating Curve= 0
Exp/Cntr=0.3,0.1

Type RM Length L Ch R = 1,68000,500,500,500
BEGIN DESCRIPTION:
Chauga River 136.0
END DESCRIPTION:
XS GIS Cut Line= 3
      1346902.14      1052555.76      1346874.00      1052870.51
      1346835.86      1053278.83
#Sta/Elev= 30
  4684.0  940.66  4715.5  937.08  4727.1  945.92  4729.3  933.05  4795.3  899.87
  4824.1  889.86  4867.6  858.73  4901.3  855.92  4914.0  850.40  4925.9  843.10
  4940.6  823.02  4942.1  823.89  4946.8  797.09  4947.0  779.41  4949.8  779.84
  4953.0  804.24  4953.9  804.51  4958.1  786.72  4959.9  774.43  4962.9  777.21
  4968.5  774.25  4969.0  773.25  5031.5  774.25  5040.5  783.31  5079.0  790.76
  5219.5  804.98  5233.7  808.45  5245.8  816.41  5286.8  818.95  5410.1  860.67
#Mann=3,-1,0
  4684.0    0.15       0  4968.5    0.05       0  5031.5    0.15       0
Bank Sta=4968.5,5031.5
XS Rating Curve= 0
Exp/Cntr=0.3,0.1

Type RM Length L Ch R = 1,67500,500,500,500
BEGIN DESCRIPTION:
Chauga River 135.0
END DESCRIPTION:
XS GIS Cut Line= 3
      1346393.02      1052603.99      1346380.23      1052946.76
      1346411.10      1053447.51
#Sta/Elev= 30
  4657.0  870.81  4702.6  865.24  4728.2  858.48  4802.9  844.55  4827.4  837.47
  4880.1  816.85  4909.4  797.35  4922.8  791.84  4930.7  784.80  4946.2  785.89
  4954.2  783.58  4955.7  785.26  4965.2  781.72  4968.5  772.41  4969.0  771.41
  5031.5  772.41  5036.0  772.41  5045.4  783.95  5085.6  789.73  5121.7  797.66
  5150.8  805.58  5243.0  840.41  5252.7  843.26  5270.1  842.59  5284.9  849.87
  5295.9  859.54  5359.4  881.23  5386.4  886.00  5452.0  890.49  5501.7  902.23
#Mann=3,-1,0
  4657.0    0.15       0  4968.5    0.05       0  5031.5    0.15       0
Bank Sta=4968.5,5031.5
XS Rating Curve= 0
Exp/Cntr=0.3,0.1

Type RM Length L Ch R = 1,67000,500,500,500
BEGIN DESCRIPTION:
Chauga River 134.0
END DESCRIPTION:
XS GIS Cut Line= 3
      1346444.22      1052508.81      1346047.42      1052643.68
      1345570.58      1052864.29
#Sta/Elev= 30
  4580.9  870.52  4677.2  863.04  4724.6  851.99  4741.1  843.99  4768.8  845.12
  4794.9  841.05  4835.8  826.98  4883.5  799.02  4922.0  794.56  4968.0  780.47
  4968.5  772.41  4969.0  771.41  5031.5  772.41  5036.7  772.41  5042.0  777.21
  5057.9  782.53  5089.8  788.05  5103.1  794.93  5116.3  795.14  5147.1  806.50
  5170.3  805.82  5172.3  806.85  5172.8  812.37  5174.0  814.08  5317.7  867.65
  5366.9  875.38  5393.5  876.88  5420.3  874.72  5430.3  877.71  5525.4  883.98
#Mann=3,-1,0
  4580.9    0.15       0  4968.5    0.05       0  5031.5    0.15       0
Bank Sta=4968.5,5031.5
XS Rating Curve= 0
Exp/Cntr=0.3,0.1

Type RM Length L Ch R = 1,66500,500,500,500
BEGIN DESCRIPTION:
Chauga River 133.0
END DESCRIPTION:
XS GIS Cut Line= 3
      1346456.30      1052141.28      1346004.86      1052148.78
      1345552.55      1052068.98
#Sta/Elev= 30
  4548.5  882.02  4707.7  862.69  4800.5  829.34  4844.1  807.72  4900.4  790.99
  4940.6  785.84  4944.6  782.48  4955.6  781.06  4961.2  777.12  4963.5  774.16
  4963.9  770.39  4964.0  773.36  4967.0  774.34  4968.5  770.39  4969.0  769.39
  5031.5  770.39  5044.0  770.52  5058.5  781.20  5080.9  787.06  5107.3  797.76
  5136.2  816.40  5162.0  826.65  5174.9  835.91  5178.0  835.34  5211.6  849.41
  5248.5  858.34  5296.1  864.00  5399.9  854.45  5437.6  854.59  5459.3  857.47
#Mann=3,-1,0
  4548.5    0.15       0  4968.5    0.05       0  5031.5    0.15       0
Bank Sta=4968.5,5031.5
XS Rating Curve= 0
Exp/Cntr=0.3,0.1

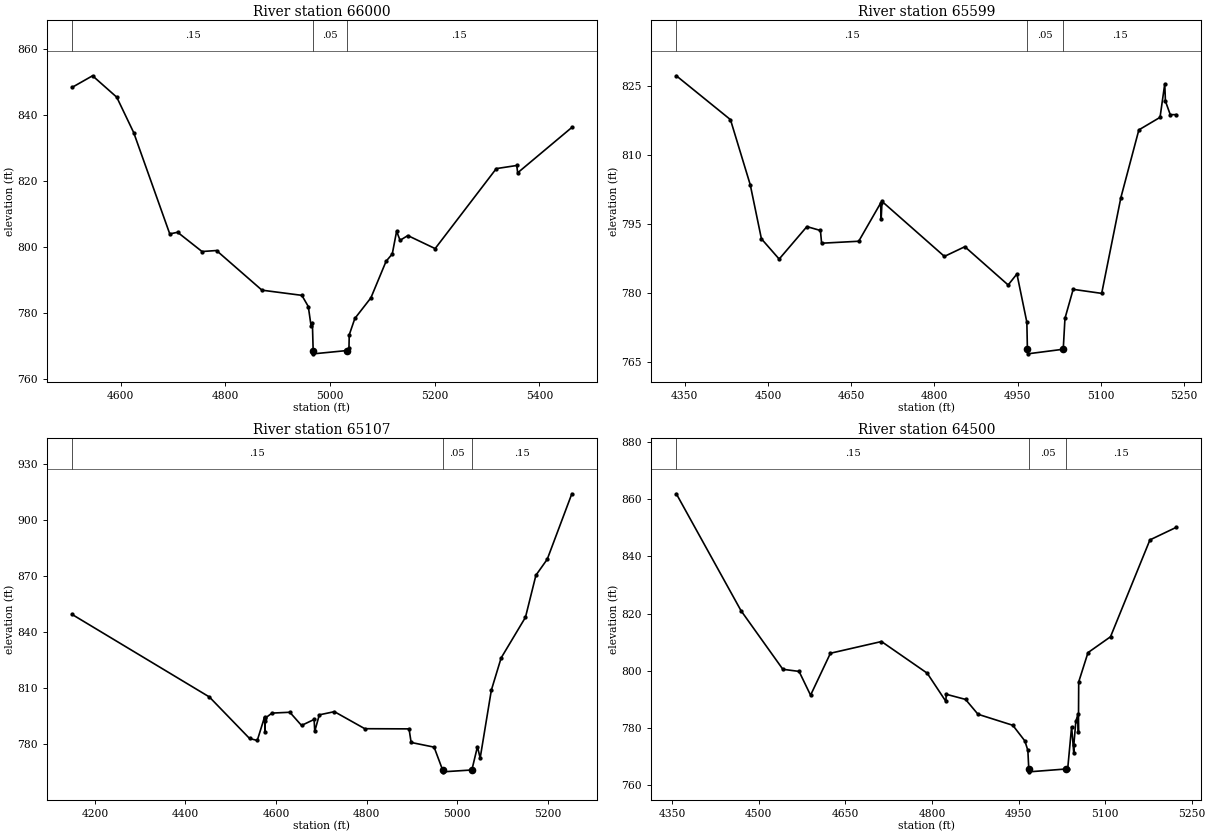
Type RM Length L Ch R = 1,66000,401,401,401
BEGIN DESCRIPTION:
Chauga River 132.0
END DESCRIPTION:
XS GIS Cut Line= 3
      1346516.07      1051886.07      1346079.35      1051657.32
      1345643.91      1051503.54
#Sta/Elev= 30
  4507.0  848.46  4546.3  852.00  4592.5  845.51  4624.9  834.76  4693.8  804.01
  4708.8  804.51  4755.4  798.67  4783.1  798.97  4869.9  786.94  4946.1  785.37
  4958.4  781.98  4963.8  776.00  4966.2  777.12  4967.7  768.62  4968.2  767.62
  5032.3  768.62  5036.1  769.43  5036.6  773.38  5047.3  778.35  5078.0  784.62
  5107.0  795.71  5118.8  797.93  5127.1  804.83  5133.7  802.07  5148.5  803.51
  5200.7  799.56  5317.5  823.83  5356.6  824.78  5358.3  822.55  5461.8  836.32
#Mann=3,-1,0
  4507.0    0.15       0  4967.7    0.05       0  5032.3    0.15       0
Bank Sta=4967.7,5032.3
XS Rating Curve= 0
Exp/Cntr=0.3,0.1

Type RM Length L Ch R = 1,65599,492,492,492
BEGIN DESCRIPTION:
Chauga River 131.0
END DESCRIPTION:
XS GIS Cut Line= 3
      1346783.83      1051745.81      1346279.42      1051312.14
      1346067.17      1051209.21
#Sta/Elev= 30
  4334.8  827.29  4432.4  817.74  4468.1  803.55  4488.2  791.80  4520.2  787.39
  4570.2  794.46  4594.6  793.61  4596.7  790.84  4663.6  791.27  4703.0  799.55
  4704.1  796.16  4705.6  799.94  4818.1  787.97  4854.9  790.08  4933.0  781.75
  4948.8  784.15  4966.7  773.64  4967.7  767.76  4968.2  766.76  5032.3  767.76
  5035.4  774.48  5050.2  780.80  5101.6  779.92  5136.2  800.77  5168.6  815.51
  5206.8  818.24  5215.3  825.54  5216.5  821.77  5225.2  818.83  5235.9  818.83
#Mann=3,-1,0
  4334.8    0.15       0  4967.7    0.05       0  5032.3    0.15       0
Bank Sta=4967.7,5032.3
XS Rating Curve= 0
Exp/Cntr=0.3,0.1

Type RM Length L Ch R = 1,65107,607,607,607
BEGIN DESCRIPTION:
Chauga River 130.0
END DESCRIPTION:
XS GIS Cut Line= 3
      1346839.93      1051859.55      1346663.84      1051027.38
      1346638.45      1050775.65
#Sta/Elev= 30
  4149.4  849.43  4452.7  805.29  4541.5  783.09  4558.5  782.04  4574.5  794.50
  4575.8  786.49  4575.9  792.50  4576.4  794.02  4591.0  796.66  4630.4  797.11
  4656.2  790.06  4684.0  793.27  4685.4  786.95  4695.5  795.73  4728.8  797.43
  4795.9  788.32  4893.6  788.23  4898.2  780.97  4948.9  778.47  4967.7  766.27
  4968.2  765.27  5032.3  766.27  5044.6  778.73  5050.6  772.61  5075.3  808.93
  5096.9  826.14  5150.6  847.86  5173.7  870.33  5198.7  878.88  5253.0  913.87
#Mann=3,-1,0
  4149.4    0.15       0  4967.7    0.05       0  5032.3    0.15       0
Bank Sta=4967.7,5032.3
XS Rating Curve= 0
Exp/Cntr=0.3,0.1

Type RM Length L Ch R = 1,64500,608,608,608
BEGIN DESCRIPTION:
Chauga River 129.0
END DESCRIPTION:
XS GIS Cut Line= 3
      1346931.72      1051893.73      1347181.43      1051301.20
      1347230.11      1051083.48
#Sta/Elev= 30
  4357.0  861.95  4469.1  821.02  4541.6  800.50  4569.7  799.76  4589.6  791.43
  4624.0  806.12  4712.5  810.22  4791.7  799.14  4824.1  789.25  4824.6  791.76
  4858.1  789.96  4879.7  784.76  4940.0  780.90  4960.9  775.42  4966.1  772.12
  4967.7  765.60  4968.2  764.60  5032.3  765.60  5035.1  765.60  5041.9  780.38
  5045.7  771.14  5045.8  774.10  5049.2  782.24  5053.1  784.92  5053.7  778.57
  5054.2  796.09  5070.3  806.34  5109.3  811.89  5177.6  845.80  5223.1  850.19
#Mann=3,-1,0
  4357.0    0.15       0  4967.7    0.05       0  5032.3    0.15       0
Bank Sta=4967.7,5032.3
XS Rating Curve= 0
Exp/Cntr=0.3,0.1