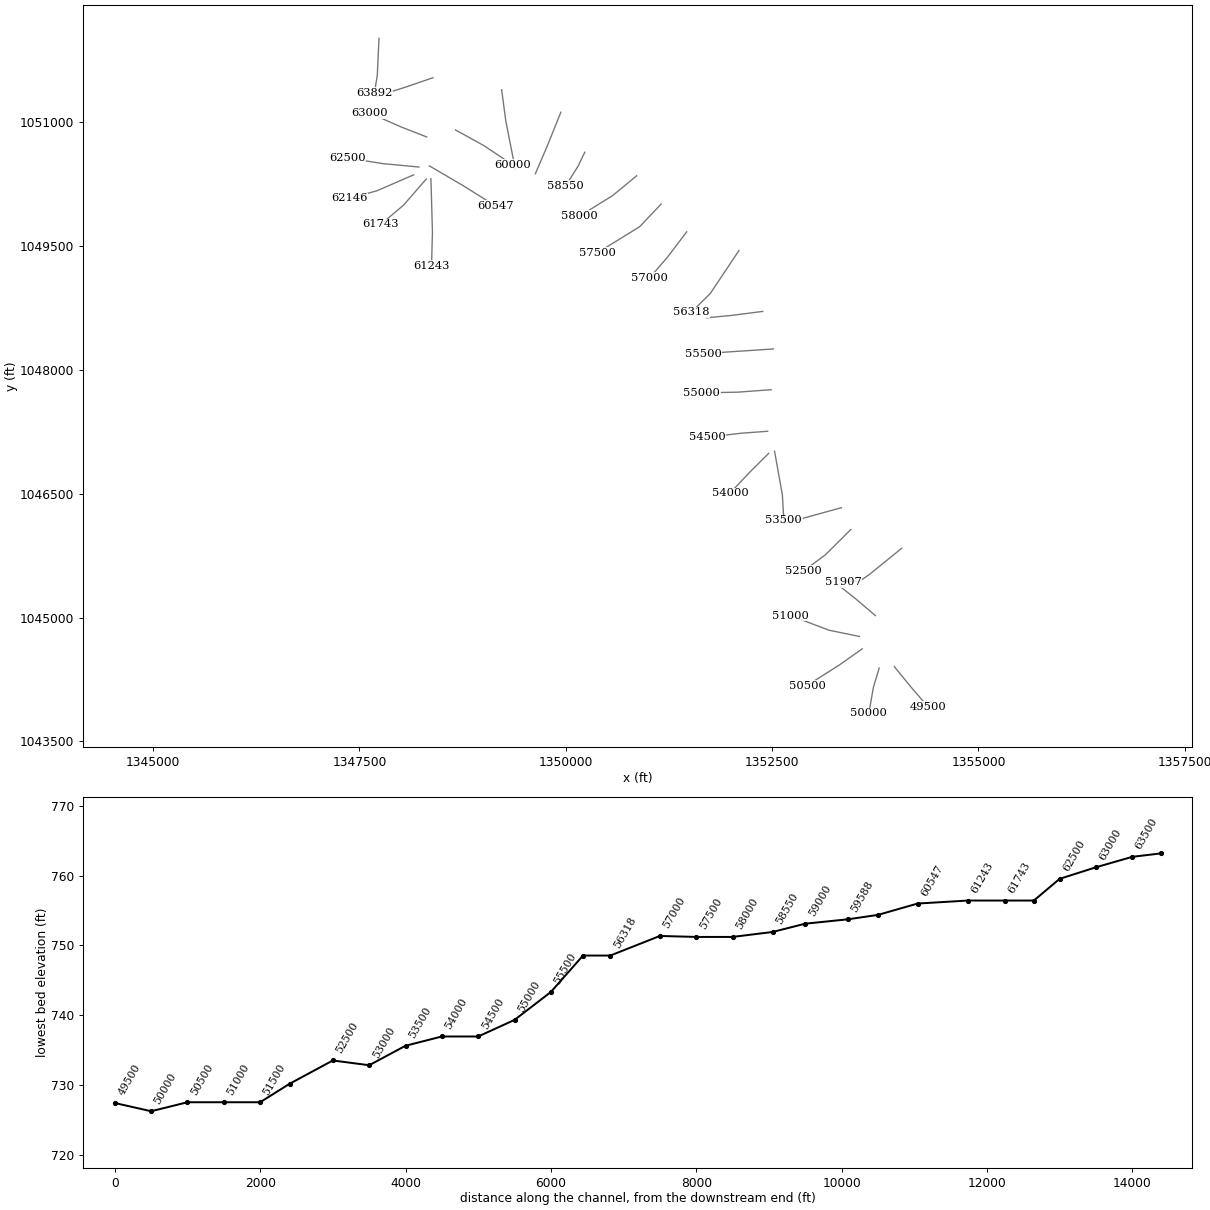
HEC-RAS study Chauga River.prj: Chauga River Limited Detail Study

--- Chauga River.g01 (geometry) --- (continued)

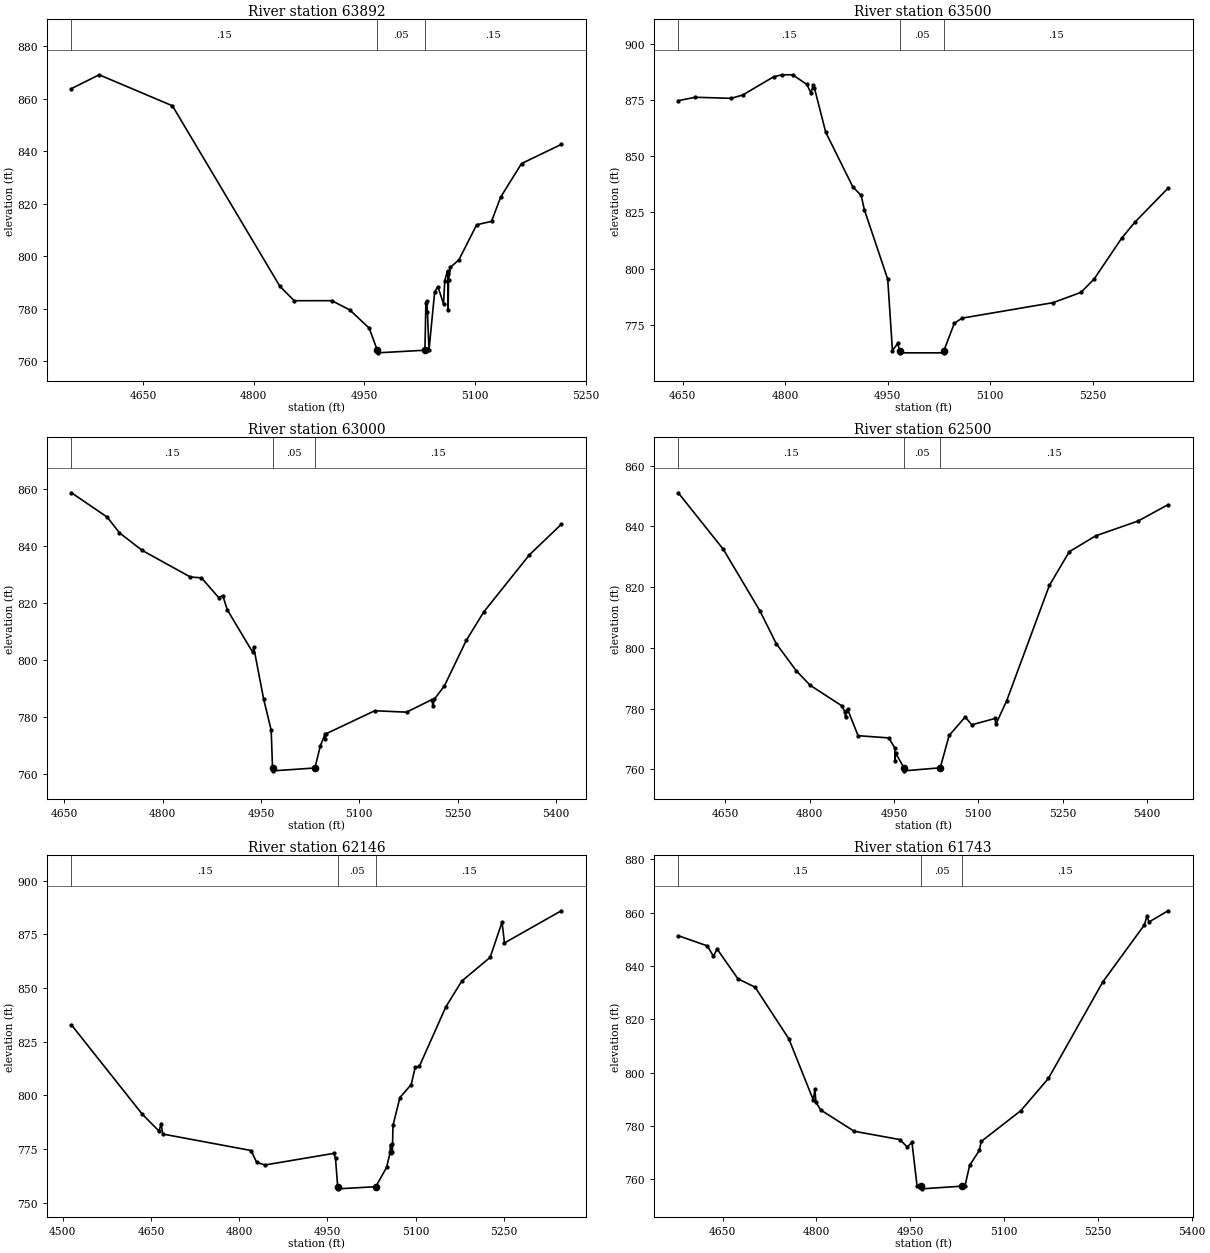
Type RM Length L Ch R = 1,63892,392,392,392
BEGIN DESCRIPTION:
Chauga River 128.0
END DESCRIPTION:
XS GIS Cut Line= 3
      1347737.61      1052017.16      1347716.89      1051570.84
      1347683.03      1051356.40
#Sta/Elev= 30
  4553.2  863.78  4590.7  869.03  4690.0  857.23  4835.7  788.51  4855.1  783.03
  4906.0  783.05  4930.2  779.57  4956.8  772.58  4967.7  764.19  4968.2  763.19
  5032.3  764.19  5033.6  782.28  5034.7  782.86  5035.7  778.85  5037.8  764.19
  5045.5  786.41  5049.9  788.40  5057.5  781.79  5059.2  790.69  5062.9  794.38
  5063.4  793.01  5063.7  779.52  5064.3  790.90  5066.7  795.69  5078.4  798.62
  5102.4  811.93  5122.6  813.24  5134.9  822.44  5163.2  835.23  5217.1  842.52
#Mann=3,-1,0
  4553.2    0.15       0  4967.7    0.05       0  5032.3    0.15       0
Bank Sta=4967.7,5032.3
XS Rating Curve= 0
Exp/Cntr=0.3,0.1

Type RM Length L Ch R = 1,63500,500,500,500
BEGIN DESCRIPTION:
Chauga River 127.0
END DESCRIPTION:
XS GIS Cut Line= 3
      1348391.98      1051539.99      1348054.61      1051424.46
      1347711.06      1051315.56
#Sta/Elev= 30
  4643.4  874.63  4668.4  876.14  4720.7  875.67  4737.6  877.10  4782.9  885.20
  4795.2  886.12  4810.9  886.11  4831.7  881.83  4837.7  878.01  4840.8  881.38
  4842.6  880.47  4859.3  860.63  4898.9  836.44  4911.2  832.55  4915.8  826.30
  4950.1  795.36  4957.0  763.70  4964.6  766.86  4967.7  763.70  4968.2  762.70
  5031.8  762.70  5032.3  763.70  5047.6  775.82  5058.9  778.10  5192.3  784.99
  5233.0  789.54  5252.4  795.53  5292.6  813.61  5311.9  820.69  5360.4  835.79
#Mann=3,-1,0
  4643.4    0.15       0  4967.7    0.05       0  5032.3    0.15       0
Bank Sta=4967.7,5032.3
XS Rating Curve= 0
Exp/Cntr=0.3,0.1

Type RM Length L Ch R = 1,63000,500,500,500
BEGIN DESCRIPTION:
Chauga River 126.0
END DESCRIPTION:
XS GIS Cut Line= 3
      1348315.45      1050822.37      1347999.90      1050945.70
      1347626.90      1051110.54
#Sta/Elev= 30
  4661.2  858.53  4715.8  849.99  4734.3  844.52  4768.9  838.37  4842.3  829.07
  4859.4  828.74  4885.9  821.78  4891.8  822.56  4898.7  817.58  4937.2  802.79
  4939.0  804.42  4954.1  786.36  4965.6  775.45  4967.7  762.20  4968.2  761.20
  5032.3  762.20  5040.6  770.03  5047.7  773.99  5047.9  772.43  5049.2  774.16
  5123.4  782.23  5172.0  781.74  5210.6  786.14  5212.1  783.86  5214.4  786.29
  5229.7  790.96  5263.0  806.86  5289.7  816.84  5359.2  836.80  5407.8  847.48
#Mann=3,-1,0
  4661.2    0.15       0  4967.7    0.05       0  5032.3    0.15       0
Bank Sta=4967.7,5032.3
XS Rating Curve= 0
Exp/Cntr=0.3,0.1

Type RM Length L Ch R = 1,62500,354,354,354
BEGIN DESCRIPTION:
Chauga River 125.0
END DESCRIPTION:
XS GIS Cut Line= 3
      1348221.08      1050458.19      1347788.86      1050498.53
      1347356.58      1050567.85
#Sta/Elev= 30
  4565.9  851.08  4646.3  832.44  4711.3  812.20  4740.4  801.41  4775.8  792.55
  4800.6  787.73  4856.8  780.99  4863.2  778.83  4863.8  777.10  4864.7  779.23
  4867.4  779.80  4886.1  771.11  4940.8  770.38  4951.6  767.01  4951.7  762.72
  4953.1  765.34  4967.7  760.54  4968.2  759.54  5032.3  760.54  5048.2  771.20
  5076.8  777.28  5088.4  774.69  5129.8  776.78  5131.3  774.85  5150.6  782.62
  5226.6  820.59  5262.0  831.67  5308.8  836.89  5384.6  841.79  5437.8  847.16
#Mann=3,-1,0
  4565.9    0.15       0  4967.7    0.05       0  5032.3    0.15       0
Bank Sta=4967.7,5032.3
XS Rating Curve= 0
Exp/Cntr=0.3,0.1

Type RM Length L Ch R = 1,62146,403,403,403
BEGIN DESCRIPTION:
Chauga River 124.0
END DESCRIPTION:
XS GIS Cut Line= 3
      1348157.35      1050363.05      1347712.22      1050170.23
      1347377.03      1050077.44
#Sta/Elev= 30
  4514.9  832.80  4635.2  791.23  4663.8  783.33  4667.3  786.84  4670.2  781.96
  4820.2  774.29  4829.9  768.74  4843.8  767.54  4961.3  772.97  4963.9  770.61
  4967.6  757.43  4968.1  756.43  5032.4  757.43  5050.8  766.48  5056.9  773.55
  5057.5  777.00  5058.0  773.30  5059.2  777.18  5060.6  773.39  5061.6  785.95
  5073.4  798.96  5092.6  805.01  5099.4  813.03  5106.4  813.46  5151.5  841.21
  5178.6  853.23  5226.8  864.26  5247.1  880.67  5251.2  870.99  5347.8  885.98
#Mann=3,-1,0
  4514.9    0.15       0  4967.6    0.05       0  5032.4    0.15       0
Bank Sta=4967.6,5032.4
XS Rating Curve= 0
Exp/Cntr=0.3,0.1

Type RM Length L Ch R = 1,61743,500,500,500
BEGIN DESCRIPTION:
Chauga River 123.0
END DESCRIPTION:
XS GIS Cut Line= 3
      1348310.38      1050312.56      1348033.85      1049995.11
      1347756.99      1049761.72
#Sta/Elev= 30
  4579.0  851.37  4625.6  847.54  4635.3  843.65  4641.2  846.36  4674.4  835.22
  4702.0  832.03  4755.9  812.67  4795.0  789.72  4797.5  793.90  4799.2  788.91
  4806.6  786.04  4860.3  778.03  4933.2  774.91  4945.2  772.12  4952.7  773.86
  4960.9  757.43  4967.6  757.43  4968.1  756.43  5032.4  757.43  5037.5  757.51
  5044.9  765.25  5060.4  770.83  5063.4  774.19  5126.8  785.76  5170.8  797.82
  5257.7  833.98  5324.4  855.44  5328.2  858.59  5332.0  856.55  5362.1  860.71
#Mann=3,-1,0
  4579.0    0.15       0  4967.6    0.05       0  5032.4    0.15       0
Bank Sta=4967.6,5032.4
XS Rating Curve= 0
Exp/Cntr=0.3,0.1

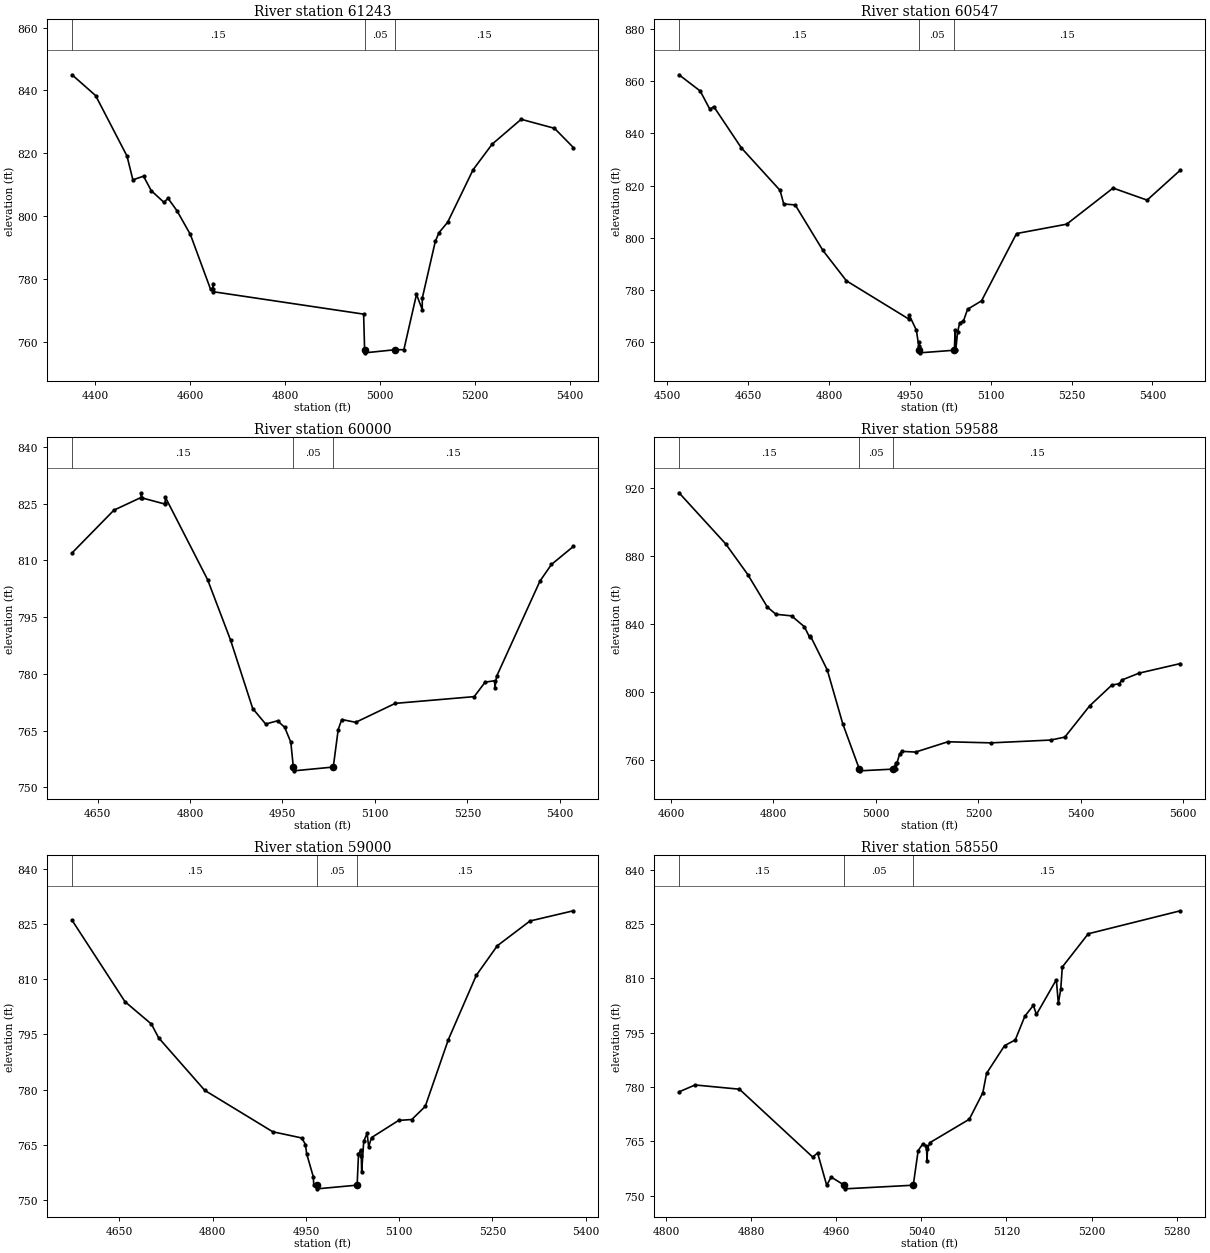
Type RM Length L Ch R = 1,61243,696,696,696
BEGIN DESCRIPTION:
Chauga River 122.0
END DESCRIPTION:
XS GIS Cut Line= 3
      1348366.49      1050316.92      1348385.07      1049668.39
      1348374.14      1049261.13
#Sta/Elev= 30
  4351.2  845.00  4400.9  838.37  4466.9  819.14  4479.4  811.53  4501.8  812.70
  4518.0  808.10  4544.9  804.35  4553.3  805.67  4572.1  801.73  4600.5  794.13
  4643.0  776.69  4647.9  776.64  4648.0  778.51  4648.5  775.90  4965.5  768.76
  4967.6  757.43  4968.1  756.43  5032.4  757.43  5050.3  757.43  5076.9  775.04
  5089.0  770.22  5089.1  773.85  5116.5  791.91  5124.2  794.70  5142.4  797.99
  5196.2  814.77  5236.3  822.90  5297.4  830.82  5367.6  827.95  5407.4  821.82
#Mann=3,-1,0
  4351.2    0.15       0  4967.6    0.05       0  5032.4    0.15       0
Bank Sta=4967.6,5032.4
XS Rating Curve= 0
Exp/Cntr=0.3,0.1

Type RM Length L Ch R = 1,60547,547,547,547
BEGIN DESCRIPTION:
Chauga River 121.0
END DESCRIPTION:
XS GIS Cut Line= 3
      1348348.60      1050471.72      1348761.44      1050229.60
      1349144.30      1049989.72
#Sta/Elev= 30
  4521.4  862.38  4560.7  856.17  4578.7  849.15  4585.9  850.20  4637.1  834.41
  4708.9  818.16  4715.7  812.95  4737.0  812.59  4788.5  795.16  4832.1  783.55
  4947.3  768.99  4948.3  770.57  4961.9  764.66  4966.4  758.45  4967.1  759.97
  4967.6  757.00  4968.1  756.00  5032.4  757.00  5033.8  764.64  5035.1  757.21
  5038.3  763.81  5042.2  767.47  5049.3  768.20  5056.9  772.67  5082.8  775.89
  5147.8  801.64  5240.8  805.22  5326.9  819.04  5390.1  814.43  5451.8  825.90
#Mann=3,-1,0
  4521.4    0.15       0  4967.6    0.05       0  5032.4    0.15       0
Bank Sta=4967.6,5032.4
XS Rating Curve= 0
Exp/Cntr=0.3,0.1

Type RM Length L Ch R = 1,60000,412,412,412
BEGIN DESCRIPTION:
Chauga River 120.0
END DESCRIPTION:
XS GIS Cut Line= 3
      1348664.91      1050907.26      1349007.47      1050717.92
      1349358.54      1050483.94
#Sta/Elev= 30
  4608.6  811.99  4676.5  823.29  4720.5  826.64  4720.8  827.89  4722.4  826.52
  4758.7  824.93  4759.7  825.14  4759.9  826.73  4828.4  804.96  4865.7  788.97
  4901.7  770.84  4922.7  766.75  4942.0  767.60  4953.6  765.87  4963.5  761.94
  4967.6  755.37  4968.1  754.37  5032.4  755.37  5040.4  765.30  5046.2  767.94
  5068.8  767.20  5133.0  772.21  5261.0  773.99  5278.8  777.82  5294.1  778.19
  5294.7  776.35  5297.3  779.33  5367.7  804.54  5386.3  808.93  5421.9  813.70
#Mann=3,-1,0
  4608.6    0.15       0  4967.6    0.05       0  5032.4    0.15       0
Bank Sta=4967.6,5032.4
XS Rating Curve= 0
Exp/Cntr=0.3,0.1

Type RM Length L Ch R = 1,59588,588,588,588
BEGIN DESCRIPTION:
Chauga River 119.0
END DESCRIPTION:
XS GIS Cut Line= 3
      1349223.37      1051394.40      1349274.24      1051013.38
      1349389.13      1050430.40
#Sta/Elev= 30
  4615.6  917.34  4706.6  887.30  4749.8  869.24  4788.0  850.09  4804.8  845.86
  4835.3  844.91  4860.3  838.52  4870.3  832.45  4871.9  833.18  4905.0  813.09
  4935.3  781.35  4967.6  754.74  4968.1  753.74  5032.4  754.74  5039.4  758.17
  5039.6  754.74  5040.8  758.16  5046.1  763.55  5050.4  765.21  5077.3  764.78
  5140.4  770.84  5224.4  770.20  5341.0  771.85  5368.7  773.58  5417.1  791.95
  5460.4  804.18  5475.2  805.02  5479.7  807.14  5513.6  811.22  5594.2  816.85
#Mann=3,-1,0
  4615.6    0.15       0  4967.6    0.05       0  5032.4    0.15       0
Bank Sta=4967.6,5032.4
XS Rating Curve= 0
Exp/Cntr=0.3,0.1

Type RM Length L Ch R = 1,59000,450,450,450
BEGIN DESCRIPTION:
Chauga River 118.0
END DESCRIPTION:
XS GIS Cut Line= 3
      1349940.48      1051121.48      1349781.81      1050726.13
      1349631.92      1050376.83
#Sta/Elev= 30
  4574.0  825.99  4659.1  803.90  4701.6  797.82  4713.3  794.07  4787.4  779.83
  4896.7  768.60  4943.4  766.91  4949.3  765.14  4951.2  762.65  4961.9  756.40
  4962.7  754.15  4967.6  754.11  4968.1  753.11  5032.4  754.11  5034.6  762.48
  5038.3  763.70  5039.1  761.91  5039.7  757.72  5043.0  766.01  5048.5  768.19
  5050.9  764.53  5055.6  767.02  5099.2  771.68  5120.3  771.92  5141.9  775.47
  5179.1  793.62  5224.0  811.04  5257.8  819.07  5310.4  825.79  5380.1  828.56
#Mann=3,-1,0
  4574.0    0.15       0  4967.6    0.05       0  5032.4    0.15       0
Bank Sta=4967.6,5032.4
XS Rating Curve= 0
Exp/Cntr=0.3,0.1

Type RM Length L Ch R = 1,58550,550,550,550
BEGIN DESCRIPTION:
Chauga River 117.0
END DESCRIPTION:
XS GIS Cut Line= 3
      1350230.22      1050636.45      1350148.90      1050467.17
      1349997.57      1050227.44
#Sta/Elev= 30
  4812.2  778.69  4827.3  780.59  4869.0  779.42  4937.8  760.71  4942.5  761.80
  4951.0  752.92  4955.3  755.15  4967.6  752.92  4968.1  751.92  5032.4  752.92
  5037.0  762.46  5041.3  764.31  5044.8  763.72  5045.4  759.47  5045.7  762.84
  5048.0  764.66  5085.1  771.13  5097.8  778.43  5101.3  783.78  5118.2  791.43
  5128.3  793.02  5137.3  799.56  5145.3  802.57  5148.2  800.05  5166.9  809.64
  5168.8  803.12  5171.1  807.07  5172.5  813.14  5196.9  822.32  5283.5  828.67
#Mann=3,-1,0
  4812.2    0.15       0  4967.6    0.05       0  5032.4    0.15       0
Bank Sta=4967.6,5032.4
XS Rating Curve= 0
Exp/Cntr=0.3,0.1

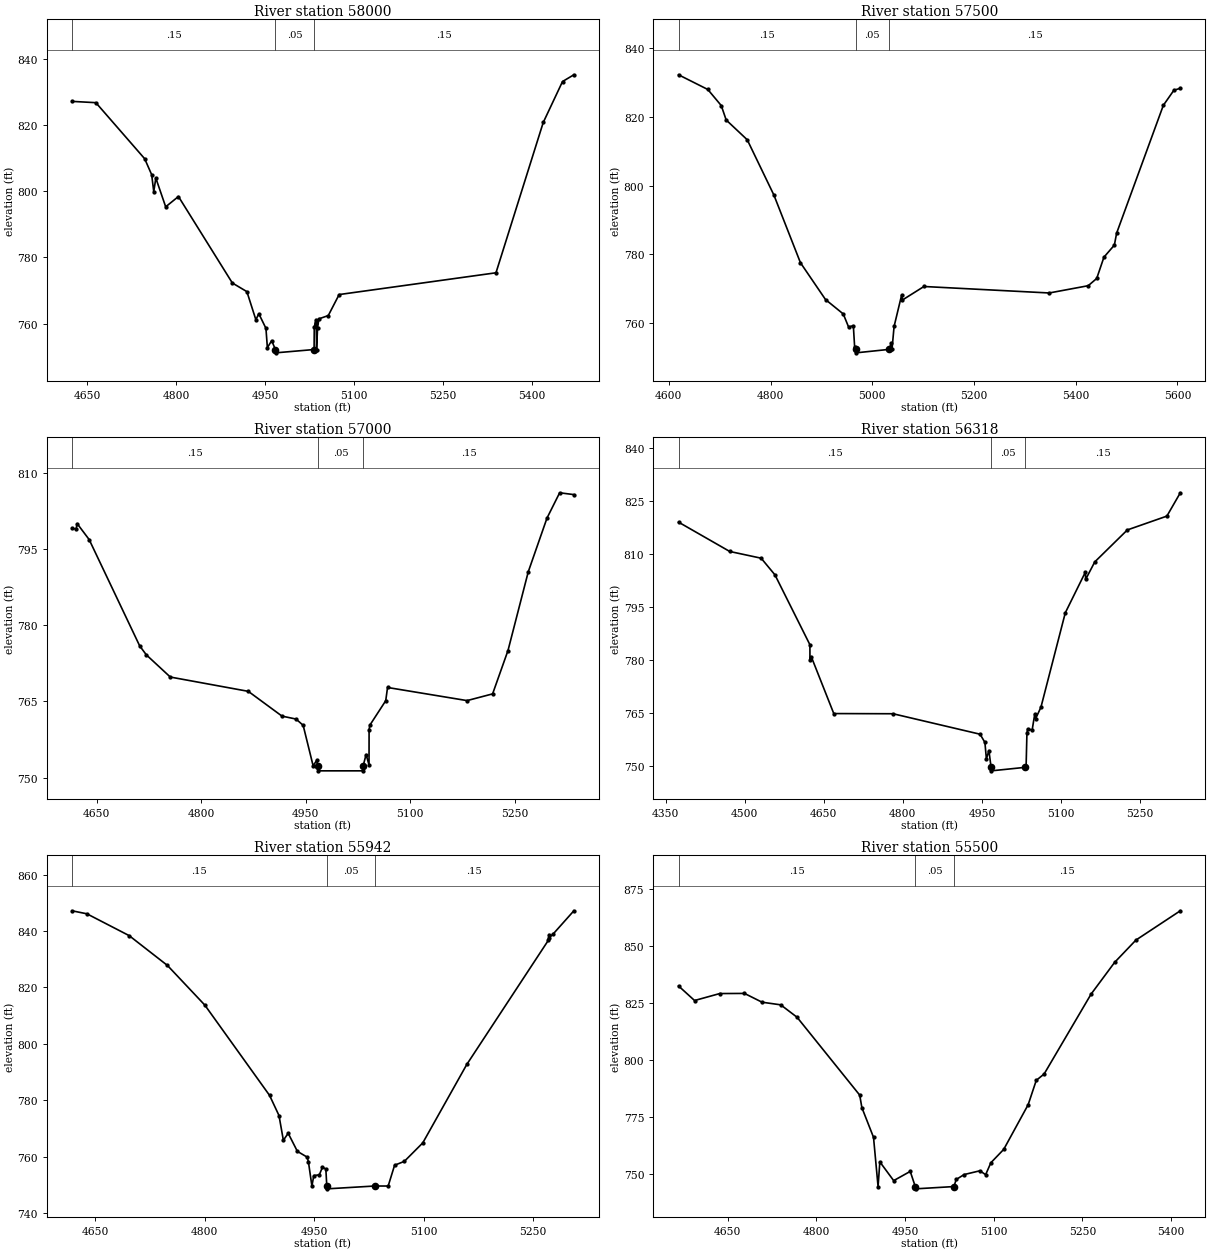
Type RM Length L Ch R = 1,58000,500,500,500
BEGIN DESCRIPTION:
Chauga River 116.0
END DESCRIPTION:
XS GIS Cut Line= 3
      1350858.59      1050351.85      1350569.35      1050113.03
      1350170.04      1049864.76
#Sta/Elev= 30
  4624.9  827.10  4665.0  826.71  4747.2  809.79  4759.0  804.98  4762.5  799.86
  4766.0  803.95  4782.6  795.28  4804.1  798.39  4894.9  772.29  4919.4  769.68
  4934.5  761.21  4939.5  763.01  4951.5  758.60  4953.9  752.78  4961.2  754.89
  4967.4  752.21  4967.9  751.21  5032.6  752.21  5032.9  758.94  5035.7  761.24
  5036.2  760.12  5036.7  752.21  5038.5  758.80  5040.7  761.47  5056.5  762.46
  5074.8  768.80  5339.0  775.37  5418.6  820.73  5451.1  833.09  5470.2  835.13
#Mann=3,-1,0
  4624.9    0.15       0  4967.4    0.05       0  5032.6    0.15       0
Bank Sta=4967.4,5032.6
XS Rating Curve= 0
Exp/Cntr=0.3,0.1

Type RM Length L Ch R = 1,57500,500,500,500
BEGIN DESCRIPTION:
Chauga River 115.0
END DESCRIPTION:
XS GIS Cut Line= 3
      1351156.96      1050010.63      1350894.53      1049734.42
      1350379.14      1049416.42
#Sta/Elev= 30
  4619.0  832.31  4676.6  828.02  4703.0  823.33  4712.7  819.12  4754.1  813.35
  4806.5  797.23  4858.7  777.49  4908.0  766.75  4942.9  762.55  4953.3  758.76
  4962.7  759.12  4965.3  752.78  4967.4  752.21  4967.9  751.21  5032.6  752.21
  5037.7  754.18  5038.7  752.21  5042.8  758.90  5057.7  768.09  5059.2  766.62
  5101.5  770.56  5347.8  768.67  5424.5  770.79  5441.2  772.90  5455.4  779.11
  5475.9  782.63  5480.4  786.14  5572.2  823.40  5592.9  827.79  5605.6  828.38
#Mann=3,-1,0
  4619.0    0.15       0  4967.4    0.05       0  5032.6    0.15       0
Bank Sta=4967.4,5032.6
XS Rating Curve= 0
Exp/Cntr=0.3,0.1

Type RM Length L Ch R = 1,57000,682,682,682
BEGIN DESCRIPTION:
Chauga River 114.0
END DESCRIPTION:
XS GIS Cut Line= 3
      1351466.23      1049673.80      1351233.26      1049366.66
      1351014.17      1049112.97
#Sta/Elev= 30
  4614.5  799.04  4620.3  798.90  4621.8  799.96  4639.0  796.83  4711.6  775.92
  4721.2  774.15  4755.6  769.79  4867.6  766.98  4916.0  762.11  4936.2  761.53
  4946.4  760.30  4960.7  752.35  4965.9  753.41  4967.4  752.35  4967.9  751.35
  5032.1  751.35  5032.6  752.35  5036.8  754.55  5041.0  752.51  5041.1  759.39
  5042.1  760.31  5065.0  765.14  5067.6  767.74  5181.8  765.16  5218.5  766.48
  5240.6  775.01  5269.7  790.48  5296.6  801.04  5314.8  806.02  5335.2  805.66
#Mann=3,-1,0
  4614.5    0.15       0  4967.4    0.05       0  5032.6    0.15       0
Bank Sta=4967.4,5032.6
XS Rating Curve= 0
Exp/Cntr=0.3,0.1

Type RM Length L Ch R = 1,56318,376,376,376
BEGIN DESCRIPTION:
Chauga River 113.0
END DESCRIPTION:
XS GIS Cut Line= 3
      1352098.52      1049446.02      1351751.18      1048925.83
      1351519.03      1048696.38
#Sta/Elev= 30
  4374.5  819.02  4471.6  810.71  4531.2  808.80  4557.4  804.08  4623.7  784.28
  4623.8  780.00  4626.3  780.89  4669.0  764.77  4781.4  764.72  4946.5  758.92
  4955.7  756.59  4958.5  751.91  4963.3  754.29  4967.4  749.54  4967.9  748.54
  5032.6  749.54  5033.8  749.54  5035.4  759.15  5036.8  760.47  5045.3  760.08
  5050.3  764.69  5051.8  763.29  5062.0  766.58  5108.2  793.33  5146.5  804.92
  5146.7  802.77  5164.1  807.75  5225.9  816.81  5300.9  820.73  5326.4  827.34
#Mann=3,-1,0
  4374.5    0.15       0  4967.4    0.05       0  5032.6    0.15       0
Bank Sta=4967.4,5032.6
XS Rating Curve= 0
Exp/Cntr=0.3,0.1

Type RM Length L Ch R = 1,55942,442,442,442
BEGIN DESCRIPTION:
Chauga River 112.0
END DESCRIPTION:
XS GIS Cut Line= 3
      1352386.68      1048708.98      1352008.11      1048660.19
      1351703.69      1048631.19
#Sta/Elev= 30
  4618.3  847.16  4638.6  846.10  4696.5  838.36  4749.0  827.77  4800.2  813.71
  4888.9  781.68  4901.8  774.55  4907.8  765.76  4914.4  768.25  4927.0  761.84
  4940.3  759.80  4942.1  758.17  4946.9  749.54  4949.5  753.24  4957.1  753.53
  4961.3  756.18  4966.0  755.58  4967.3  749.54  4967.8  748.54  5032.7  749.54
  5051.4  749.54  5060.2  756.92  5073.5  758.28  5098.8  764.84  5159.1  792.66
  5270.9  836.72  5271.7  838.74  5272.0  837.62  5277.6  838.98  5305.8  847.17
#Mann=3,-1,0
  4618.3    0.15       0  4967.3    0.05       0  5032.7    0.15       0
Bank Sta=4967.3,5032.7
XS Rating Curve= 0
Exp/Cntr=0.3,0.1

Type RM Length L Ch R = 1,55500,500,500,500
BEGIN DESCRIPTION:
Chauga River 111.0
END DESCRIPTION:
XS GIS Cut Line= 3
      1352514.67      1048253.76      1352082.61      1048225.38
      1351668.03      1048197.66
#Sta/Elev= 30
  4567.0  832.52  4594.1  826.12  4636.7  829.18  4678.5  829.24  4708.2  825.38
  4739.8  824.22  4767.4  818.77  4873.4  784.51  4877.0  779.03  4896.7  765.97
  4904.4  744.31  4907.4  755.16  4930.8  746.92  4958.8  750.98  4967.3  744.31
  4967.8  743.31  5032.7  744.31  5036.5  747.42  5049.9  749.59  5076.6  751.25
  5086.3  749.53  5095.1  754.77  5116.9  760.67  5158.2  780.31  5171.9  791.01
  5185.2  793.81  5264.6  828.94  5304.4  842.89  5340.4  852.69  5415.5  865.58
#Mann=3,-1,0
  4567.0    0.15       0  4967.3    0.05       0  5032.7    0.15       0
Bank Sta=4967.3,5032.7
XS Rating Curve= 0
Exp/Cntr=0.3,0.1

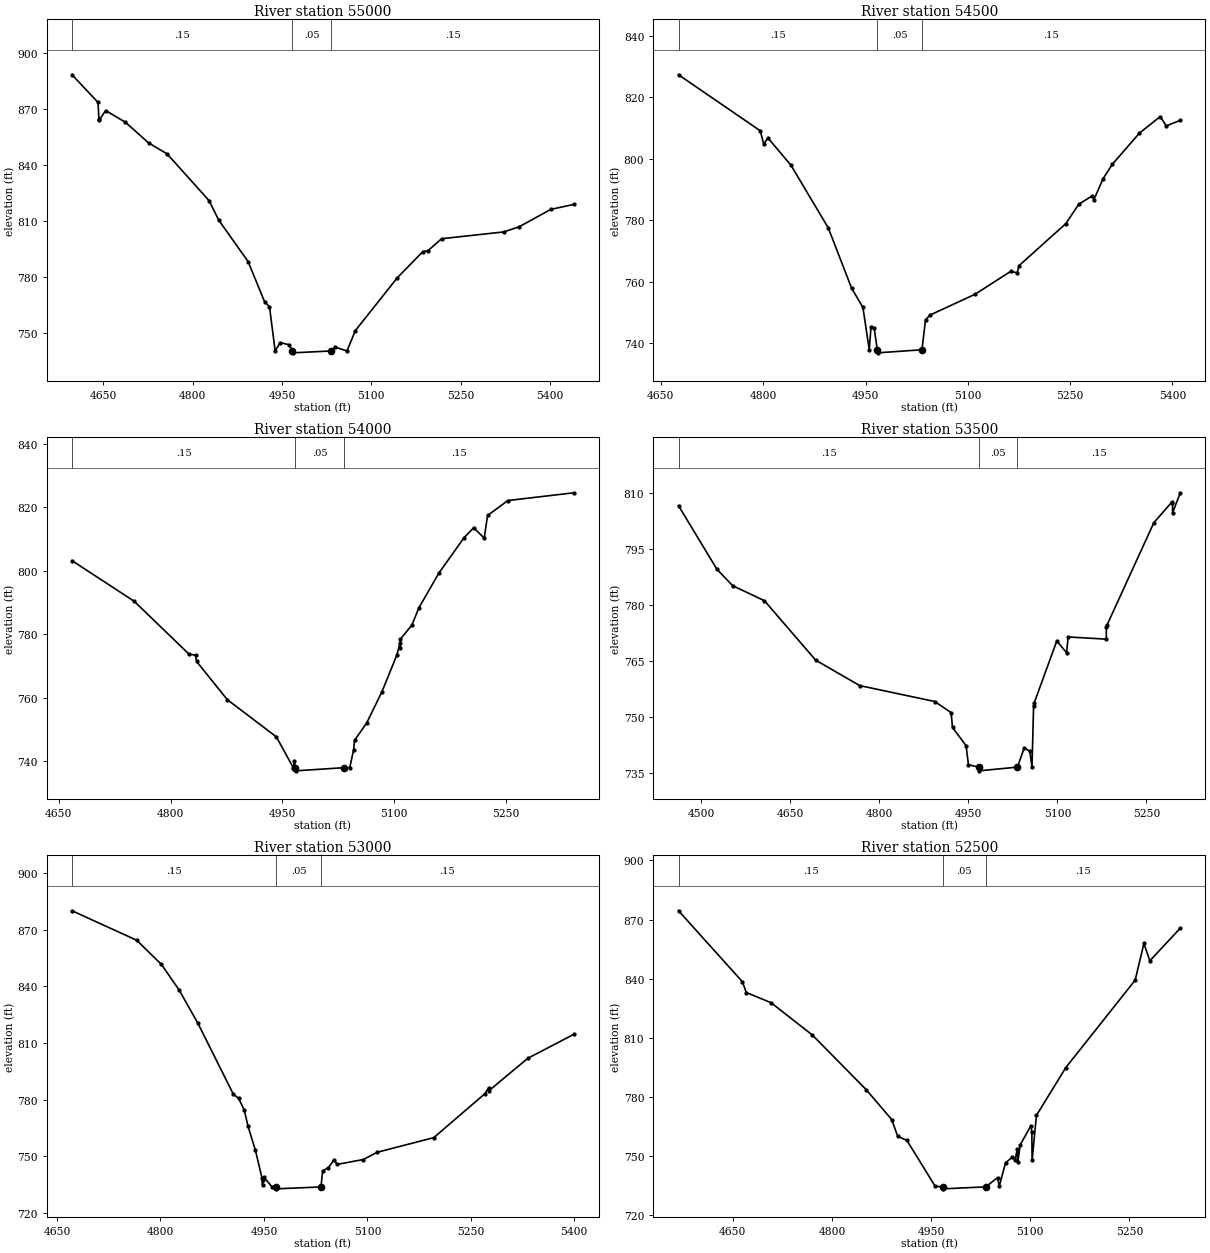
Type RM Length L Ch R = 1,55000,500,500,500
BEGIN DESCRIPTION:
Chauga River 110.0
END DESCRIPTION:
XS GIS Cut Line= 3
      1352489.21      1047760.30      1352087.81      1047730.66
      1351647.59      1047722.04
#Sta/Elev= 30
  4597.5  888.09  4641.1  873.30  4642.6  864.39  4643.1  863.85  4653.9  868.97
  4687.1  862.69  4726.1  851.62  4757.2  845.74  4827.9  820.64  4843.6  810.43
  4893.2  788.13  4920.8  766.69  4929.1  763.97  4938.6  740.31  4947.2  744.78
  4962.4  743.60  4967.3  740.31  4967.8  739.31  5032.7  740.31  5039.1  742.42
  5059.2  740.31  5073.3  751.21  5143.8  779.50  5186.5  793.42  5195.5  794.02
  5218.1  800.37  5322.8  804.02  5348.8  806.81  5401.3  816.03  5440.3  818.73
#Mann=3,-1,0
  4597.5    0.15       0  4967.3    0.05       0  5032.7    0.15       0
Bank Sta=4967.3,5032.7
XS Rating Curve= 0
Exp/Cntr=0.3,0.1

Type RM Length L Ch R = 1,54500,500,500,500
BEGIN DESCRIPTION:
Chauga River 109.0
END DESCRIPTION:
XS GIS Cut Line= 3
      1352445.87      1047256.63      1352122.67      1047232.57
      1351713.90      1047185.21
#Sta/Elev= 30
  4675.9  827.29  4795.8  809.08  4800.8  804.73  4806.9  806.78  4840.7  797.89
  4895.3  777.58  4929.6  757.95  4946.2  751.67  4955.5  737.93  4958.0  745.22
  4962.6  745.09  4967.3  737.93  4967.8  736.93  5032.7  737.93  5038.0  747.70
  5045.0  749.25  5110.6  755.97  5162.7  763.39  5172.4  762.95  5175.1  765.27
  5243.6  778.91  5262.8  785.26  5282.2  787.92  5284.8  786.70  5298.4  793.58
  5312.0  798.25  5351.5  808.32  5382.1  813.71  5390.8  810.67  5411.5  812.49
#Mann=3,-1,0
  4675.9    0.15       0  4967.3    0.05       0  5032.7    0.15       0
Bank Sta=4967.3,5032.7
XS Rating Curve= 0
Exp/Cntr=0.3,0.1

Type RM Length L Ch R = 1,54000,500,500,500
BEGIN DESCRIPTION:
Chauga River 108.0
END DESCRIPTION:
XS GIS Cut Line= 3
      1352458.63      1046988.88      1352223.31      1046754.68
      1351989.36      1046506.87
#Sta/Elev= 30
  4668.0  803.11  4751.3  790.33  4824.9  773.65  4833.5  773.38  4835.0  771.37
  4876.0  759.38  4941.9  747.63  4964.6  737.93  4966.2  739.96  4967.3  737.93
  4967.8  736.93  5032.7  737.93  5040.3  737.93  5045.5  743.54  5046.7  746.52
  5063.0  752.00  5083.6  761.90  5103.7  773.54  5107.7  777.28  5108.2  775.68
  5108.3  778.41  5123.7  782.86  5132.9  788.21  5159.9  799.25  5193.7  810.40
  5206.5  813.49  5220.6  810.23  5225.1  817.35  5252.4  822.06  5340.8  824.50
#Mann=3,-1,0
  4668.0    0.15       0  4967.3    0.05       0  5032.7    0.15       0
Bank Sta=4967.3,5032.7
XS Rating Curve= 0
Exp/Cntr=0.3,0.1

Type RM Length L Ch R = 1,53500,500,500,500
BEGIN DESCRIPTION:
Chauga River 107.0
END DESCRIPTION:
XS GIS Cut Line= 3
      1352530.00      1047014.35      1352624.65      1046484.43
      1352642.21      1046177.84
#Sta/Elev= 30
  4461.7  806.56  4526.3  789.58  4552.7  785.18  4606.5  781.13  4692.7  765.23
  4766.9  758.42  4893.3  754.16  4920.9  751.18  4923.3  747.21  4946.2  742.33
  4950.1  737.24  4967.3  736.60  4967.8  735.60  5032.7  736.60  5044.1  741.76
  5053.5  740.85  5057.2  736.60  5059.9  753.01  5060.6  753.65  5098.9  770.34
  5115.5  767.23  5118.1  771.44  5182.3  770.85  5182.6  774.22  5183.4  774.56
  5262.6  802.05  5293.2  807.59  5293.9  807.38  5294.1  804.70  5307.1  810.03
#Mann=3,-1,0
  4461.7    0.15       0  4967.3    0.05       0  5032.7    0.15       0
Bank Sta=4967.3,5032.7
XS Rating Curve= 0
Exp/Cntr=0.3,0.1

Type RM Length L Ch R = 1,53000,500,500,500
BEGIN DESCRIPTION:
Chauga River 106.0
END DESCRIPTION:
XS GIS Cut Line= 3
      1353340.96      1046331.14      1353024.54      1046243.99
      1352639.65      1046137.32
#Sta/Elev= 30
  4671.8  879.96  4765.6  864.36  4801.4  851.54  4827.1  838.00  4854.3  820.40
  4905.8  782.77  4913.2  780.77  4921.5  774.49  4926.9  765.97  4937.7  753.14
  4947.3  738.34  4948.0  734.78  4948.4  737.49  4950.1  738.94  4961.5  733.96
  4967.3  733.81  4967.8  732.81  5032.7  733.81  5035.2  742.34  5043.3  743.94
  5051.9  748.25  5055.8  745.72  5094.2  748.33  5114.1  752.15  5196.3  759.90
  5270.4  783.15  5275.9  786.32  5276.3  784.76  5332.5  801.86  5399.4  814.59
#Mann=3,-1,0
  4671.8    0.15       0  4967.3    0.05       0  5032.7    0.15       0
Bank Sta=4967.3,5032.7
XS Rating Curve= 0
Exp/Cntr=0.3,0.1

Type RM Length L Ch R = 1,52500,593,593,593
BEGIN DESCRIPTION:
Chauga River 105.0
END DESCRIPTION:
XS GIS Cut Line= 3
      1353453.16      1046065.89      1353147.00      1045761.11
      1352884.51      1045566.10
#Sta/Elev= 30
  4568.0  874.48  4664.5  838.54  4670.5  833.04  4708.0  827.85  4770.3  811.52
  4851.7  783.84  4890.4  768.64  4899.5  760.15  4913.5  758.01  4956.2  734.78
  4967.3  734.49  4967.8  733.49  5032.7  734.49  5050.5  739.17  5053.1  734.78
  5062.6  746.72  5073.0  749.58  5077.1  748.17  5080.4  753.69  5081.2  747.08
  5084.8  755.77  5101.0  765.51  5102.4  762.23  5102.8  747.94  5109.4  770.76
  5153.7  794.94  5258.7  839.31  5271.9  857.91  5280.9  849.12  5327.0  865.67
#Mann=3,-1,0
  4568.0    0.15       0  4967.3    0.05       0  5032.7    0.15       0
Bank Sta=4967.3,5032.7
XS Rating Curve= 0
Exp/Cntr=0.3,0.1

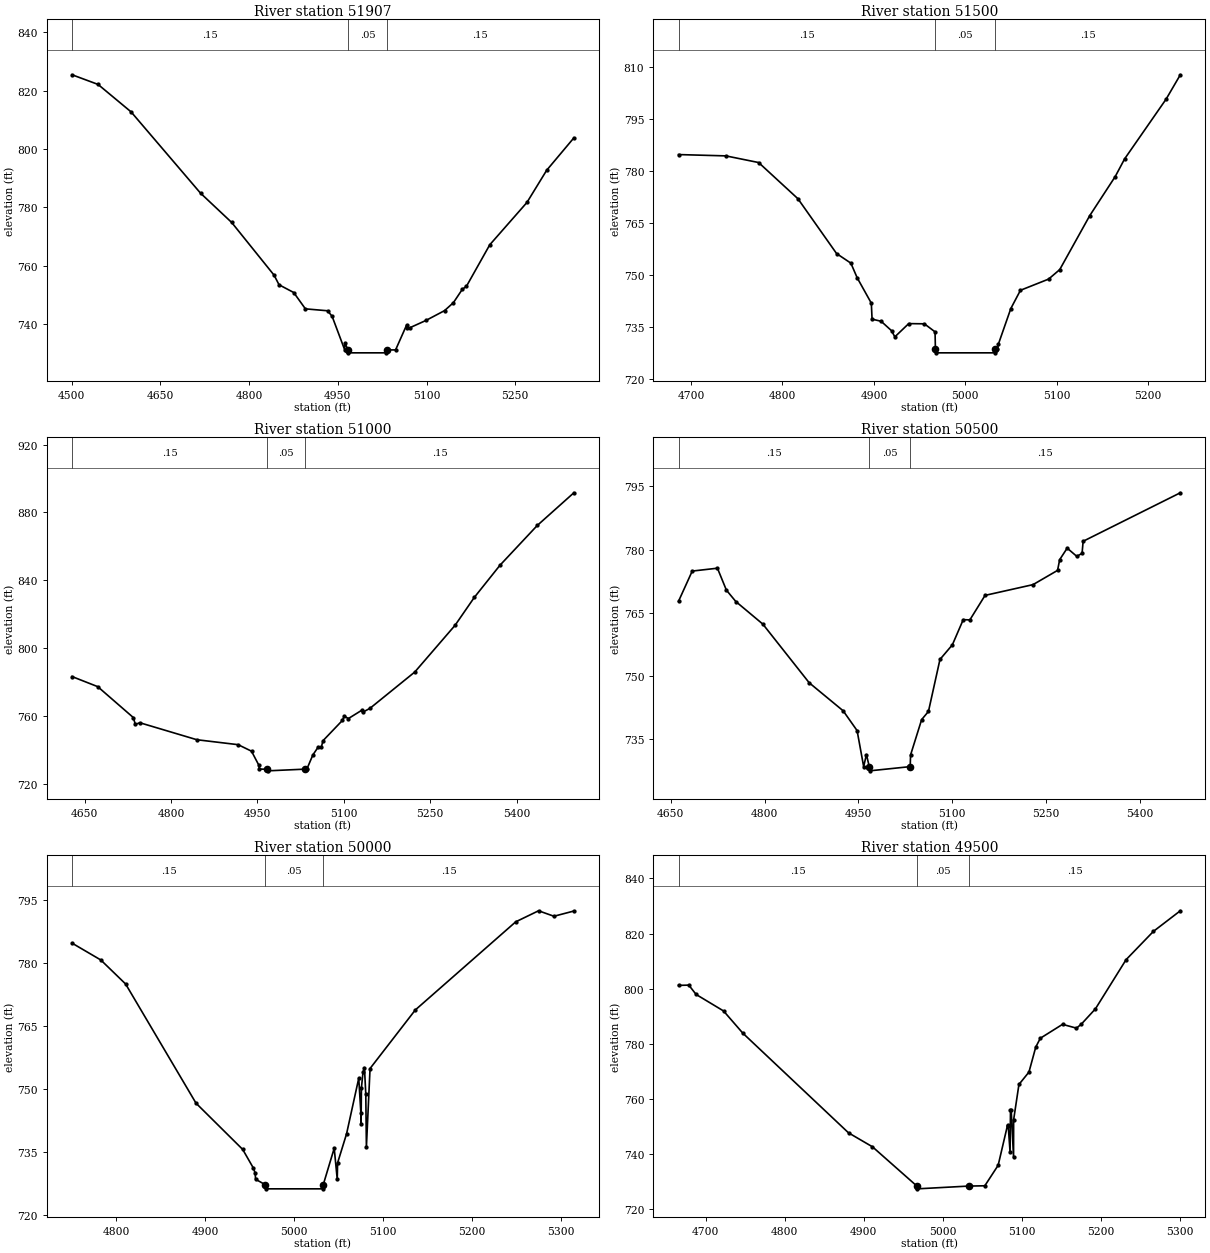
Type RM Length L Ch R = 1,51907,407,407,407
BEGIN DESCRIPTION:
Chauga River 104.0
END DESCRIPTION:
XS GIS Cut Line= 4
      1354070.35      1045838.96      1353682.21      1045524.57
      1353570.49      1045446.21      1353358.83      1045425.81
#Sta/Elev= 30
  4500.5  825.42  4544.4  822.12  4600.3  812.71  4717.7  784.87  4770.4  774.83
  4842.2  756.75  4850.5  753.48  4875.3  750.83  4895.1  745.23  4932.7  744.57
  4940.3  742.66  4961.6  731.16  4961.8  733.57  4967.3  731.16  4967.8  730.16
  5032.2  730.16  5032.7  731.16  5047.6  731.16  5066.3  739.70  5067.6  738.62
  5071.2  738.71  5099.0  741.26  5130.4  744.62  5145.4  747.35  5160.4  751.90
  5167.5  752.98  5206.9  767.18  5269.8  781.69  5303.1  792.70  5349.1  803.80
#Mann=3,-1,0
  4500.5    0.15       0  4967.3    0.05       0  5032.7    0.15       0
Bank Sta=4967.3,5032.7
XS Rating Curve= 0
Exp/Cntr=0.3,0.1

Type RM Length L Ch R = 1,51500,500,500,500
BEGIN DESCRIPTION:
Chauga River 103.0
END DESCRIPTION:
XS GIS Cut Line= 3
      1353751.53      1045023.41      1353512.59      1045226.67
      1353328.25      1045372.74
#Sta/Elev= 30
  4686.3  784.75  4738.1  784.37  4773.9  782.45  4816.9  772.00  4859.2  756.16
  4874.8  753.40  4881.7  749.18  4897.2  741.84  4898.0  737.22  4907.9  736.62
  4919.3  733.89  4922.9  732.11  4938.1  735.94  4955.2  735.88  4966.9  733.56
  4967.3  728.50  4967.8  727.50  5032.2  727.50  5032.7  728.50  5035.1  728.50
  5036.3  730.10  5049.8  740.30  5060.3  745.56  5091.1  748.79  5103.3  751.54
  5136.1  767.11  5164.0  778.41  5174.3  783.52  5219.7  800.78  5235.2  807.79
#Mann=3,-1,0
  4686.3    0.15       0  4967.3    0.05       0  5032.7    0.15       0
Bank Sta=4967.3,5032.7
XS Rating Curve= 0
Exp/Cntr=0.3,0.1

Type RM Length L Ch R = 1,51000,500,500,500
BEGIN DESCRIPTION:
Chauga River 102.0
END DESCRIPTION:
XS GIS Cut Line= 3
      1353557.78      1044770.90      1353193.73      1044845.41
      1352726.37      1045020.83
#Sta/Elev= 30
  4628.4  783.14  4672.9  777.20  4734.8  758.92  4738.1  754.95  4746.1  755.88
  4845.0  745.86  4916.6  742.94  4939.8  739.10  4952.3  730.96  4953.4  728.50
  4967.3  728.50  4967.8  727.50  5032.7  728.50  5035.8  728.50  5046.3  736.90
  5055.2  741.38  5061.1  741.69  5063.9  745.30  5097.6  757.29  5100.7  759.81
  5107.9  758.36  5132.2  763.48  5133.5  762.23  5145.3  764.38  5223.2  785.85
  5293.0  813.38  5326.5  829.90  5371.0  848.86  5435.7  872.33  5499.2  891.63
#Mann=3,-1,0
  4628.4    0.15       0  4967.3    0.05       0  5032.7    0.15       0
Bank Sta=4967.3,5032.7
XS Rating Curve= 0
Exp/Cntr=0.3,0.1

Type RM Length L Ch R = 1,50500,500,500,500
BEGIN DESCRIPTION:
Chauga River 101.0
END DESCRIPTION:
XS GIS Cut Line= 3
      1353590.90      1044620.20      1353315.15      1044425.26
      1352922.77      1044176.48
#Sta/Elev= 30
  4662.3  767.75  4684.2  774.91  4724.5  775.59  4738.8  770.39  4753.9  767.68
  4797.1  762.32  4871.2  748.40  4925.5  741.75  4947.8  737.05  4958.3  728.50
  4962.7  731.36  4967.3  728.50  4967.8  727.50  5032.7  728.50  5033.3  731.27
  5051.0  739.66  5061.9  741.60  5080.3  753.94  5100.1  757.40  5117.5  763.38
  5128.1  763.32  5152.4  769.14  5229.1  771.69  5268.3  775.07  5271.7  777.62
  5283.7  780.35  5299.0  778.41  5307.5  779.11  5309.2  781.98  5464.6  793.49
#Mann=3,-1,0
  4662.3    0.15       0  4967.3    0.05       0  5032.7    0.15       0
Bank Sta=4967.3,5032.7
XS Rating Curve= 0
Exp/Cntr=0.3,0.1

Type RM Length L Ch R = 1,50000,500,500,500
BEGIN DESCRIPTION:
Chauga River 100.0
END DESCRIPTION:
XS GIS Cut Line= 3
      1353797.46      1044388.11      1353725.96      1044148.76
      1353672.51      1043838.83
#Sta/Elev= 30
  4750.2  784.65  4782.5  780.65  4810.4  774.94  4889.6  746.58  4942.1  735.58
  4953.9  731.22  4956.2  729.93  4956.5  728.50  4967.3  727.21  4967.8  726.21
  5032.2  726.21  5032.7  727.21  5045.0  735.86  5048.4  728.50  5048.8  732.38
  5058.9  739.30  5072.6  752.52  5075.0  744.14  5075.2  741.58  5075.6  750.23
  5077.4  754.00  5079.0  755.05  5080.5  748.79  5081.2  736.14  5085.3  754.83
  5136.2  768.76  5249.1  789.72  5274.8  792.35  5292.1  791.05  5314.5  792.29
#Mann=3,-1,0
  4750.2    0.15       0  4967.3    0.05       0  5032.7    0.15       0
Bank Sta=4967.3,5032.7
XS Rating Curve= 0
Exp/Cntr=0.3,0.1

Type RM Length L Ch R = 1,49500,500,500,500
BEGIN DESCRIPTION:
Chauga River 99.0
END DESCRIPTION:
XS GIS Cut Line= 3
      1353981.06      1044404.98      1354192.85      1044145.94
      1354389.11      1043917.86
#Sta/Elev= 30
  4665.4  801.20  4678.4  801.29  4687.7  797.90  4722.4  791.92  4746.8  783.87
  4880.7  747.70  4911.0  742.64  4967.3  728.39  4967.8  727.39  5032.7  728.39
  5053.3  728.50  5070.2  735.94  5082.2  750.65  5083.0  750.03  5085.3  740.61
  5085.8  755.88  5086.7  755.95  5089.7  738.78  5089.8  752.45  5096.5  765.25
  5109.2  769.75  5117.8  778.81  5123.6  782.02  5151.7  787.06  5169.4  785.68
  5175.7  787.19  5193.4  792.69  5232.2  810.52  5266.8  820.78  5300.9  828.26
#Mann=3,-1,0
  4665.4    0.15       0  4967.3    0.05       0  5032.7    0.15       0
Bank Sta=4967.3,5032.7
XS Rating Curve= 0
Exp/Cntr=0.3,0.1