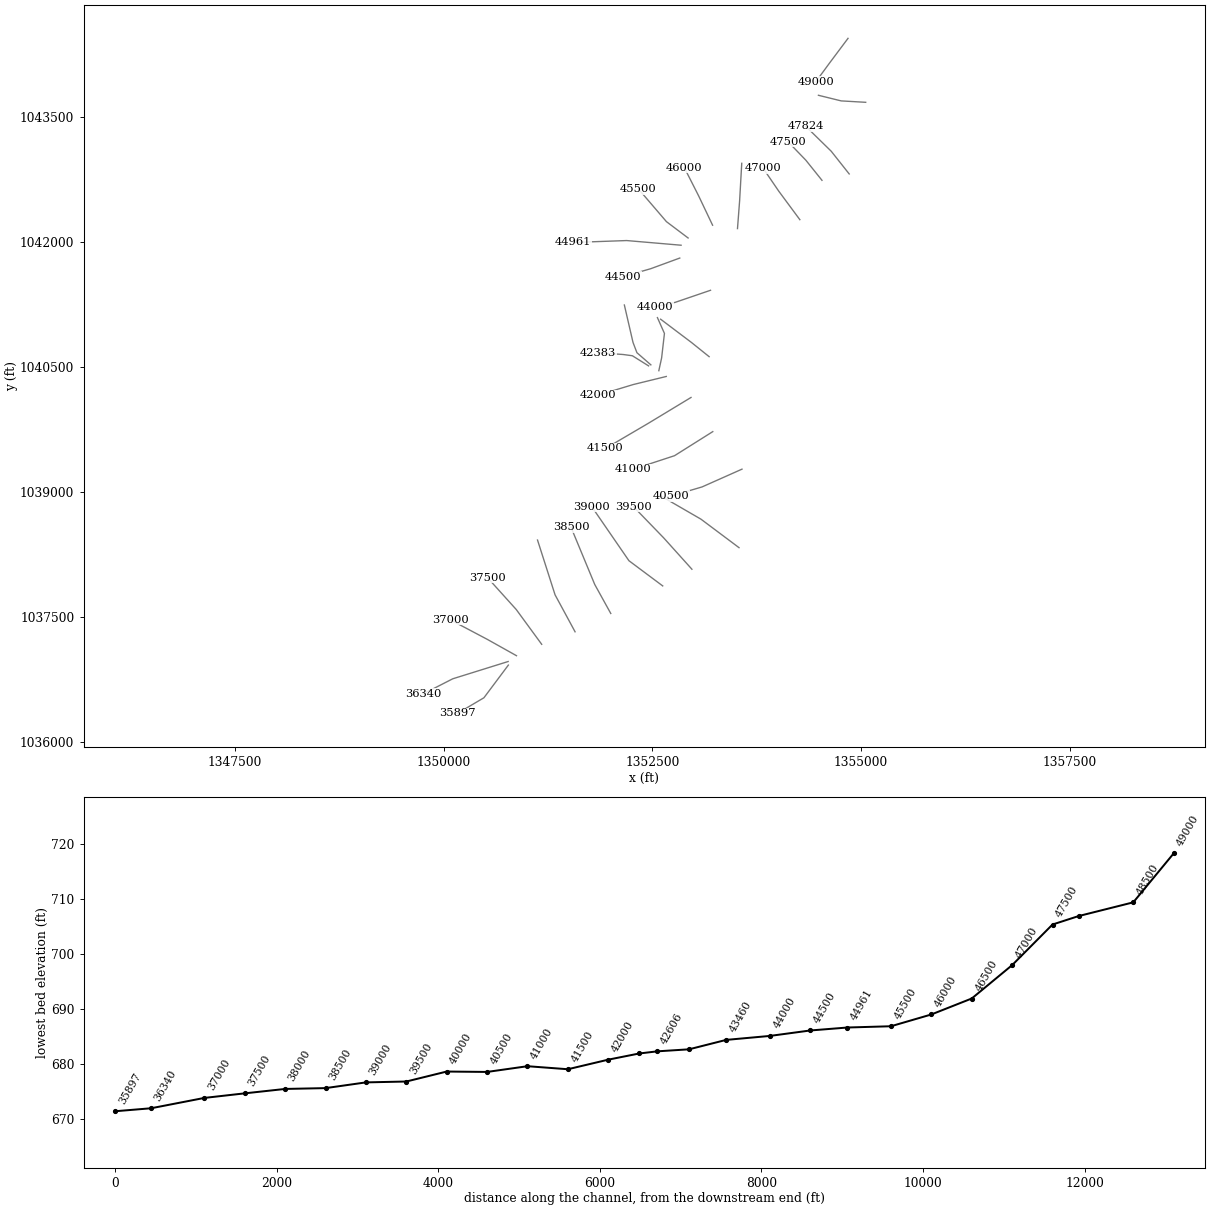
HEC-RAS study Chauga River.prj: Chauga River Limited Detail Study

--- Chauga River.g01 (geometry) --- (continued)

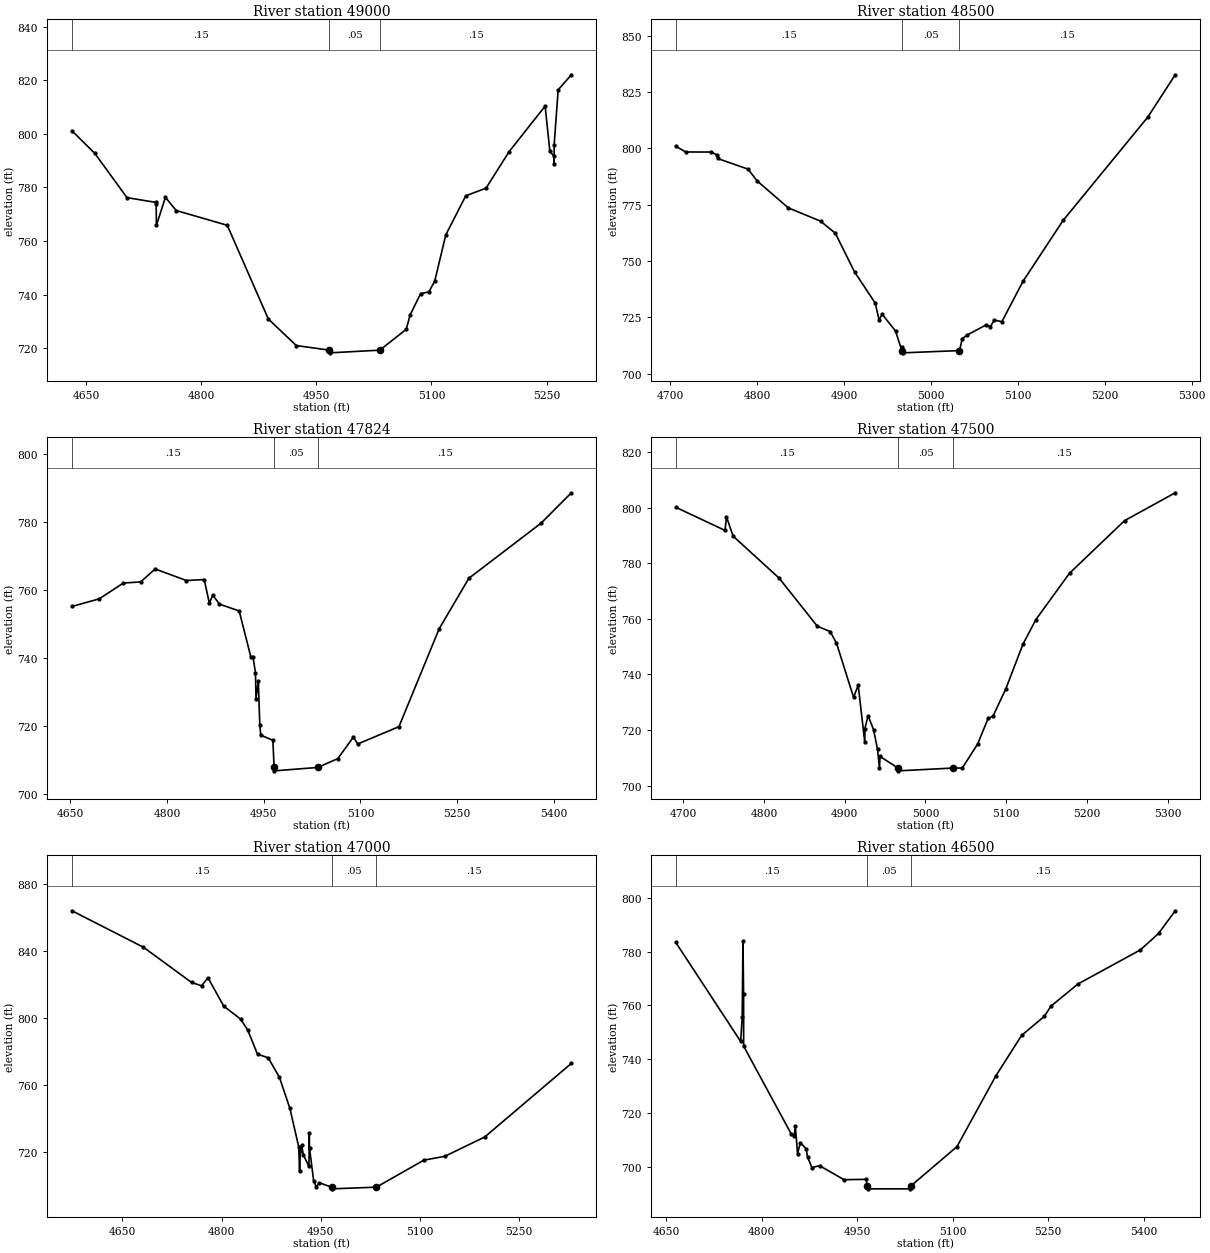
Type RM Length L Ch R = 1,49000,500,500,500
BEGIN DESCRIPTION:
Chauga River 98.0
END DESCRIPTION:
XS GIS Cut Line= 3
      1354845.58      1044440.62      1354624.96      1044145.59
      1354457.97      1043917.85
#Sta/Elev= 30
  4631.6  801.17  4661.4  792.74  4703.3  776.20  4741.0  774.42  4741.4  773.80
  4741.6  765.79  4753.4  776.31  4767.4  771.39  4834.0  765.86  4887.5  730.85
  4923.9  720.93  4967.2  719.20  4967.7  718.20  5032.8  719.20  5067.3  727.01
  5072.1  732.26  5085.9  740.31  5096.6  740.96  5104.3  744.97  5118.8  762.32
  5144.8  776.88  5171.2  779.74  5201.3  793.39  5248.2  810.40  5254.4  793.44
  5259.8  791.65  5259.9  788.83  5260.0  796.05  5265.2  816.48  5282.4  822.11
#Mann=3,-1,0
  4631.6    0.15       0  4967.2    0.05       0  5032.8    0.15       0
Bank Sta=4967.2,5032.8
XS Rating Curve= 0
Exp/Cntr=0.3,0.1

Type RM Length L Ch R = 1,48500,676,676,676
BEGIN DESCRIPTION:
Chauga River 97.0
END DESCRIPTION:
XS GIS Cut Line= 3
      1355057.27      1043673.55      1354764.06      1043690.45
      1354491.12      1043757.71
#Sta/Elev= 30
  4706.3  800.91  4717.8  798.40  4747.0  798.37  4753.3  797.15  4754.4  795.51
  4789.4  790.79  4800.0  785.53  4835.7  773.63  4872.9  767.71  4889.9  762.37
  4912.0  745.21  4935.8  731.38  4940.3  723.87  4943.8  726.44  4959.2  718.99
  4966.4  710.31  4966.8  712.12  4967.2  710.31  4967.7  709.31  5032.8  710.31
  5036.0  715.61  5041.3  717.15  5063.5  721.70  5068.4  720.90  5072.7  723.85
  5081.6  723.14  5106.0  741.10  5152.1  768.06  5249.4  813.81  5281.1  832.64
#Mann=3,-1,0
  4706.3    0.15       0  4967.2    0.05       0  5032.8    0.15       0
Bank Sta=4967.2,5032.8
XS Rating Curve= 0
Exp/Cntr=0.3,0.1

Type RM Length L Ch R = 1,47824,324,324,324
BEGIN DESCRIPTION:
Chauga River 96.0
END DESCRIPTION:
XS GIS Cut Line= 3
      1354859.46      1042814.78      1354643.73      1043087.33
      1354338.33      1043386.34
#Sta/Elev= 30
  4652.4  755.10  4694.8  757.34  4732.2  761.98  4759.0  762.31  4781.5  766.11
  4830.0  762.72  4857.6  763.01  4865.6  756.11  4871.0  758.41  4881.3  755.78
  4911.9  753.78  4930.2  740.13  4933.5  740.17  4937.2  735.56  4938.0  728.05
  4941.6  733.09  4943.9  720.41  4945.3  717.32  4964.2  715.79  4966.1  707.82
  4966.6  706.82  5033.9  707.82  5064.9  710.41  5089.1  716.72  5095.9  714.71
  5159.8  719.79  5222.3  748.56  5268.3  763.37  5380.5  779.59  5427.4  788.49
#Mann=3,-1,0
  4652.4    0.15       0  4966.1    0.05       0  5033.9    0.15       0
Bank Sta=4966.1,5033.9
XS Rating Curve= 0
Exp/Cntr=0.3,0.1

Type RM Length L Ch R = 1,47500,500,500,500
BEGIN DESCRIPTION:
Chauga River 95.0
END DESCRIPTION:
XS GIS Cut Line= 3
      1354533.44      1042738.14      1354340.06      1042979.41
      1354125.43      1043202.26
#Sta/Elev= 30
  4690.8  800.11  4751.8  791.78  4753.5  796.70  4761.8  789.73  4818.9  774.58
  4866.1  757.31  4881.9  755.41  4889.8  751.28  4911.0  731.71  4916.7  736.10
  4924.9  715.50  4925.0  720.51  4929.0  725.13  4935.7  720.10  4940.7  713.00
  4943.0  706.28  4943.8  710.45  4966.1  706.28  4966.6  705.28  5033.9  706.28
  5045.6  706.28  5064.6  714.90  5077.7  724.17  5083.6  724.92  5099.4  734.66
  5120.7  750.79  5136.8  759.71  5178.5  776.39  5246.7  795.31  5309.4  805.33
#Mann=3,-1,0
  4690.8    0.15       0  4966.1    0.05       0  5033.9    0.15       0
Bank Sta=4966.1,5033.9
XS Rating Curve= 0
Exp/Cntr=0.3,0.1

Type RM Length L Ch R = 1,47000,500,500,500
BEGIN DESCRIPTION:
Chauga River 94.0
END DESCRIPTION:
XS GIS Cut Line= 3
      1354268.24      1042266.32      1354014.80      1042609.22
      1353829.61      1042880.91
#Sta/Elev= 30
  4573.6  864.13  4681.7  842.34  4754.5  821.27  4769.7  819.28  4779.3  824.12
  4803.1  807.13  4828.6  799.37  4839.4  792.85  4854.2  778.39  4870.4  776.25
  4887.3  764.60  4903.1  746.09  4916.6  722.85  4917.8  708.47  4919.0  720.45
  4920.8  723.97  4923.7  718.04  4932.0  711.27  4932.4  731.28  4932.9  722.03
  4939.2  702.37  4943.2  699.07  4947.7  701.52  4966.1  698.90  4966.6  697.90
  5033.9  698.90  5105.7  715.04  5137.4  717.35  5197.8  728.90  5328.8  772.90
#Mann=3,-1,0
  4573.6    0.15       0  4966.1    0.05       0  5033.9    0.15       0
Bank Sta=4966.1,5033.9
XS Rating Curve= 0
Exp/Cntr=0.3,0.1

Type RM Length L Ch R = 1,46500,500,500,500
BEGIN DESCRIPTION:
Chauga River 93.0
END DESCRIPTION:
XS GIS Cut Line= 3
      1353521.02      1042159.25      1353546.61      1042493.27
      1353572.03      1042942.15
#Sta/Elev= 30
  4665.0  783.42  4766.9  746.63  4769.3  755.64  4770.5  784.05  4771.5  764.25
  4771.6  744.86  4846.2  712.30  4850.9  711.47  4852.8  715.23  4856.2  704.94
  4860.8  708.97  4869.9  706.64  4871.9  703.71  4878.9  699.73  4890.8  700.46
  4929.3  695.24  4963.8  695.37  4966.1  692.84  4966.6  691.84  5033.4  691.84
  5033.9  692.84  5106.8  707.56  5167.6  733.77  5208.4  748.92  5243.8  755.93
  5254.3  759.74  5296.8  768.00  5394.8  780.66  5423.4  786.77  5449.6  795.21
#Mann=3,-1,0
  4665.0    0.15       0  4966.1    0.05       0  5033.9    0.15       0
Bank Sta=4966.1,5033.9
XS Rating Curve= 0
Exp/Cntr=0.3,0.1

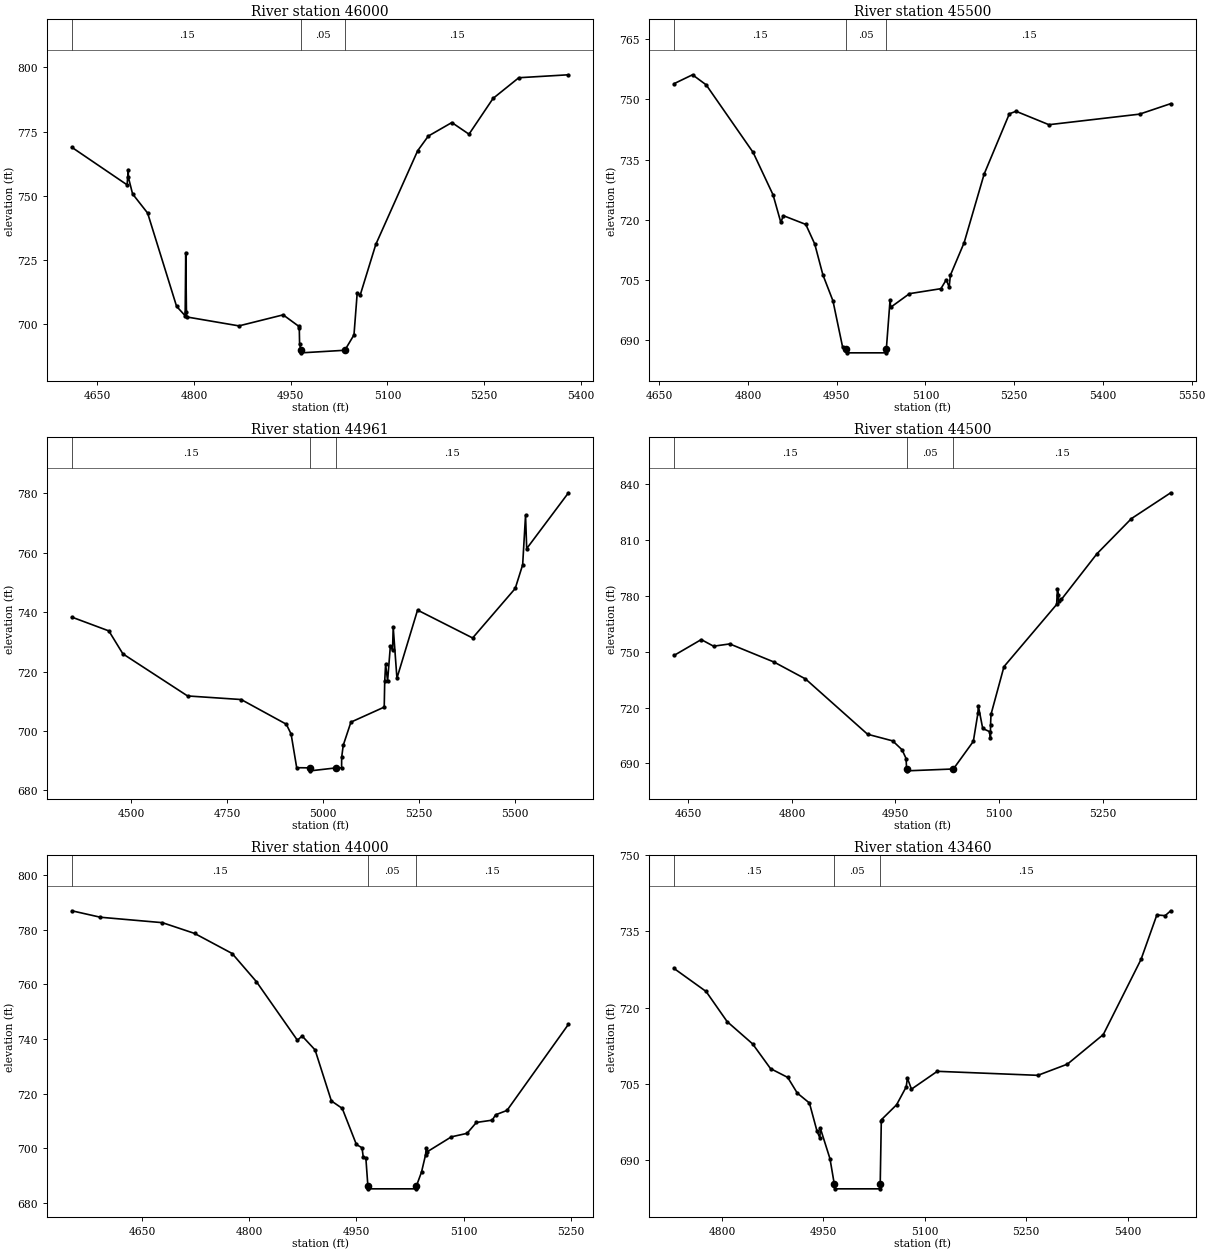
Type RM Length L Ch R = 1,46000,500,500,500
BEGIN DESCRIPTION:
Chauga River 92.0
END DESCRIPTION:
XS GIS Cut Line= 3
      1353222.63      1042200.04      1353055.55      1042551.66
      1352883.46      1042891.14
#Sta/Elev= 30
  4610.7  768.94  4696.4  754.32  4698.2  760.27  4698.4  757.24  4704.9  750.79
  4728.2  743.34  4773.1  707.04  4786.4  703.37  4787.3  727.96  4788.4  704.72
  4788.8  702.91  4869.8  699.43  4938.3  703.72  4962.8  699.22  4963.3  698.61
  4963.8  692.26  4966.1  689.94  4966.6  688.94  5033.9  689.94  5048.1  695.92
  5053.1  712.22  5057.7  711.38  5081.9  731.12  5146.8  767.59  5163.3  773.30
  5199.8  778.57  5226.4  774.04  5263.7  787.96  5303.6  796.01  5380.6  797.16
#Mann=3,-1,0
  4610.7    0.15       0  4966.1    0.05       0  5033.9    0.15       0
Bank Sta=4966.1,5033.9
XS Rating Curve= 0
Exp/Cntr=0.3,0.1

Type RM Length L Ch R = 1,45500,539,539,539
BEGIN DESCRIPTION:
Chauga River 91.0
END DESCRIPTION:
XS GIS Cut Line= 3
      1352929.34      1042046.78      1352669.89      1042242.51
      1352335.13      1042633.34
#Sta/Elev= 30
  4675.0  753.93  4706.2  756.15  4729.3  753.64  4808.7  736.78  4842.4  726.20
  4855.5  719.33  4859.8  721.01  4897.7  718.83  4912.8  713.96  4926.6  706.26
  4943.6  699.78  4960.0  688.20  4966.1  687.80  4966.6  686.80  5033.4  686.80
  5033.9  687.80  5040.2  700.04  5041.1  698.15  5073.0  701.56  5126.1  702.80
  5135.2  705.03  5140.1  703.16  5142.1  706.14  5165.4  714.28  5199.2  731.38
  5241.8  746.41  5253.1  747.05  5308.7  743.70  5461.9  746.33  5514.6  748.95
#Mann=3,-1,0
  4675.0    0.15       0  4966.1    0.05       0  5033.9    0.15       0
Bank Sta=4966.1,5033.9
XS Rating Curve= 0
Exp/Cntr=0.3,0.1

Type RM Length L Ch R = 1,44961,461,461,461
BEGIN DESCRIPTION:
Chauga River 90.0
END DESCRIPTION:
XS GIS Cut Line= 3
      1352845.25      1041960.04      1352193.15      1042015.97
      1351554.75      1041993.20
#Sta/Elev= 30
  4345.5  738.36  4441.9  733.71  4478.5  725.98  4646.9  711.80  4786.5  710.59
  4904.0  702.28  4916.5  698.98  4931.1  687.63  4966.1  687.57  4966.6  686.57
  5033.9  687.57  5048.0  687.57  5048.2  691.11  5052.3  695.19  5072.3  702.98
  5159.0  708.04  5160.3  716.71  5162.6  722.42  5167.8  716.86  5175.0  728.63
  5180.7  727.19  5182.4  735.00  5192.1  717.78  5245.8  740.72  5389.2  731.33
  5500.1  748.00  5519.5  755.98  5527.0  772.66  5530.0  761.43  5638.8  780.24
#Mann=3,-1,0
  4345.5    0.15       0  4966.1    0.05       0  5033.9    0.15       0
Bank Sta=4966.1,5033.9
XS Rating Curve= 0
Exp/Cntr=0.3,0.1

Type RM Length L Ch R = 1,44500,500,500,500
BEGIN DESCRIPTION:
Chauga River 89.0
END DESCRIPTION:
XS GIS Cut Line= 3
      1352829.45      1041806.21      1352481.46      1041678.43
      1352146.49      1041581.55
#Sta/Elev= 30
  4629.3  747.99  4668.7  756.50  4686.5  752.95  4710.0  754.17  4774.1  744.44
  4819.7  735.37  4909.6  705.68  4946.0  702.11  4959.5  697.36  4965.4  692.63
  4966.1  687.03  4966.6  686.03  5033.9  687.03  5062.8  701.85  5069.4  716.91
  5070.0  721.01  5076.4  708.77  5086.8  707.00  5087.6  703.89  5087.7  710.41
  5088.4  716.34  5107.2  741.99  5183.5  775.36  5184.6  783.85  5186.1  780.48
  5186.4  777.09  5190.5  778.12  5241.9  802.60  5291.8  821.46  5348.7  835.32
#Mann=3,-1,0
  4629.3    0.15       0  4966.1    0.05       0  5033.9    0.15       0
Bank Sta=4966.1,5033.9
XS Rating Curve= 0
Exp/Cntr=0.3,0.1

Type RM Length L Ch R = 1,44000,540,540,540
BEGIN DESCRIPTION:
Chauga River 88.0
END DESCRIPTION:
XS GIS Cut Line= 3
      1353197.91      1041419.77      1352773.93      1041274.74
      1352532.92      1041222.07
#Sta/Elev= 30
  4551.9  787.02  4591.9  784.65  4678.6  782.66  4723.7  778.71  4776.2  771.35
  4810.1  761.04  4867.5  739.53  4874.1  741.10  4892.2  735.99  4915.0  717.28
  4930.2  714.55  4950.0  701.31  4957.9  700.09  4959.5  696.90  4963.3  696.19
  4966.1  686.04  4966.6  685.04  5033.4  685.04  5033.9  686.04  5041.1  691.18
  5046.7  697.42  5047.8  700.08  5049.0  698.62  5082.9  704.11  5104.8  705.39
  5117.9  709.39  5140.1  710.23  5144.7  712.19  5160.7  713.80  5246.7  745.40
#Mann=3,-1,0
  4551.9    0.15       0  4966.1    0.05       0  5033.9    0.15       0
Bank Sta=4966.1,5033.9
XS Rating Curve= 0
Exp/Cntr=0.3,0.1

Type RM Length L Ch R = 1,43460,460,460,460
BEGIN DESCRIPTION:
Chauga River 87.0
END DESCRIPTION:
XS GIS Cut Line= 3
      1353181.29      1040623.76      1352970.15      1040793.48
      1352600.16      1041072.81
#Sta/Elev= 30
  4729.1  727.71  4776.5  723.18  4807.6  717.25  4845.3  712.86  4871.8  707.99
  4897.2  706.26  4911.3  703.18  4929.3  701.22  4940.5  695.69  4944.8  694.33
  4945.4  696.27  4959.7  690.25  4966.0  685.32  4966.5  684.32  5033.5  684.32
  5034.0  685.32  5035.6  697.69  5035.9  697.95  5058.2  700.87  5072.4  704.39
  5074.2  706.12  5080.2  703.95  5118.4  707.46  5267.1  706.67  5310.8  708.87
  5363.9  714.70  5419.7  729.49  5443.1  738.25  5455.4  738.11  5463.6  739.07
#Mann=3,-1,0
  4729.1    0.15       0  4966.0    0.05       0  5034.0    0.15       0
Bank Sta=4966,5034
XS Rating Curve= 0
Exp/Cntr=0.3,0.1

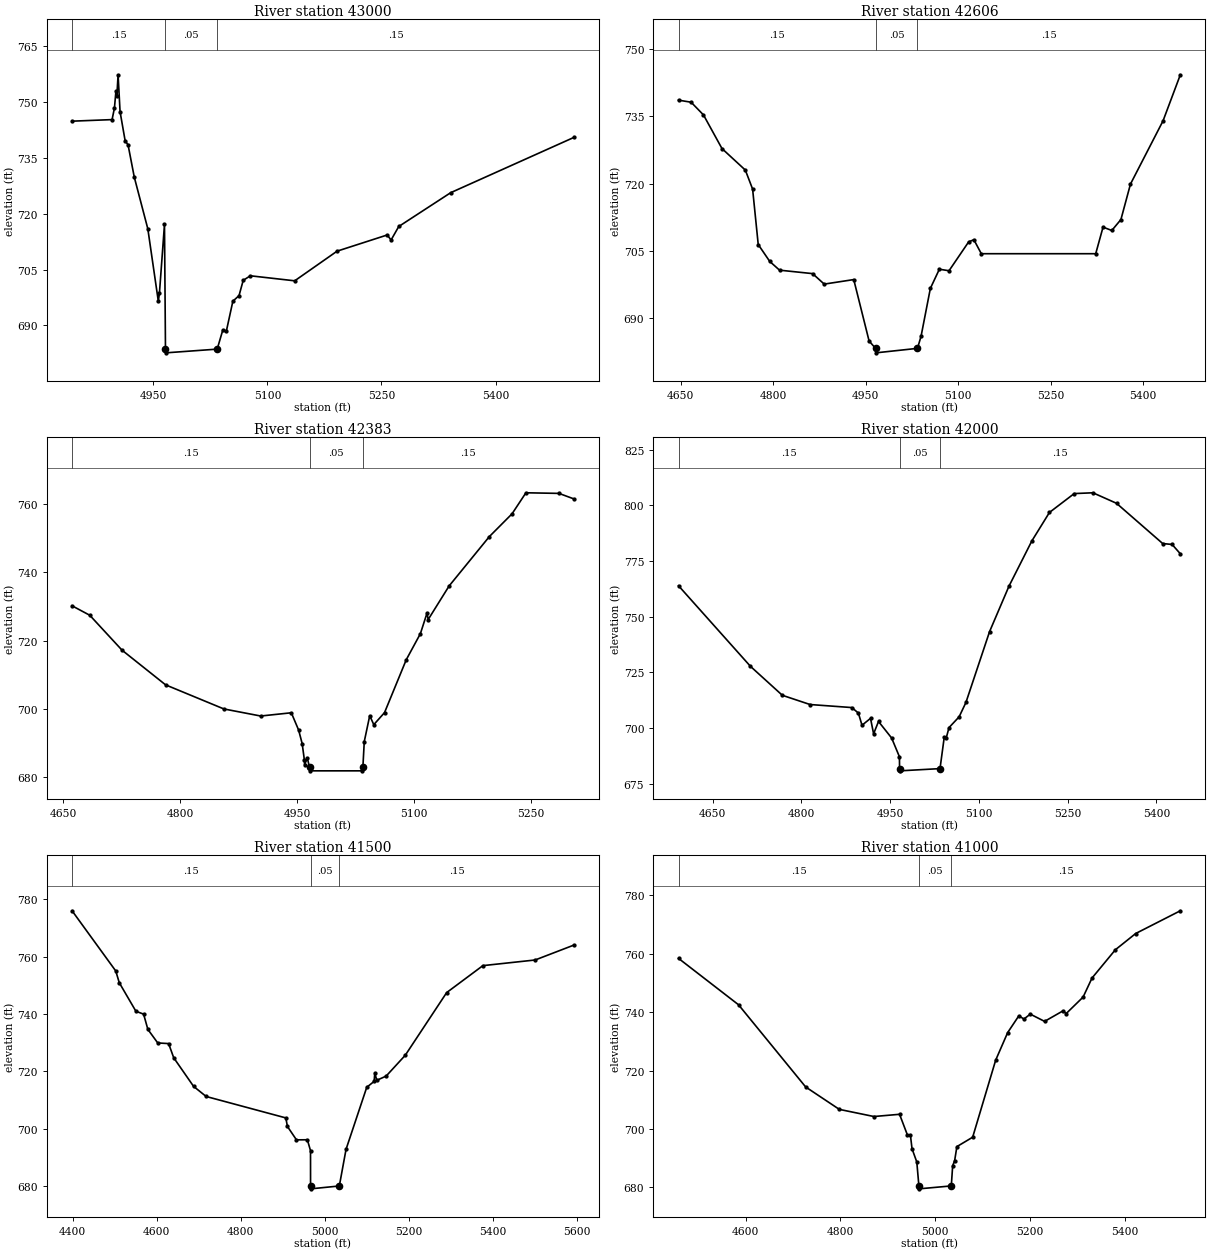
Type RM Length L Ch R = 1,43000,394,394,394
BEGIN DESCRIPTION:
Chauga River 86.0
END DESCRIPTION:
XS GIS Cut Line= 4
      1352578.55      1040455.62      1352612.05      1040608.80
      1352645.80      1040902.30      1352561.76      1041091.98
#Sta/Elev= 30
  4843.2  744.88  4895.8  745.30  4898.9  748.40  4900.9  753.02  4902.1  751.73
  4903.7  757.35  4906.3  747.43  4913.0  739.58  4916.8  738.53  4925.0  729.83
  4942.8  715.94  4956.6  696.48  4958.1  698.74  4964.7  717.14  4966.0  683.61
  4966.5  682.61  5034.0  683.61  5041.4  688.77  5046.0  688.41  5054.6  696.49
  5062.7  697.99  5068.2  702.10  5077.6  703.32  5135.9  701.97  5191.6  709.94
  5257.5  714.29  5262.6  712.94  5272.7  716.57  5341.0  725.66  5502.9  740.51
#Mann=3,-1,0
  4843.2    0.15       0  4966.0    0.05       0  5034.0    0.15       0
Bank Sta=4966,5034
XS Rating Curve= 0
Exp/Cntr=0.3,0.1

Type RM Length L Ch R = 1,42606,223,223,223
BEGIN DESCRIPTION:
Chauga River 85.0
END DESCRIPTION:
XS GIS Cut Line= 4
      1352483.14      1040525.43      1352316.21      1040671.11
      1352269.17      1040794.60      1352165.52      1041243.28
#Sta/Elev= 30
  4646.3  738.60  4666.7  738.14  4686.8  735.30  4716.8  727.80  4754.7  723.00
  4766.5  718.76  4775.6  706.40  4794.3  702.63  4810.2  700.68  4863.8  699.91
  4882.7  697.57  4930.6  698.58  4955.5  684.88  4966.0  683.24  4966.5  682.24
  5034.0  683.24  5039.8  685.92  5054.9  696.61  5069.5  700.89  5085.2  700.55
  5117.1  707.00  5125.5  707.47  5137.6  704.35  5323.2  704.35  5335.1  710.28
  5349.3  709.53  5364.1  711.97  5379.6  719.88  5432.5  734.00  5460.5  744.26
#Mann=3,-1,0
  4646.3    0.15       0  4966.0    0.05       0  5034.0    0.15       0
Bank Sta=4966,5034
XS Rating Curve= 0
Exp/Cntr=0.3,0.1

Type RM Length L Ch R = 1,42383,383,383,383
BEGIN DESCRIPTION:
Chauga River 84.5
END DESCRIPTION:
XS GIS Cut Line= 4
      1352455.89      1040513.23      1352261.57      1040634.69
      1352152.83      1040649.53      1351848.69      1040671.11
#Sta/Elev= 30
  4661.1  730.20  4683.8  727.43  4725.2  717.20  4781.1  707.04  4855.9  699.98
  4903.1  697.91  4942.4  698.86  4951.8  693.78  4956.3  689.85  4959.2  684.95
  4959.4  683.62  4962.9  685.60  4965.8  682.85  4966.3  681.85  5033.7  681.85
  5034.2  682.85  5036.0  690.43  5043.0  698.01  5048.2  695.38  5062.0  698.91
  5089.9  714.42  5108.0  722.04  5116.5  728.06  5118.0  726.18  5144.9  736.03
  5196.5  750.48  5225.6  757.15  5243.4  763.31  5285.8  763.13  5304.9  761.52
#Mann=3,-1,0
  4661.1    0.15       0  4965.8    0.05       0  5034.2    0.15       0
Bank Sta=4965.8,5034.2
XS Rating Curve= 0
Exp/Cntr=0.3,0.1

Type RM Length L Ch R = 1,42000,500,500,500
BEGIN DESCRIPTION:
Chauga River 84.0
END DESCRIPTION:
XS GIS Cut Line= 3
      1352667.71      1040386.29      1352271.51      1040289.31
      1351849.92      1040161.62
#Sta/Elev= 30
  4592.1  763.85  4713.7  727.66  4767.6  714.66  4814.5  710.51  4885.1  709.15
  4896.2  706.66  4902.3  701.20  4916.7  704.30  4921.9  697.36  4930.2  702.90
  4952.4  695.47  4965.6  687.04  4965.8  681.73  4966.3  680.73  5034.2  681.73
  5041.4  695.95  5044.8  695.58  5049.4  700.15  5066.5  704.99  5078.0  711.43
  5118.0  743.27  5150.9  763.73  5189.5  784.00  5219.2  796.77  5261.1  805.25
  5292.7  805.61  5332.6  800.89  5410.7  782.81  5426.6  782.40  5440.5  778.22
#Mann=3,-1,0
  4592.1    0.15       0  4965.8    0.05       0  5034.2    0.15       0
Bank Sta=4965.8,5034.2
XS Rating Curve= 0
Exp/Cntr=0.3,0.1

Type RM Length L Ch R = 1,41500,500,500,500
BEGIN DESCRIPTION:
Chauga River 83.0
END DESCRIPTION:
XS GIS Cut Line= 3
      1352964.30      1040134.67      1352450.08      1039823.19
      1351939.75      1039523.53
#Sta/Elev= 30
  4398.8  776.06  4502.7  755.04  4511.0  750.95  4550.6  740.98  4568.9  739.98
  4579.0  734.65  4602.5  729.92  4628.3  729.70  4640.5  724.74  4687.7  714.76
  4717.6  711.23  4907.0  703.75  4910.8  700.76  4932.3  696.09  4958.2  696.12
  4965.7  692.31  4965.8  679.99  4966.3  678.99  5034.2  679.99  5050.2  692.80
  5099.4  714.44  5117.0  716.51  5118.5  719.40  5123.3  716.88  5145.5  718.35
  5190.9  725.61  5289.4  747.50  5375.5  756.91  5499.7  758.88  5591.8  764.08
#Mann=3,-1,0
  4398.8    0.15       0  4965.8    0.05       0  5034.2    0.15       0
Bank Sta=4965.8,5034.2
XS Rating Curve= 0
Exp/Cntr=0.3,0.1

Type RM Length L Ch R = 1,41000,500,500,500
BEGIN DESCRIPTION:
Chauga River 82.0
END DESCRIPTION:
XS GIS Cut Line= 3
      1353224.97      1039724.98      1352766.78      1039436.41
      1352274.99      1039275.00
#Sta/Elev= 30
  4458.5  758.41  4585.1  742.54  4726.8  714.41  4797.9  706.73  4870.9  704.29
  4925.0  705.05  4941.4  698.05  4948.0  697.83  4951.3  693.27  4961.4  688.72
  4965.8  680.54  4966.3  679.54  5034.2  680.54  5037.1  687.47  5041.2  689.12
  5046.0  693.99  5079.3  697.21  5127.9  723.59  5153.2  733.02  5176.8  738.76
  5187.5  737.65  5200.9  739.33  5231.1  736.85  5270.2  740.47  5276.6  739.51
  5312.4  745.17  5331.2  751.68  5380.5  761.36  5423.4  766.92  5517.6  774.70
#Mann=3,-1,0
  4458.5    0.15       0  4965.8    0.05       0  5034.2    0.15       0
Bank Sta=4965.8,5034.2
XS Rating Curve= 0
Exp/Cntr=0.3,0.1

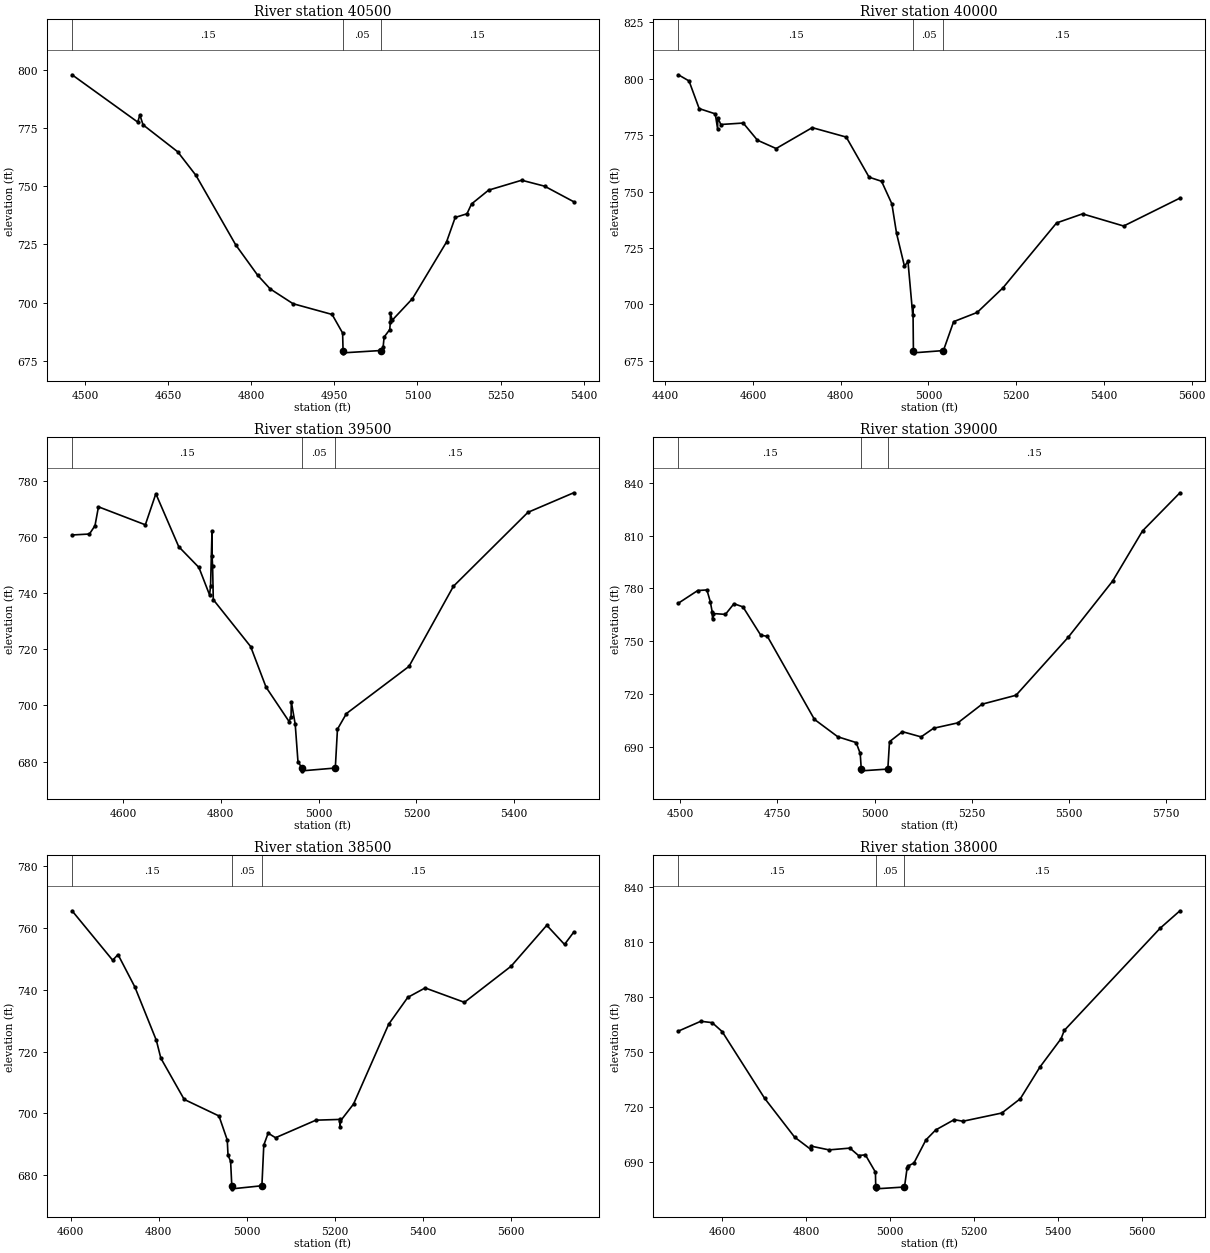
Type RM Length L Ch R = 1,40500,500,500,500
BEGIN DESCRIPTION:
Chauga River 81.0
END DESCRIPTION:
XS GIS Cut Line= 3
      1353575.02      1039275.01      1353096.99      1039062.11
      1352730.67      1038953.79
#Sta/Elev= 30
  4476.7  797.74  4595.2  777.46  4599.1  780.51  4604.8  776.28  4667.3  764.73
  4700.3  754.60  4772.1  724.79  4811.7  711.77  4834.2  705.93  4875.5  699.57
  4946.0  694.96  4965.0  687.00  4965.8  679.50  4966.3  678.50  5034.2  679.50
  5038.2  681.15  5039.9  685.28  5050.1  688.49  5051.0  691.54  5051.3  695.38
  5054.6  692.51  5091.1  701.76  5152.5  726.02  5168.2  736.57  5189.4  738.13
  5197.7  742.35  5228.4  748.26  5288.2  752.52  5329.5  749.97  5382.0  743.31
#Mann=3,-1,0
  4476.7    0.15       0  4965.8    0.05       0  5034.2    0.15       0
Bank Sta=4965.8,5034.2
XS Rating Curve= 0
Exp/Cntr=0.3,0.1

Type RM Length L Ch R = 1,40000,500,500,500
BEGIN DESCRIPTION:
Chauga River 80.0
END DESCRIPTION:
XS GIS Cut Line= 3
      1353539.41      1038333.71      1353083.11      1038675.48
      1352586.86      1038962.75
#Sta/Elev= 30
  4429.9  801.71  4454.3  798.98  4477.4  786.74  4514.1  784.40  4519.4  777.81
  4519.8  782.75  4526.7  779.69  4577.8  780.34  4610.3  772.73  4652.9  769.05
  4735.1  778.30  4812.7  774.12  4864.8  756.36  4893.2  754.54  4916.7  744.56
  4927.4  731.47  4945.4  716.94  4953.4  719.05  4964.3  695.42  4964.8  699.36
  4965.8  679.57  4966.3  678.57  5034.2  679.57  5057.5  692.38  5111.2  696.46
  5169.9  707.34  5292.2  736.10  5351.4  740.12  5445.1  734.73  5573.4  747.10
#Mann=3,-1,0
  4429.9    0.15       0  4965.8    0.05       0  5034.2    0.15       0
Bank Sta=4965.8,5034.2
XS Rating Curve= 0
Exp/Cntr=0.3,0.1

Type RM Length L Ch R = 1,39500,500,500,500
BEGIN DESCRIPTION:
Chauga River 79.0
END DESCRIPTION:
XS GIS Cut Line= 3
      1352974.98      1038075.02      1352637.75      1038449.98
      1352274.97      1038825.03
#Sta/Elev= 30
  4495.7  760.65  4531.2  760.99  4542.6  763.95  4549.7  770.67  4645.6  764.27
  4667.1  775.31  4713.9  756.49  4755.2  749.10  4777.0  739.32  4779.0  742.45
  4782.0  762.09  4782.1  753.04  4783.2  749.62  4784.6  737.65  4861.0  720.97
  4892.5  706.53  4939.7  694.28  4943.7  696.05  4944.2  701.37  4952.2  693.32
  4957.8  680.07  4965.8  677.76  4966.3  676.76  5034.2  677.76  5038.6  691.57
  5057.0  697.14  5185.0  713.92  5275.8  742.40  5428.2  768.70  5521.8  775.66
#Mann=3,-1,0
  4495.7    0.15       0  4965.8    0.05       0  5034.2    0.15       0
Bank Sta=4965.8,5034.2
XS Rating Curve= 0
Exp/Cntr=0.3,0.1

Type RM Length L Ch R = 1,39000,500,500,500
BEGIN DESCRIPTION:
Chauga River 78.0
END DESCRIPTION:
XS GIS Cut Line= 3
      1352625.03      1037874.98      1352220.35      1038177.24
      1351774.99      1038825.01
#Sta/Elev= 30
  4494.9  771.62  4544.9  778.82  4568.5  779.15  4577.1  772.57  4582.1  766.72
  4583.1  762.64  4584.5  765.78  4616.1  765.29  4638.1  771.34  4661.3  769.54
  4707.0  753.52  4724.2  752.82  4845.2  705.78  4905.4  695.91  4952.6  692.63
  4963.1  686.46  4965.8  677.60  4966.3  676.60  5034.2  677.60  5038.5  693.13
  5071.6  698.81  5119.8  695.84  5151.9  700.74  5214.4  703.80  5276.7  714.38
  5364.2  719.45  5498.6  752.34  5612.8  784.17  5689.8  812.61  5786.1  834.23
#Mann=3,-1,0
  4494.9    0.15       0  4965.8    0.05       0  5034.2    0.15       0
Bank Sta=4965.8,5034.2
XS Rating Curve= 0
Exp/Cntr=0.3,0.1

Type RM Length L Ch R = 1,38500,500,500,500
BEGIN DESCRIPTION:
Chauga River 77.0
END DESCRIPTION:
XS GIS Cut Line= 3
      1352002.69      1037544.61      1351810.70      1037892.21
      1351526.38      1038578.12
#Sta/Elev= 30
  4602.9  765.62  4695.2  749.60  4707.3  751.44  4745.6  740.93  4794.4  723.65
  4804.6  717.88  4857.6  704.53  4936.7  699.16  4955.5  691.37  4957.2  686.48
  4963.1  684.49  4965.8  676.56  4966.3  675.56  5034.2  676.56  5038.5  689.73
  5048.4  693.60  5065.1  692.11  5156.9  697.80  5210.8  698.04  5211.5  695.48
  5212.6  697.53  5242.4  703.03  5322.2  728.87  5365.6  737.57  5405.0  740.63
  5494.3  735.97  5600.4  747.67  5681.4  760.92  5721.7  754.72  5742.5  758.67
#Mann=3,-1,0
  4602.9    0.15       0  4965.8    0.05       0  5034.2    0.15       0
Bank Sta=4965.8,5034.2
XS Rating Curve= 0
Exp/Cntr=0.3,0.1

Type RM Length L Ch R = 1,38000,500,500,500
BEGIN DESCRIPTION:
Chauga River 76.0
END DESCRIPTION:
XS GIS Cut Line= 3
      1351575.00      1037325.01      1351335.23      1037768.20
      1351125.01      1038424.98
#Sta/Elev= 30
  4496.1  761.46  4549.6  766.84  4576.6  766.09  4600.3  761.24  4701.2  724.88
  4772.7  703.64  4811.3  696.93  4811.8  698.72  4854.6  696.66  4904.4  697.63
  4924.8  693.60  4941.2  693.94  4965.1  684.52  4965.8  676.41  4966.3  675.41
  5034.2  676.41  5040.4  686.75  5042.2  687.79  5056.7  689.50  5085.1  702.06
  5108.4  707.53  5152.5  713.16  5173.2  712.29  5265.8  716.78  5309.8  724.58
  5356.5  741.87  5406.8  757.35  5414.4  761.84  5642.3  817.57  5689.6  827.13
#Mann=3,-1,0
  4496.1    0.15       0  4965.8    0.05       0  5034.2    0.15       0
Bank Sta=4965.8,5034.2
XS Rating Curve= 0
Exp/Cntr=0.3,0.1

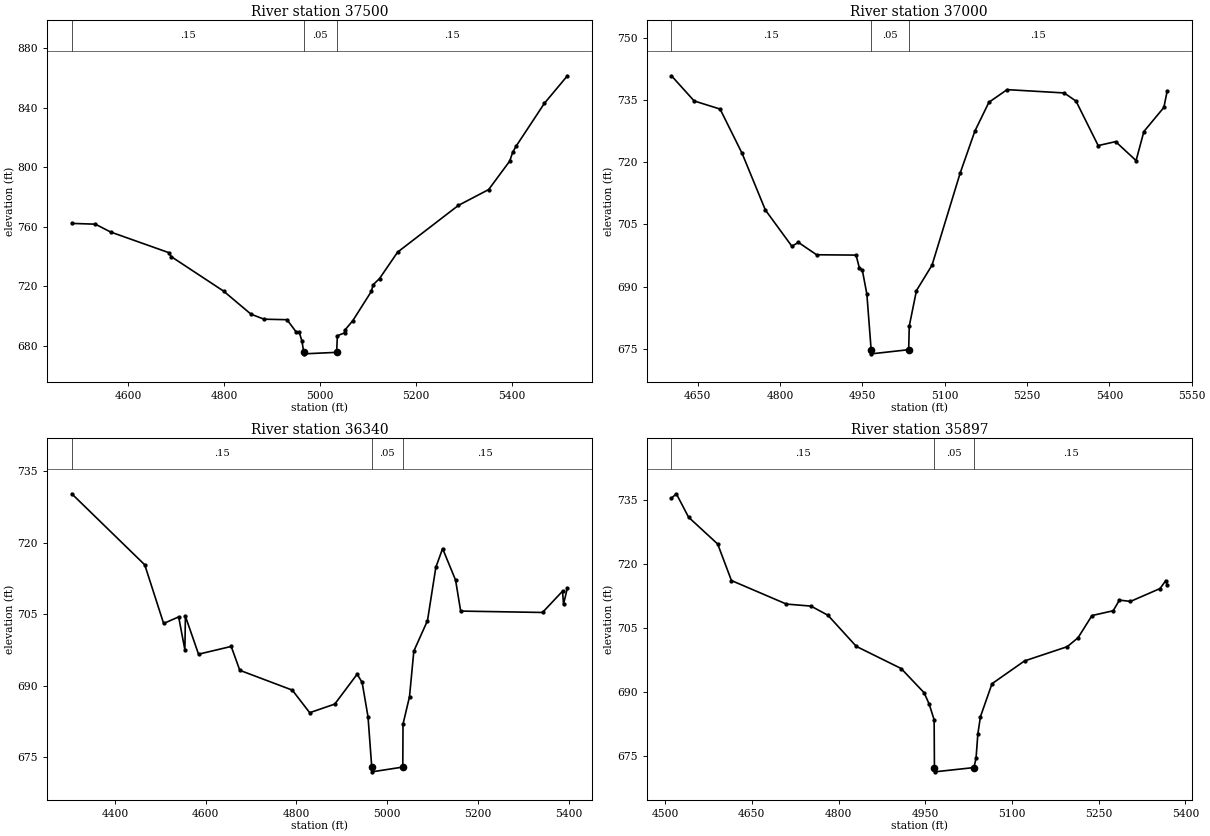
Type RM Length L Ch R = 1,37500,500,500,500
BEGIN DESCRIPTION:
Chauga River 75.0
END DESCRIPTION:
XS GIS Cut Line= 3
      1351175.00      1037174.99      1350869.67      1037592.57
      1350525.02      1037974.98
#Sta/Elev= 30
  4482.7  762.21  4531.9  761.69  4563.6  756.43  4684.4  742.61  4689.9  739.88
  4798.8  716.75  4855.8  701.27  4883.1  697.87  4930.9  697.54  4949.5  689.51
  4956.5  689.02  4962.0  683.12  4965.8  675.61  4966.3  674.61  5034.2  675.61
  5035.8  686.78  5050.7  688.70  5050.9  690.38  5067.7  696.79  5106.4  716.48
  5110.4  721.08  5123.6  725.18  5161.3  742.95  5287.8  774.31  5350.8  784.94
  5394.6  804.04  5400.9  810.03  5408.2  814.18  5466.8  842.83  5514.8  861.35
#Mann=3,-1,0
  4482.7    0.15       0  4965.8    0.05       0  5034.2    0.15       0
Bank Sta=4965.8,5034.2
XS Rating Curve= 0
Exp/Cntr=0.3,0.1

Type RM Length L Ch R = 1,37000,660,660,660
BEGIN DESCRIPTION:
Chauga River 74.0
END DESCRIPTION:
XS GIS Cut Line= 3
      1350873.07      1037038.28      1350525.75      1037232.84
      1350079.15      1037469.21
#Sta/Elev= 30
  4601.9  740.83  4643.2  734.76  4690.5  732.80  4730.5  722.15  4773.0  708.47
  4821.3  699.73  4833.3  700.64  4866.4  697.67  4938.3  697.59  4944.4  694.47
  4949.7  693.99  4958.0  688.18  4965.8  674.78  4966.3  673.78  5034.2  674.78
  5035.3  680.48  5048.4  689.04  5076.8  695.17  5128.0  717.34  5154.9  727.50
  5180.5  734.45  5213.7  737.49  5317.6  736.69  5339.2  734.73  5379.6  724.00
  5411.4  724.95  5448.7  720.38  5462.9  727.39  5499.3  733.19  5505.3  737.11
#Mann=3,-1,0
  4601.9    0.15       0  4965.8    0.05       0  5034.2    0.15       0
Bank Sta=4965.8,5034.2
XS Rating Curve= 0
Exp/Cntr=0.3,0.1

Type RM Length L Ch R = 1,36340,443,443,443
BEGIN DESCRIPTION:
Chauga River 73.0
END DESCRIPTION:
XS GIS Cut Line= 3
      1350772.86      1036968.48      1350109.32      1036761.41
      1349755.95      1036580.70
#Sta/Elev= 30
  4304.9  730.26  4465.7  715.35  4507.3  703.04  4540.4  704.42  4554.1  697.52
  4555.3  704.55  4584.2  696.59  4656.2  698.22  4675.1  693.21  4790.8  689.05
  4829.1  684.31  4884.3  686.12  4933.6  692.39  4944.6  690.69  4957.6  683.45
  4965.8  672.90  4966.3  671.90  5034.2  672.90  5034.7  681.92  5049.0  687.67
  5058.5  697.24  5088.6  703.63  5107.0  714.82  5121.9  718.76  5150.5  712.14
  5161.7  705.64  5342.0  705.35  5386.1  709.81  5388.3  707.10  5396.9  710.53
#Mann=3,-1,0
  4304.9    0.15       0  4965.8    0.05       0  5034.2    0.15       0
Bank Sta=4965.8,5034.2
XS Rating Curve= 0
Exp/Cntr=0.3,0.1

Type RM Length L Ch R = 1,35897,397,397,397
BEGIN DESCRIPTION:
Chauga River 72.0
END DESCRIPTION:
XS GIS Cut Line= 3
      1350775.57      1036925.54      1350482.81      1036533.86
      1350165.57      1036346.76
#Sta/Elev= 30
  4511.0  735.33  4519.4  736.35  4540.6  730.87  4590.9  724.61  4614.7  716.07
  4709.8  710.57  4752.2  710.10  4781.6  707.96  4830.7  700.68  4908.2  695.51
  4948.0  689.84  4956.6  687.23  4965.3  683.52  4965.8  672.36  4966.3  671.36
  5034.2  672.36  5037.8  674.59  5040.9  680.22  5045.4  684.26  5065.4  691.96
  5121.6  697.28  5195.5  700.61  5214.2  702.70  5238.3  707.89  5275.0  709.01
  5285.7  711.50  5304.9  711.19  5356.0  714.20  5366.0  716.07  5368.3  715.03
#Mann=3,-1,0
  4511.0    0.15       0  4965.8    0.05       0  5034.2    0.15       0
Bank Sta=4965.8,5034.2
XS Rating Curve= 0
Exp/Cntr=0.3,0.1