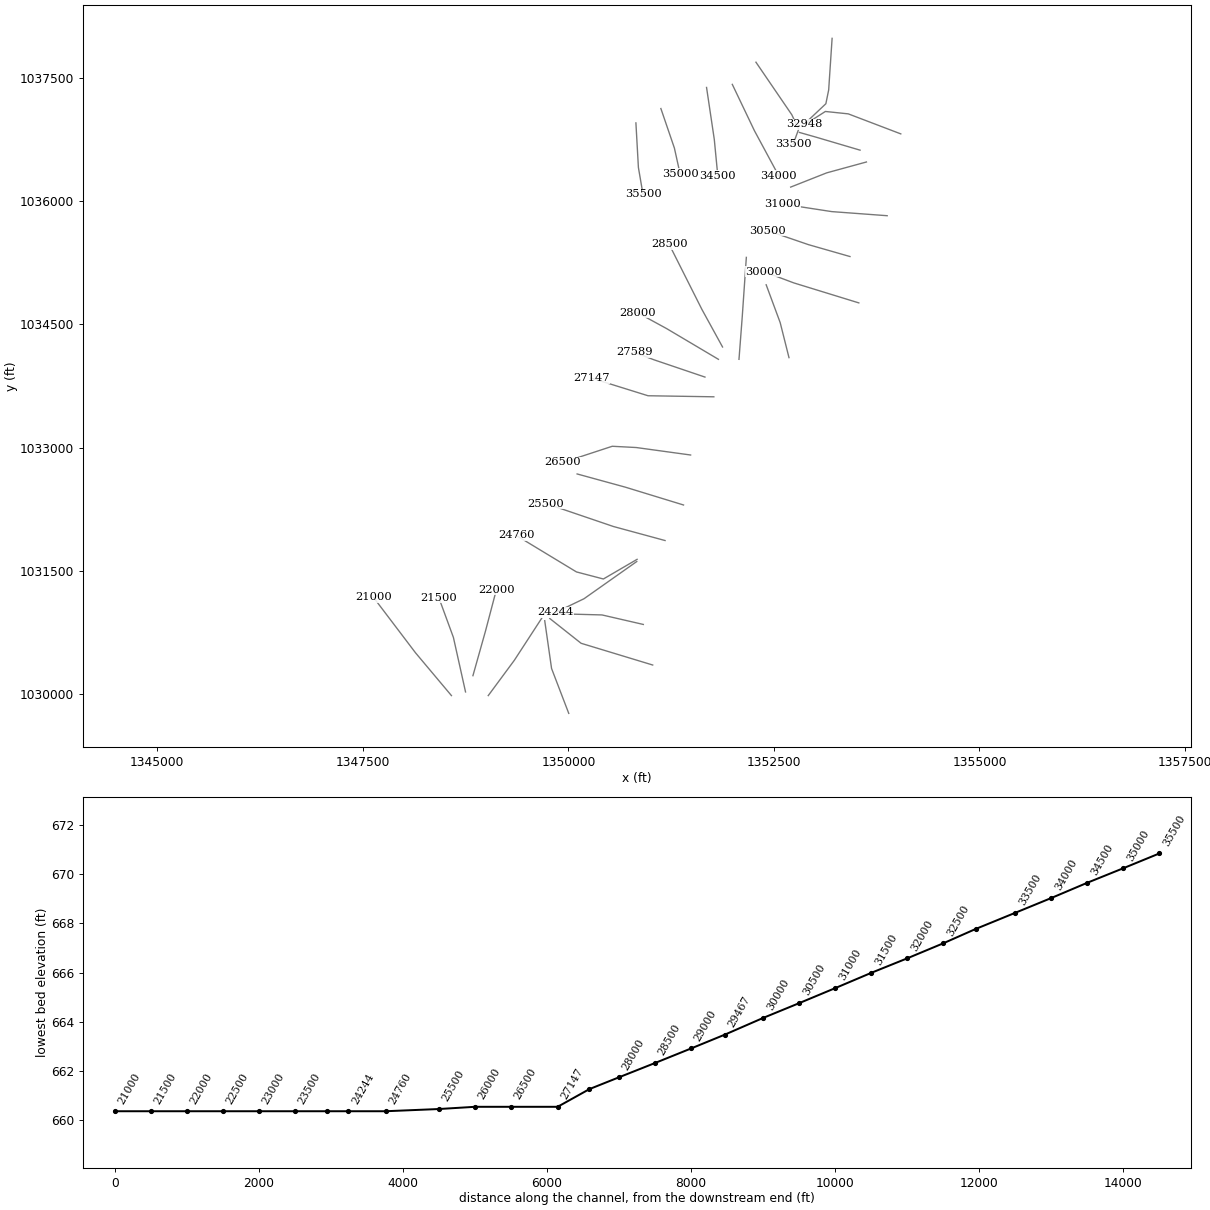
HEC-RAS study Chauga River.prj: Chauga River Limited Detail Study

--- Chauga River.g01 (geometry) --- (continued)

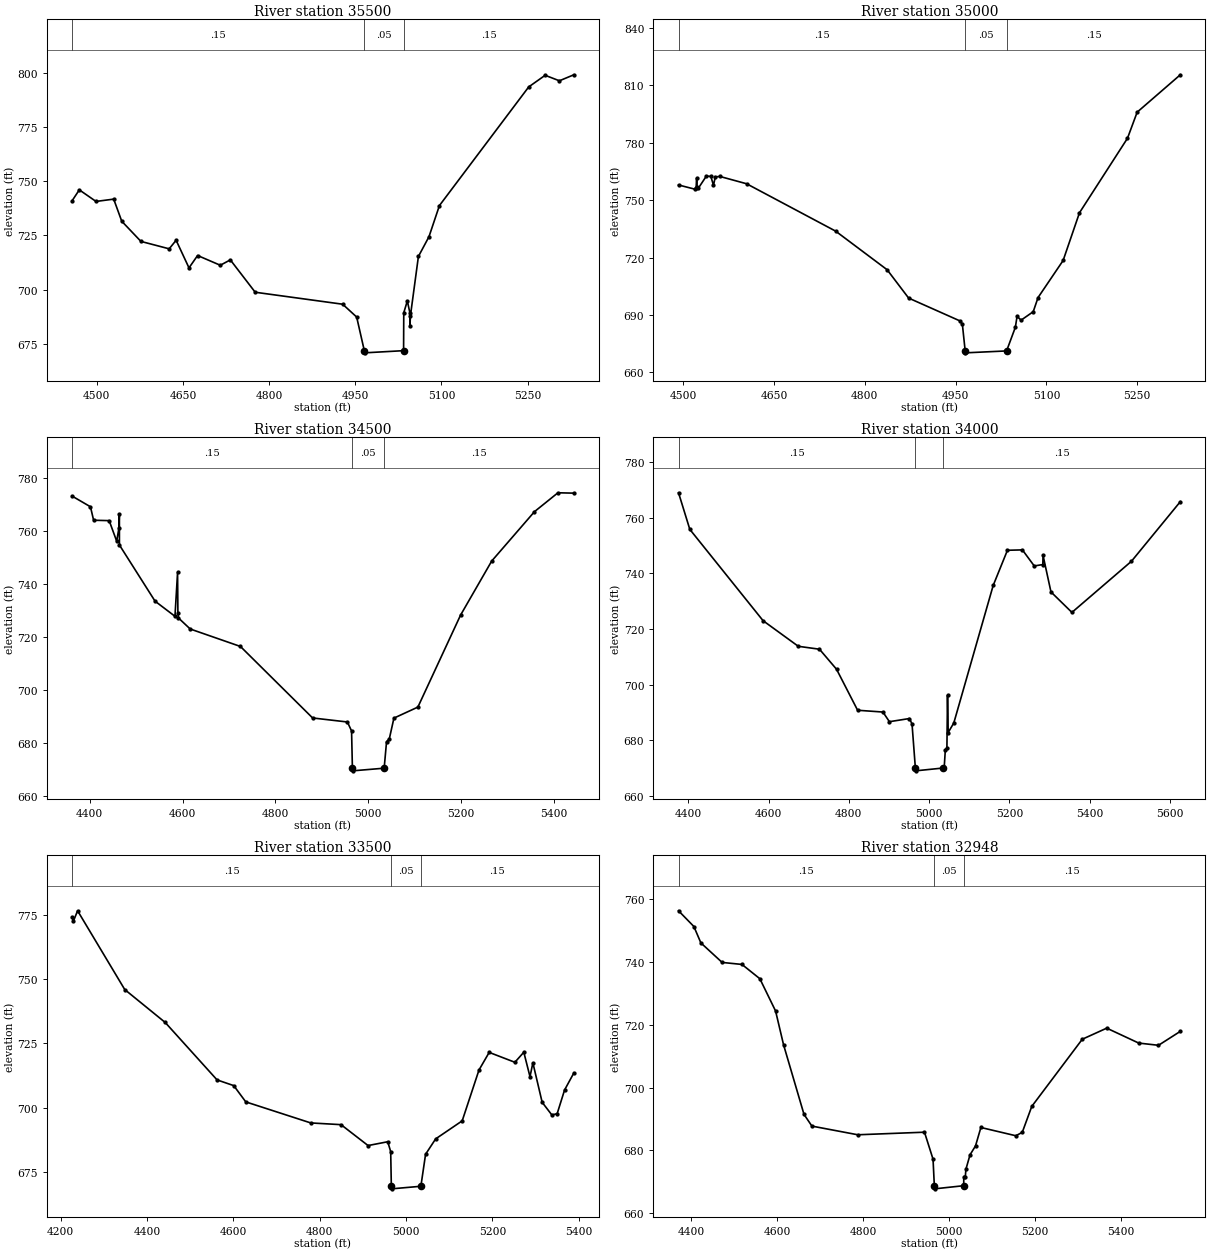
Type RM Length L Ch R = 1,35500,500,500,500
BEGIN DESCRIPTION:
Chauga River 71.0
END DESCRIPTION:
XS GIS Cut Line= 3
      1350821.43      1036950.23      1350851.75      1036407.98
      1350907.65      1036082.04
#Sta/Elev= 30
  4456.9  740.91  4469.5  745.96  4498.6  740.62  4529.4  741.69  4543.4  731.50
  4576.8  722.20  4626.0  718.78  4638.1  722.73  4660.5  710.01  4675.5  715.70
  4715.0  711.21  4732.5  713.69  4775.8  698.77  4928.1  693.25  4952.5  687.34
  4965.8  671.84  4966.3  670.84  5034.2  671.84  5034.5  689.30  5040.7  694.76
  5045.2  689.24  5045.3  683.31  5046.1  687.89  5060.0  715.26  5078.4  724.36
  5096.6  738.72  5252.1  793.41  5280.7  798.76  5305.5  796.23  5330.7  799.00
#Mann=3,-1,0
  4456.9    0.15       0  4965.8    0.05       0  5034.2    0.15       0
Bank Sta=4965.8,5034.2
XS Rating Curve= 0
Exp/Cntr=0.3,0.1

Type RM Length L Ch R = 1,35000,500,500,500
BEGIN DESCRIPTION:
Chauga River 70.0
END DESCRIPTION:
XS GIS Cut Line= 3
      1351125.01      1037124.98      1351289.39      1036644.62
      1351358.75      1036331.00
#Sta/Elev= 30
  4492.3  757.97  4520.0  755.71  4521.3  756.31  4522.2  761.47  4522.9  757.03
  4525.0  756.26  4538.3  762.64  4545.7  762.41  4550.0  757.83  4553.1  762.19
  4560.5  762.43  4604.7  758.61  4751.8  733.85  4836.9  713.66  4872.4  698.86
  4957.7  686.85  4961.2  685.06  4965.8  671.24  4966.3  670.24  5034.2  671.24
  5048.7  683.61  5051.5  689.28  5058.2  687.32  5078.2  691.74  5086.2  699.15
  5127.6  718.51  5154.6  743.44  5233.9  782.38  5249.9  796.02  5321.2  815.56
#Mann=3,-1,0
  4492.3    0.15       0  4965.8    0.05       0  5034.2    0.15       0
Bank Sta=4965.8,5034.2
XS Rating Curve= 0
Exp/Cntr=0.3,0.1

Type RM Length L Ch R = 1,34500,500,500,500
BEGIN DESCRIPTION:
Chauga River 69.0
END DESCRIPTION:
XS GIS Cut Line= 3
      1351680.53      1037381.36      1351774.54      1036750.42
      1351817.14      1036309.78
#Sta/Elev= 30
  4362.1  773.31  4401.7  769.27  4408.5  764.19  4442.0  764.04  4458.2  756.28
  4463.0  761.27  4464.0  766.62  4464.1  754.84  4540.8  733.66  4583.7  727.95
  4589.3  744.50  4590.0  729.34  4591.2  727.32  4616.5  723.16  4724.7  716.57
  4880.1  689.60  4955.0  688.08  4964.0  684.69  4965.8  670.65  4966.3  669.65
  5034.2  670.65  5039.3  680.62  5045.3  681.73  5055.2  689.54  5106.8  693.70
  5198.7  728.39  5265.8  748.80  5357.9  767.43  5408.4  774.55  5442.7  774.41
#Mann=3,-1,0
  4362.1    0.15       0  4965.8    0.05       0  5034.2    0.15       0
Bank Sta=4965.8,5034.2
XS Rating Curve= 0
Exp/Cntr=0.3,0.1

Type RM Length L Ch R = 1,34000,500,500,500
BEGIN DESCRIPTION:
Chauga River 68.0
END DESCRIPTION:
XS GIS Cut Line= 3
      1351993.71      1037418.78      1352262.77      1036855.44
      1352559.87      1036304.43
#Sta/Elev= 30
  4375.7  768.90  4403.8  755.76  4586.4  722.95  4674.1  713.76  4726.9  712.71
  4769.4  705.52  4821.9  690.79  4885.0  690.15  4901.1  686.68  4951.1  687.82
  4957.5  685.85  4965.8  670.03  4966.3  669.03  5034.2  670.03  5037.6  670.03
  5040.5  676.66  5044.4  677.13  5045.9  696.14  5047.6  682.80  5061.6  686.23
  5159.7  735.61  5195.2  748.25  5232.5  748.39  5262.0  742.62  5283.4  743.12
  5283.9  746.43  5303.7  733.28  5355.9  725.93  5504.3  744.31  5626.0  765.71
#Mann=3,-1,0
  4375.7    0.15       0  4965.8    0.05       0  5034.2    0.15       0
Bank Sta=4965.8,5034.2
XS Rating Curve= 0
Exp/Cntr=0.3,0.1

Type RM Length L Ch R = 1,33500,552,552,552
BEGIN DESCRIPTION:
Chauga River 67.0
END DESCRIPTION:
XS GIS Cut Line= 4
      1352281.26      1037688.44      1352717.39      1037049.50
      1352800.70      1036873.77      1352733.91      1036691.61
#Sta/Elev= 30
  4226.4  774.02  4229.3  772.37  4239.2  776.48  4348.4  745.87  4442.1  733.08
  4562.2  710.76  4600.8  708.54  4628.7  702.22  4779.2  694.04  4849.3  693.37
  4911.9  685.25  4957.5  686.73  4964.3  682.88  4965.8  669.43  4966.3  668.43
  5034.2  669.43  5045.1  681.87  5068.4  687.84  5129.9  694.85  5168.8  714.61
  5192.4  721.45  5251.9  717.61  5272.6  721.52  5286.9  712.01  5293.6  717.39
  5315.1  702.05  5337.5  697.15  5349.8  697.63  5367.0  706.84  5388.5  713.47
#Mann=3,-1,0
  4226.4    0.15       0  4965.8    0.05       0  5034.2    0.15       0
Bank Sta=4965.8,5034.2
XS Rating Curve= 0
Exp/Cntr=0.3,0.1

Type RM Length L Ch R = 1,32948,448,448,448
BEGIN DESCRIPTION:
Chauga River 66.0
END DESCRIPTION:
XS GIS Cut Line= 4
      1353207.49      1037978.74      1353165.71      1037350.83
      1353131.59      1037183.41      1352864.44      1036931.43
#Sta/Elev= 30
  4370.7  756.28  4406.4  751.27  4422.7  746.05  4472.1  739.84  4518.3  739.20
  4559.9  734.65  4596.5  724.37  4615.0  713.64  4662.6  691.47  4681.0  687.74
  4787.7  684.98  4942.9  685.80  4962.8  677.21  4965.8  668.77  4966.3  667.77
  5034.2  668.77  5034.3  671.67  5037.9  671.65  5039.3  674.02  5048.9  678.62
  5061.6  681.43  5074.1  687.30  5155.4  684.67  5170.4  685.76  5192.5  694.01
  5310.0  715.39  5366.9  718.92  5441.3  714.17  5487.3  713.46  5538.1  717.90
#Mann=3,-1,0
  4370.7    0.15       0  4965.8    0.05       0  5034.2    0.15       0
Bank Sta=4965.8,5034.2
XS Rating Curve= 0
Exp/Cntr=0.3,0.1

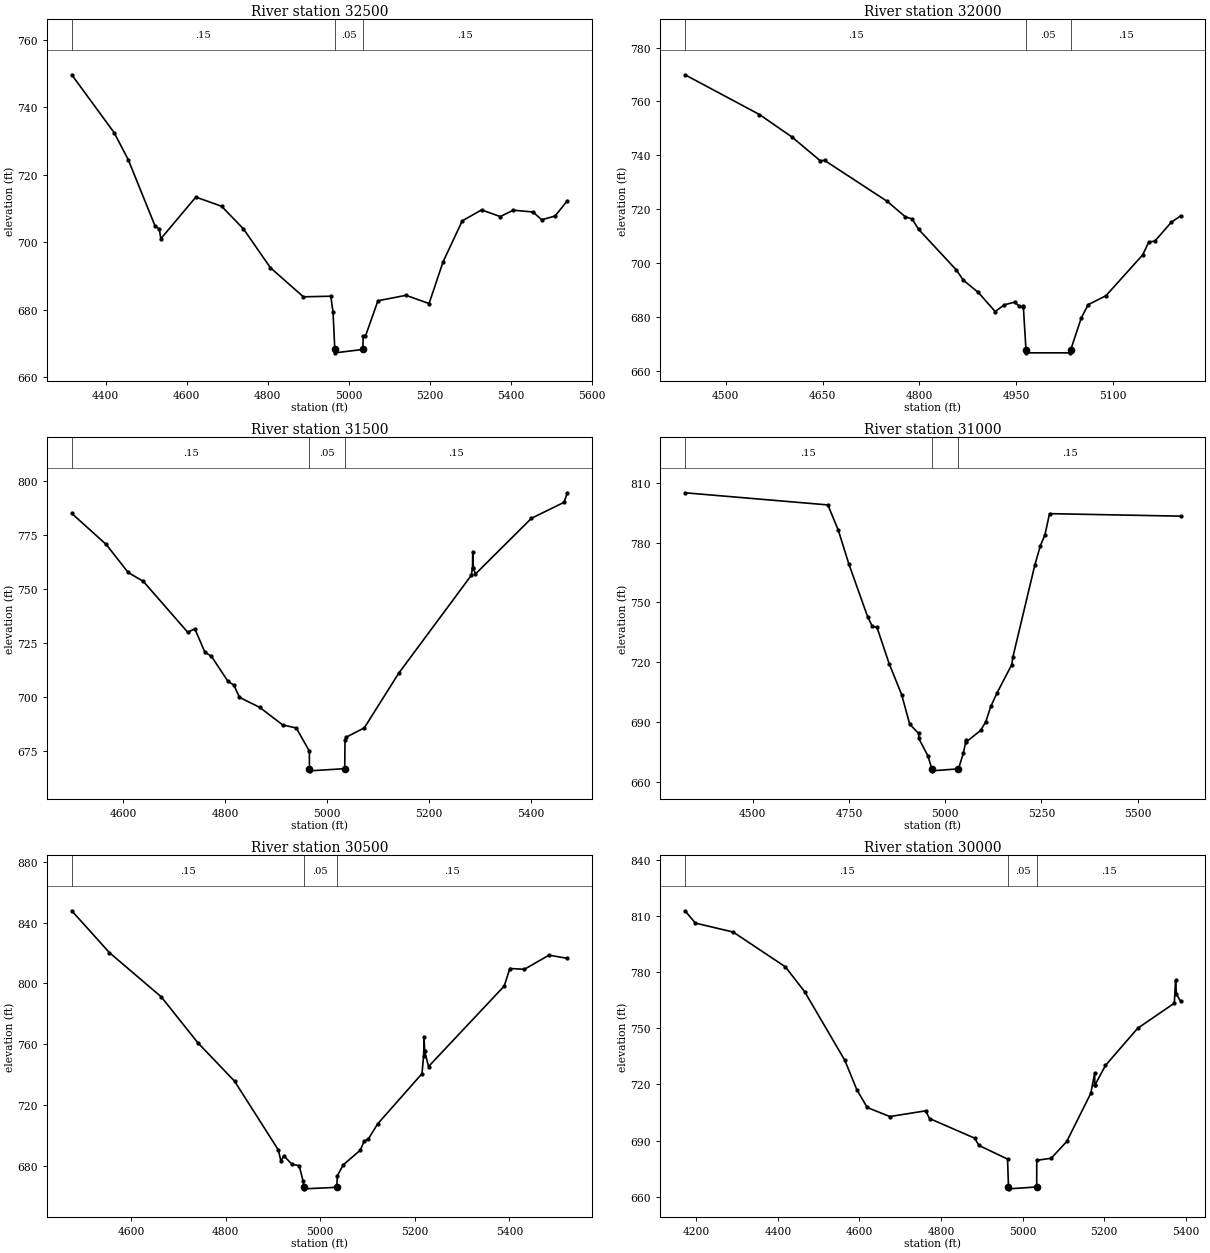
Type RM Length L Ch R = 1,32500,500,500,500
BEGIN DESCRIPTION:
Chauga River 65.0
END DESCRIPTION:
XS GIS Cut Line= 4
      1354042.73      1036816.68      1353403.88      1037060.23
      1353125.52      1037089.30      1352906.99      1036949.68
#Sta/Elev= 30
  4316.3  749.68  4420.9  732.51  4455.8  724.46  4521.4  704.96  4532.3  703.89
  4536.1  701.03  4622.5  713.40  4686.0  710.67  4740.0  703.96  4806.6  692.42
  4887.9  683.81  4955.5  683.99  4961.0  679.25  4965.4  668.19  4965.9  667.19
  5034.6  668.19  5035.4  672.05  5041.0  672.15  5071.8  682.64  5140.9  684.25
  5198.0  681.82  5232.6  694.23  5279.9  706.35  5327.4  709.59  5373.7  707.62
  5405.8  709.51  5454.2  708.97  5475.9  706.68  5508.8  707.77  5539.2  712.32
#Mann=3,-1,0
  4316.3    0.15       0  4965.4    0.05       0  5034.6    0.15       0
Bank Sta=4965.4,5034.6
XS Rating Curve= 0
Exp/Cntr=0.3,0.1

Type RM Length L Ch R = 1,32000,500,500,500
BEGIN DESCRIPTION:
Chauga River 64.0
END DESCRIPTION:
XS GIS Cut Line= 3
      1353547.49      1036618.77      1353007.24      1036778.26
      1352809.84      1036834.29
#Sta/Elev= 30
  4436.7  769.91  4552.1  755.14  4602.5  746.79  4646.4  737.96  4653.0  738.11
  4750.3  722.86  4778.3  717.13  4788.7  716.35  4799.0  712.44  4857.3  697.41
  4868.3  693.56  4891.6  689.01  4917.6  681.92  4931.9  684.44  4947.7  685.41
  4954.1  684.10  4961.0  683.46  4961.2  684.14  4965.4  667.58  4965.9  666.58
  5034.1  666.58  5034.6  667.58  5051.0  679.47  5061.9  684.49  5089.4  687.81
  5146.5  703.02  5155.8  707.80  5165.1  708.08  5190.6  715.07  5205.2  717.47
#Mann=3,-1,0
  4436.7    0.15       0  4965.4    0.05       0  5034.6    0.15       0
Bank Sta=4965.4,5034.6
XS Rating Curve= 0
Exp/Cntr=0.3,0.1

Type RM Length L Ch R = 1,31500,500,500,500
BEGIN DESCRIPTION:
Chauga River 63.0
END DESCRIPTION:
XS GIS Cut Line= 3
      1353624.96      1036474.99      1353141.93      1036342.78
      1352703.69      1036169.64
#Sta/Elev= 30
  4499.2  785.16  4566.8  770.77  4609.9  757.81  4639.6  753.69  4726.6  730.15
  4740.6  731.73  4760.4  720.86  4773.1  719.03  4805.7  707.35  4817.0  705.73
  4828.1  700.02  4867.7  695.39  4913.0  687.22  4939.4  685.85  4965.2  675.13
  4965.4  666.99  4965.9  665.99  5034.6  666.99  5035.1  680.20  5037.1  681.53
  5072.9  685.87  5140.3  711.13  5282.8  756.49  5285.2  760.03  5285.6  767.48
  5286.8  760.10  5290.8  757.08  5400.8  782.91  5464.5  790.27  5471.2  794.71
#Mann=3,-1,0
  4499.2    0.15       0  4965.4    0.05       0  5034.6    0.15       0
Bank Sta=4965.4,5034.6
XS Rating Curve= 0
Exp/Cntr=0.3,0.1

Type RM Length L Ch R = 1,31000,500,500,500
BEGIN DESCRIPTION:
Chauga River 62.0
END DESCRIPTION:
XS GIS Cut Line= 3
      1353877.24      1035821.51      1353203.19      1035871.50
      1352598.29      1035964.46
#Sta/Elev= 30
  4324.1  805.07  4695.3  798.97  4722.4  786.26  4750.0  769.18  4799.2  742.48
  4811.0  737.94  4823.0  737.42  4854.5  719.24  4887.0  703.66  4907.9  688.85
  4931.0  684.18  4931.6  681.64  4955.4  672.82  4965.4  666.37  4965.9  665.37
  5034.6  666.37  5047.2  674.12  5054.8  681.02  5055.1  679.93  5092.5  685.72
  5105.8  690.14  5118.7  697.73  5135.1  704.61  5173.0  718.67  5176.3  722.72
  5233.0  768.67  5247.6  778.58  5259.1  783.73  5271.3  794.58  5612.0  793.33
#Mann=3,-1,0
  4324.1    0.15       0  4965.4    0.05       0  5034.6    0.15       0
Bank Sta=4965.4,5034.6
XS Rating Curve= 0
Exp/Cntr=0.3,0.1

Type RM Length L Ch R = 1,30500,500,500,500
BEGIN DESCRIPTION:
Chauga River 61.0
END DESCRIPTION:
XS GIS Cut Line= 3
      1353425.02      1035325.00      1352919.43      1035469.76
      1352425.03      1035639.42
#Sta/Elev= 30
  4474.1  847.84  4553.8  820.28  4663.5  791.16  4740.5  761.07  4818.5  735.66
  4911.3  690.32  4916.6  682.96  4922.7  686.62  4939.9  680.91  4955.2  680.04
  4963.3  670.23  4965.4  665.76  4965.9  664.76  5034.6  665.76  5036.2  673.43
  5048.4  680.52  5084.5  690.18  5092.8  696.14  5101.5  697.53  5121.2  707.49
  5215.1  740.58  5218.6  752.40  5219.5  764.66  5220.8  755.29  5229.0  745.28
  5389.1  798.28  5401.0  809.83  5431.9  809.33  5483.9  818.62  5522.7  816.51
#Mann=3,-1,0
  4474.1    0.15       0  4965.4    0.05       0  5034.6    0.15       0
Bank Sta=4965.4,5034.6
XS Rating Curve= 0
Exp/Cntr=0.3,0.1

Type RM Length L Ch R = 1,30000,533,533,533
BEGIN DESCRIPTION:
Chauga River 60.0
END DESCRIPTION:
XS GIS Cut Line= 3
      1353532.33      1034761.22      1352741.39      1035004.46
      1352378.73      1035140.69
#Sta/Elev= 30
  4172.5  812.93  4197.9  806.34  4290.6  801.54  4418.6  782.92  4465.5  769.71
  4564.4  732.84  4593.5  717.25  4619.0  707.70  4674.4  702.84  4762.3  705.90
  4771.8  701.78  4882.4  691.28  4893.1  687.36  4963.1  680.08  4965.4  665.16
  4965.9  664.16  5034.6  665.16  5034.7  679.43  5070.2  680.52  5108.2  689.50
  5167.2  715.28  5176.7  726.05  5176.9  719.75  5177.3  719.66  5203.1  730.17
  5282.0  750.05  5371.9  763.48  5375.0  775.80  5377.1  768.33  5387.4  764.47
#Mann=3,-1,0
  4172.5    0.15       0  4965.4    0.05       0  5034.6    0.15       0
Bank Sta=4965.4,5034.6
XS Rating Curve= 0
Exp/Cntr=0.3,0.1

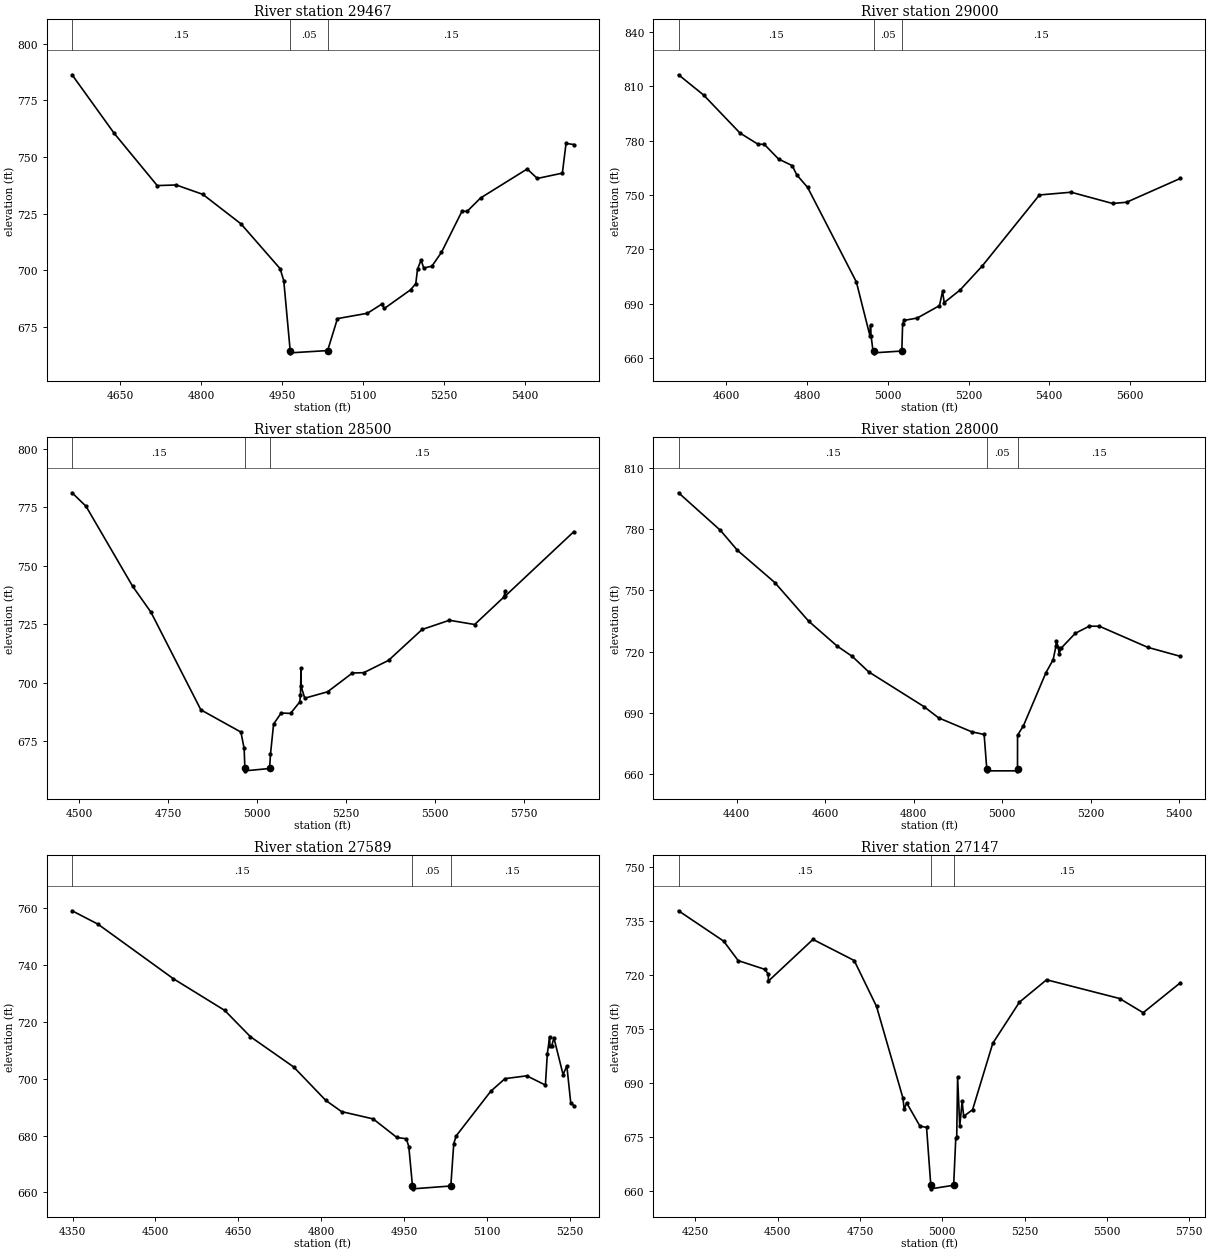
Type RM Length L Ch R = 1,29467,467,467,467
BEGIN DESCRIPTION:
Chauga River 59.0
END DESCRIPTION:
XS GIS Cut Line= 3
      1352683.08      1034095.69      1352576.09      1034521.24
      1352405.62      1034981.60
#Sta/Elev= 30
  4561.2  786.34  4639.4  760.42  4719.0  737.38  4754.1  737.65  4803.4  733.51
  4874.1  720.48  4946.6  700.69  4953.4  695.40  4965.3  664.48  4965.8  663.48
  5034.7  664.48  5052.9  678.61  5108.3  680.96  5135.1  685.02  5139.9  683.10
  5188.3  691.32  5198.0  694.06  5201.3  700.51  5207.8  704.46  5212.8  700.96
  5227.9  701.78  5245.6  707.87  5283.7  726.09  5293.1  725.98  5318.1  731.91
  5404.4  744.71  5423.2  740.53  5469.6  742.88  5476.4  756.01  5490.9  755.52
#Mann=3,-1,0
  4561.2    0.15       0  4965.3    0.05       0  5034.7    0.15       0
Bank Sta=4965.3,5034.7
XS Rating Curve= 0
Exp/Cntr=0.3,0.1

Type RM Length L Ch R = 1,29000,500,500,500
BEGIN DESCRIPTION:
Chauga River 58.0
END DESCRIPTION:
XS GIS Cut Line= 3
      1352075.00      1034074.97      1352114.58      1034591.96
      1352164.44      1035314.94
#Sta/Elev= 30
  4481.5  816.36  4543.8  805.15  4633.7  784.22  4678.7  777.98  4693.8  778.01
  4729.3  769.87  4763.2  766.23  4774.4  761.13  4801.2  754.24  4922.1  702.03
  4955.8  672.21  4957.1  678.13  4958.6  672.09  4963.4  663.92  4965.3  663.92
  4965.8  662.92  5034.7  663.92  5036.7  678.95  5040.4  680.83  5072.9  682.12
  5127.9  688.95  5135.6  696.80  5139.8  690.64  5179.1  697.60  5233.8  710.80
  5375.6  750.04  5454.1  751.55  5556.7  745.35  5591.4  746.01  5724.7  759.17
#Mann=3,-1,0
  4481.5    0.15       0  4965.3    0.05       0  5034.7    0.15       0
Bank Sta=4965.3,5034.7
XS Rating Curve= 0
Exp/Cntr=0.3,0.1

Type RM Length L Ch R = 1,28500,500,500,500
BEGIN DESCRIPTION:
Chauga River 57.0
END DESCRIPTION:
XS GIS Cut Line= 3
      1351874.98      1034225.03      1351624.68      1034680.82
      1351224.99      1035475.02
#Sta/Elev= 30
  4480.0  781.11  4519.1  775.36  4649.7  741.26  4701.5  730.10  4841.7  688.38
  4954.1  678.89  4963.2  671.89  4965.3  663.33  4965.8  662.33  5034.7  663.33
  5037.2  669.43  5045.9  682.33  5067.3  687.03  5093.5  686.87  5119.4  691.76
  5121.4  694.74  5122.9  706.08  5123.3  698.38  5133.4  693.36  5197.6  696.10
  5267.2  704.11  5299.3  704.27  5368.6  709.51  5463.0  722.72  5539.6  726.65
  5610.5  724.84  5693.6  736.71  5695.1  739.03  5695.2  736.84  5889.1  764.51
#Mann=3,-1,0
  4480.0    0.15       0  4965.3    0.05       0  5034.7    0.15       0
Bank Sta=4965.3,5034.7
XS Rating Curve= 0
Exp/Cntr=0.3,0.1

Type RM Length L Ch R = 1,28000,411,411,411
BEGIN DESCRIPTION:
Chauga River 56.0
END DESCRIPTION:
XS GIS Cut Line= 3
      1351825.01      1034074.99      1351196.28      1034447.89
      1350843.04      1034640.85
#Sta/Elev= 30
  4269.0  797.82  4363.4  779.48  4402.1  769.66  4486.4  753.91  4562.9  735.00
  4627.2  722.82  4661.5  717.74  4698.4  710.21  4823.1  693.22  4856.5  687.67
  4931.1  680.87  4959.3  679.54  4965.3  662.75  4965.8  661.75  5034.2  661.75
  5034.7  662.75  5034.8  679.17  5048.2  683.86  5099.1  709.86  5115.1  716.09
  5121.6  722.71  5122.1  725.42  5127.6  721.81  5128.2  718.97  5134.0  721.96
  5165.3  729.06  5196.9  732.55  5219.9  732.49  5328.9  722.19  5402.5  717.79
#Mann=3,-1,0
  4269.0    0.15       0  4965.3    0.05       0  5034.7    0.15       0
Bank Sta=4965.3,5034.7
XS Rating Curve= 0
Exp/Cntr=0.3,0.1

Type RM Length L Ch R = 1,27589,442,442,442
BEGIN DESCRIPTION:
Chauga River 55.0
END DESCRIPTION:
XS GIS Cut Line= 3
      1351661.21      1033859.09      1351044.85      1034067.99
      1350804.06      1034158.94
#Sta/Elev= 30
  4349.2  758.97  4395.9  754.29  4532.6  735.09  4625.5  723.96  4672.1  714.71
  4750.1  704.12  4808.2  692.38  4836.9  688.41  4894.2  685.84  4937.1  679.31
  4954.2  678.87  4958.7  676.06  4965.3  662.27  4965.8  661.27  5034.7  662.27
  5040.0  677.11  5044.3  679.85  5107.0  695.56  5132.8  699.99  5172.2  700.98
  5205.9  697.73  5209.4  708.79  5213.6  714.72  5214.0  711.51  5217.1  711.33
  5221.3  714.33  5237.9  701.39  5244.7  704.46  5251.8  691.43  5257.4  690.54
#Mann=3,-1,0
  4349.2    0.15       0  4965.3    0.05       0  5034.7    0.15       0
Bank Sta=4965.3,5034.7
XS Rating Curve= 0
Exp/Cntr=0.3,0.1

Type RM Length L Ch R = 1,27147,647,647,647
BEGIN DESCRIPTION:
Chauga River 54.0
END DESCRIPTION:
XS GIS Cut Line= 3
      1351769.14      1033619.20      1350968.74      1033632.01
      1350278.62      1033846.89
#Sta/Elev= 30
  4199.5  737.72  4336.6  729.29  4380.5  723.90  4460.9  721.48  4471.9  720.17
  4472.4  718.21  4607.6  729.77  4732.8  723.92  4800.5  711.18  4880.6  685.79
  4884.5  682.66  4892.0  684.42  4932.3  677.96  4952.4  677.61  4965.3  661.55
  4965.8  660.55  5034.7  661.55  5041.1  674.55  5044.0  674.89  5046.7  691.57
  5053.2  677.87  5060.4  684.86  5065.1  680.67  5092.2  682.53  5153.5  700.96
  5234.5  712.37  5316.8  718.57  5538.5  713.37  5610.0  709.43  5722.8  717.74
#Mann=3,-1,0
  4199.5    0.15       0  4965.3    0.05       0  5034.7    0.15       0
Bank Sta=4965.3,5034.7
XS Rating Curve= 0
Exp/Cntr=0.3,0.1

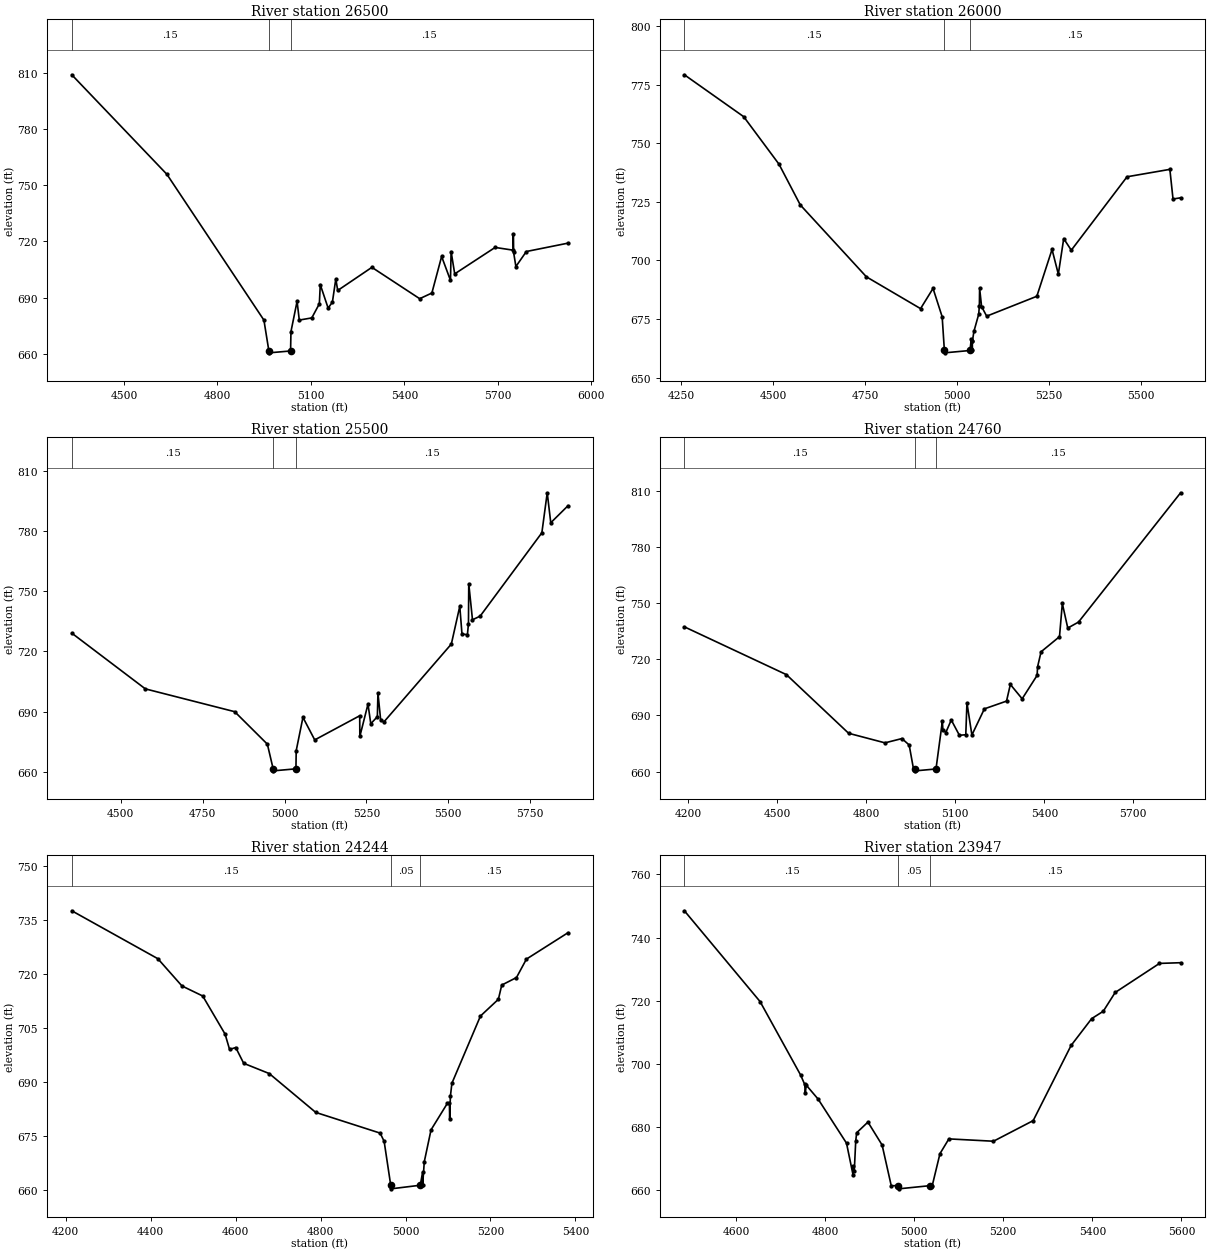
Type RM Length L Ch R = 1,26500,500,500,500
BEGIN DESCRIPTION:
Chauga River 53.0
END DESCRIPTION:
XS GIS Cut Line= 4
      1351486.85      1032911.28      1350825.77      1033002.20
      1350533.65      1033017.53      1349932.54      1032820.19
#Sta/Elev= 30
  4332.7  808.93  4637.9  755.82  4949.3  678.00  4965.2  661.55  4965.7  660.55
  5034.8  661.55  5036.1  671.91  5055.7  688.03  5062.8  678.04  5102.9  679.19
  5127.2  686.73  5130.1  696.97  5155.4  684.39  5169.1  687.65  5180.0  700.01
  5186.1  693.83  5295.8  706.17  5449.2  689.44  5488.3  692.47  5519.6  711.97
  5548.0  699.22  5550.0  714.60  5561.6  702.69  5691.3  716.80  5749.4  715.33
  5749.6  724.12  5750.4  714.40  5757.9  706.60  5791.5  714.62  5925.2  719.09
#Mann=3,-1,0
  4332.7    0.15       0  4965.2    0.05       0  5034.8    0.15       0
Bank Sta=4965.2,5034.8
XS Rating Curve= 0
Exp/Cntr=0.3,0.1

Type RM Length L Ch R = 1,26000,500,500,500
BEGIN DESCRIPTION:
Chauga River 52.0
END DESCRIPTION:
XS GIS Cut Line= 3
      1351400.57      1032303.46      1350691.85      1032520.48
      1350106.44      1032680.92
#Sta/Elev= 30
  4258.8  779.17  4420.0  761.29  4515.9  741.02  4573.7  723.65  4753.4  692.97
  4900.5  679.41  4934.4  688.03  4959.2  675.93  4965.2  661.55  4965.7  660.55
  5034.8  661.55  5038.1  666.31  5040.5  665.55  5041.0  661.55  5041.3  665.47
  5045.4  669.67  5058.4  676.99  5060.3  680.62  5060.9  688.14  5066.3  680.29
  5080.1  676.19  5216.4  684.68  5257.7  704.65  5274.8  694.12  5289.4  709.28
  5310.0  704.33  5461.5  735.66  5577.8  738.82  5586.4  726.17  5607.0  726.69
#Mann=3,-1,0
  4258.8    0.15       0  4965.2    0.05       0  5034.8    0.15       0
Bank Sta=4965.2,5034.8
XS Rating Curve= 0
Exp/Cntr=0.3,0.1

Type RM Length L Ch R = 1,25500,740,740,740
BEGIN DESCRIPTION:
Chauga River 51.0
END DESCRIPTION:
XS GIS Cut Line= 3
      1351175.85      1031871.21      1350548.66      1032041.50
      1349728.95      1032320.55
#Sta/Elev= 30
  4350.1  729.11  4574.8  701.32  4847.7  689.95  4947.5  673.76  4965.2  661.46
  4965.7  660.46  5034.8  661.46  5035.6  670.51  5056.2  687.11  5092.2  675.88
  5229.6  687.92  5230.0  677.62  5254.9  693.74  5263.4  683.95  5283.5  687.45
  5285.3  699.30  5293.6  685.83  5303.5  684.83  5509.5  723.66  5535.3  742.49
  5542.0  728.65  5558.6  728.36  5561.8  733.79  5562.7  753.77  5574.1  735.77
  5597.5  737.58  5786.0  779.14  5802.4  799.08  5813.2  784.13  5865.9  792.63
#Mann=3,-1,0
  4350.1    0.15       0  4965.2    0.05       0  5034.8    0.15       0
Bank Sta=4965.2,5034.8
XS Rating Curve= 0
Exp/Cntr=0.3,0.1

Type RM Length L Ch R = 1,24760,516,516,516
BEGIN DESCRIPTION:
Chauga River 50.0
END DESCRIPTION:
XS GIS Cut Line= 4
      1350835.73      1031642.52      1350425.88      1031403.45
      1350098.25      1031489.39      1349363.43      1031934.67
#Sta/Elev= 30
  4186.8  737.42  4530.7  711.84  4740.3  680.47  4862.9  675.34  4920.0  677.64
  4944.4  674.19  4959.0  661.37  4965.2  661.37  4965.7  660.37  5034.8  661.37
  5056.2  686.78  5058.0  682.48  5067.9  680.88  5086.3  687.58  5113.7  679.38
  5135.2  679.70  5139.1  696.73  5155.8  679.55  5197.9  693.54  5272.5  697.68
  5285.4  706.59  5325.2  698.92  5375.6  711.45  5377.1  715.99  5389.0  724.08
  5451.0  732.15  5460.6  749.92  5478.9  736.76  5515.1  739.97  5859.2  809.15
#Mann=3,-1,0
  4186.8    0.15       0  4965.2    0.05       0  5034.8    0.15       0
Bank Sta=4965.2,5034.8
XS Rating Curve= 0
Exp/Cntr=0.3,0.1

Type RM Length L Ch R = 1,24244,297,297,297
BEGIN DESCRIPTION:
Chauga River 49.0
END DESCRIPTION:
XS GIS Cut Line= 3
      1350831.91      1031615.95      1350190.04      1031163.17
      1349845.31      1030997.43
#Sta/Elev= 30
  4214.5  737.46  4417.1  724.17  4473.8  716.62  4522.7  713.83  4575.4  703.25
  4585.9  699.01  4600.4  699.55  4619.1  695.17  4679.3  692.33  4788.7  681.56
  4940.3  675.82  4949.7  673.54  4965.2  661.37  4965.7  660.37  5034.8  661.37
  5040.1  664.90  5040.3  661.37  5044.2  667.89  5060.1  676.73  5098.5  684.07
  5103.3  684.24  5104.0  679.80  5105.6  685.99  5109.2  689.64  5176.4  708.28
  5218.6  712.92  5226.5  716.86  5261.2  718.95  5284.6  724.06  5382.5  731.38
#Mann=3,-1,0
  4214.5    0.15       0  4965.2    0.05       0  5034.8    0.15       0
Bank Sta=4965.2,5034.8
XS Rating Curve= 0
Exp/Cntr=0.3,0.1

Type RM Length L Ch R = 1,23947,447,447,447
BEGIN DESCRIPTION:
Chauga River 48.0
END DESCRIPTION:
XS GIS Cut Line= 3
      1350911.62      1030850.57      1350409.07      1030966.32
      1349811.19      1030982.24
#Sta/Elev= 30
  4484.3  748.50  4654.2  719.72  4745.2  696.44  4754.3  693.48  4755.8  690.86
  4757.8  693.24  4784.5  688.81  4848.2  674.85  4862.8  664.85  4863.5  667.49
  4865.7  666.17  4868.9  675.52  4871.0  678.14  4896.3  681.53  4928.1  674.26
  4948.6  661.37  4964.9  661.37  4965.4  660.37  5035.1  661.37  5040.6  661.37
  5058.0  671.53  5078.0  676.20  5178.1  675.46  5267.2  681.99  5352.3  705.81
  5398.5  714.32  5424.5  716.65  5451.2  722.60  5550.7  731.82  5598.1  732.04
#Mann=3,-1,0
  4484.3    0.15       0  4964.9    0.05       0  5035.1    0.15       0
Bank Sta=4964.9,5035.1
XS Rating Curve= 0
Exp/Cntr=0.3,0.1

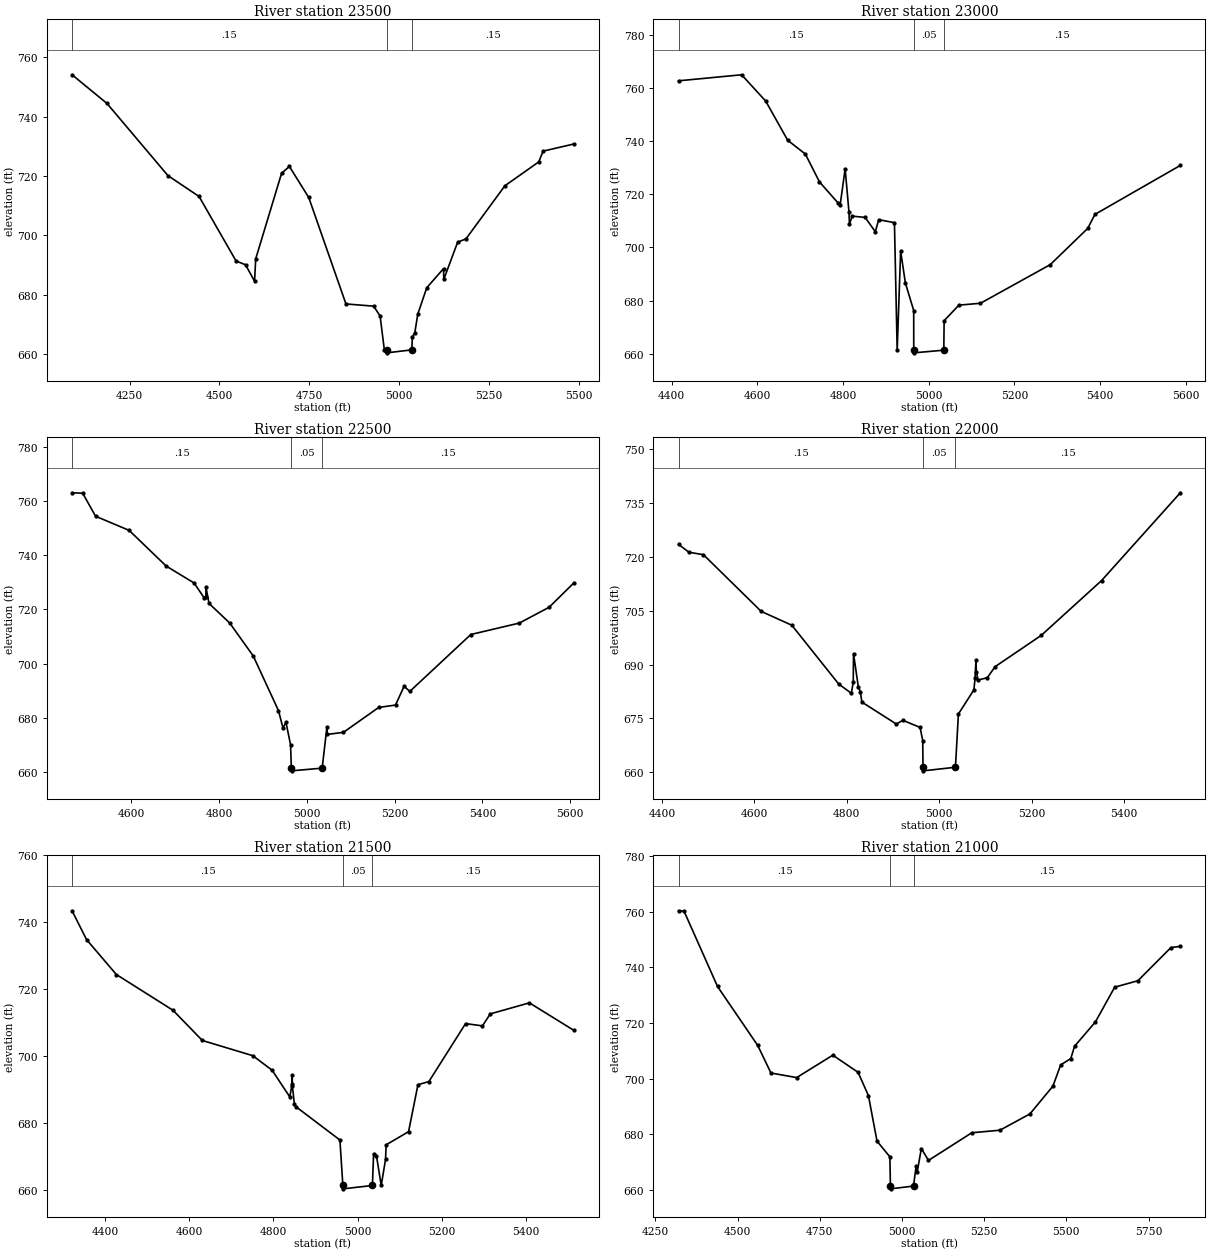
Type RM Length L Ch R = 1,23500,500,500,500
BEGIN DESCRIPTION:
Chauga River 47.0
END DESCRIPTION:
XS GIS Cut Line= 3
      1351025.42      1030357.28      1350154.83      1030621.50
      1349773.95      1030923.06
#Sta/Elev= 30
  4090.2  754.09  4187.2  744.44  4356.8  720.11  4443.4  713.07  4546.4  691.31
  4572.7  690.05  4597.8  684.50  4600.9  692.04  4672.8  720.85  4694.5  723.21
  4748.4  712.74  4851.9  676.85  4928.8  676.11  4946.9  672.80  4958.7  661.37
  4964.9  661.37  4965.4  660.37  5035.1  661.37  5036.7  665.79  5043.3  667.03
  5051.7  673.39  5076.6  682.30  5123.3  688.75  5124.1  685.17  5162.6  697.67
  5185.7  698.78  5294.0  716.68  5388.2  724.73  5400.2  728.35  5485.8  730.76
#Mann=3,-1,0
  4090.2    0.15       0  4964.9    0.05       0  5035.1    0.15       0
Bank Sta=4964.9,5035.1
XS Rating Curve= 0
Exp/Cntr=0.3,0.1

Type RM Length L Ch R = 1,23000,500,500,500
BEGIN DESCRIPTION:
Chauga River 46.0
END DESCRIPTION:
XS GIS Cut Line= 3
      1350004.68      1029769.10      1349795.70      1030314.75
      1349712.49      1030896.12
#Sta/Elev= 30
  4415.7  762.64  4563.0  764.91  4619.2  755.02  4670.5  740.31  4711.9  735.08
  4744.7  724.64  4789.1  716.56  4793.2  716.09  4804.7  729.59  4813.7  713.14
  4814.7  708.85  4821.4  711.77  4851.3  711.28  4875.2  705.91  4883.0  710.44
  4919.8  709.31  4926.2  661.37  4934.3  698.64  4945.3  686.66  4964.8  676.27
  4964.9  661.37  4965.4  660.37  5035.1  661.37  5035.8  672.45  5070.3  678.30
  5120.7  679.01  5283.6  693.53  5371.1  707.16  5387.9  712.42  5587.3  730.83
#Mann=3,-1,0
  4415.7    0.15       0  4964.9    0.05       0  5035.1    0.15       0
Bank Sta=4964.9,5035.1
XS Rating Curve= 0
Exp/Cntr=0.3,0.1

Type RM Length L Ch R = 1,22500,500,500,500
BEGIN DESCRIPTION:
Chauga River 45.0
END DESCRIPTION:
XS GIS Cut Line= 3
      1349025.66      1029985.39      1349343.20      1030415.22
      1349674.97      1030924.96
#Sta/Elev= 30
  4465.6  763.06  4489.8  762.90  4519.1  754.40  4595.6  749.17  4679.9  736.00
  4743.4  729.74  4766.2  724.31  4770.3  724.73  4770.5  728.16  4777.5  722.19
  4824.6  714.95  4878.2  702.78  4935.6  682.61  4945.8  676.24  4952.7  678.26
  4963.1  670.01  4964.9  661.37  4965.4  660.37  5035.1  661.37  5045.9  676.53
  5046.2  673.81  5083.5  674.59  5163.8  683.78  5202.1  684.66  5221.6  691.59
  5234.7  689.71  5373.6  710.72  5484.0  714.94  5551.7  720.76  5608.2  729.77
#Mann=3,-1,0
  4465.6    0.15       0  4964.9    0.05       0  5035.1    0.15       0
Bank Sta=4964.9,5035.1
XS Rating Curve= 0
Exp/Cntr=0.3,0.1

Type RM Length L Ch R = 1,22000,500,500,500
BEGIN DESCRIPTION:
Chauga River 44.0
END DESCRIPTION:
XS GIS Cut Line= 3
      1348839.30      1030227.50      1348992.15      1030770.50
      1349125.00      1031275.00
#Sta/Elev= 30
  4435.9  723.51  4458.3  721.32  4489.8  720.63  4614.8  704.82  4681.1  700.96
  4782.5  684.57  4809.9  681.98  4814.0  685.17  4814.5  693.06  4824.9  683.81
  4829.2  682.46  4832.6  679.54  4907.1  673.42  4921.4  674.46  4958.6  672.47
  4964.3  668.80  4964.9  661.37  4965.4  660.37  5035.1  661.37  5041.5  676.22
  5075.0  682.94  5077.5  686.13  5079.5  691.22  5080.2  688.02  5084.2  685.67
  5104.1  686.35  5120.9  689.41  5220.9  698.15  5351.3  713.42  5521.7  737.89
#Mann=3,-1,0
  4435.9    0.15       0  4964.9    0.05       0  5035.1    0.15       0
Bank Sta=4964.9,5035.1
XS Rating Curve= 0
Exp/Cntr=0.3,0.1

Type RM Length L Ch R = 1,21500,500,500,500
BEGIN DESCRIPTION:
Chauga River 43.0
END DESCRIPTION:
XS GIS Cut Line= 3
      1348749.41      1030029.82      1348602.01      1030692.43
      1348425.00      1031174.99
#Sta/Elev= 30
  4321.2  743.47  4355.6  734.86  4426.5  724.42  4561.1  713.74  4630.8  704.71
  4750.9  700.16  4796.8  695.81  4838.7  687.85  4844.1  691.57  4844.5  694.26
  4844.9  691.00  4849.8  685.65  4853.8  684.87  4957.9  674.96  4964.9  661.37
  4965.4  660.37  5035.1  661.37  5038.0  670.89  5044.8  670.25  5056.1  661.37
  5066.4  669.22  5067.7  673.52  5121.1  677.46  5143.4  691.49  5169.4  692.43
  5256.6  709.76  5296.7  709.07  5315.4  712.66  5408.3  715.95  5514.0  707.73
#Mann=3,-1,0
  4321.2    0.15       0  4964.9    0.05       0  5035.1    0.15       0
Bank Sta=4964.9,5035.1
XS Rating Curve= 0
Exp/Cntr=0.3,0.1

Type RM Length L Ch R = 1,21000,396,396,396
BEGIN DESCRIPTION:
Chauga River 42.0
END DESCRIPTION:
XS GIS Cut Line= 3
      1348577.89      1029985.41      1348140.83      1030505.96
      1347629.22      1031180.74
#Sta/Elev= 30
  4320.3  760.35  4336.9  760.25  4438.9  733.13  4561.3  711.91  4601.4  702.02
  4679.6  700.37  4789.7  708.43  4866.5  702.26  4898.0  693.88  4924.1  677.52
  4963.2  671.89  4964.9  661.37  4965.4  660.37  5035.1  661.37  5043.1  668.64
  5046.3  666.38  5058.9  674.87  5080.7  670.59  5212.3  680.53  5298.0  681.45
  5389.4  687.32  5459.2  697.30  5482.7  704.90  5513.6  707.22  5525.0  711.63
  5588.5  720.39  5647.1  732.88  5717.7  735.20  5818.3  747.13  5846.8  747.55
#Mann=3,-1,0
  4320.3    0.15       0  4964.9    0.05       0  5035.1    0.15       0
Bank Sta=4964.9,5035.1
XS Rating Curve= 0
Exp/Cntr=0.3,0.1