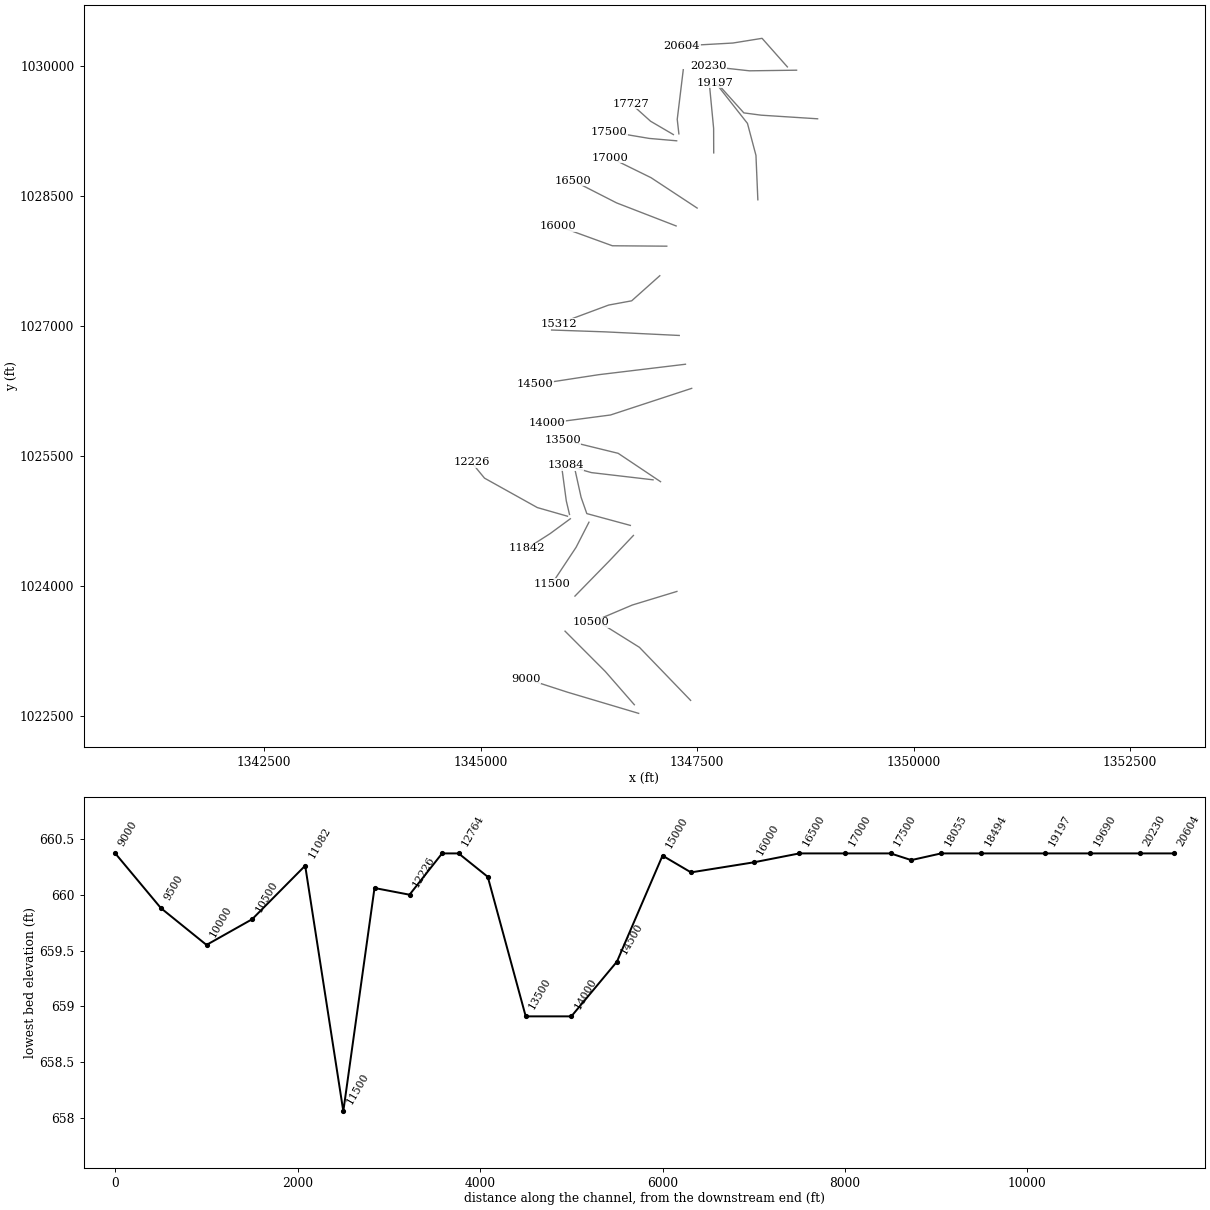
HEC-RAS study Chauga River.prj: Chauga River Limited Detail Study

--- Chauga River.g01 (geometry) --- (continued)

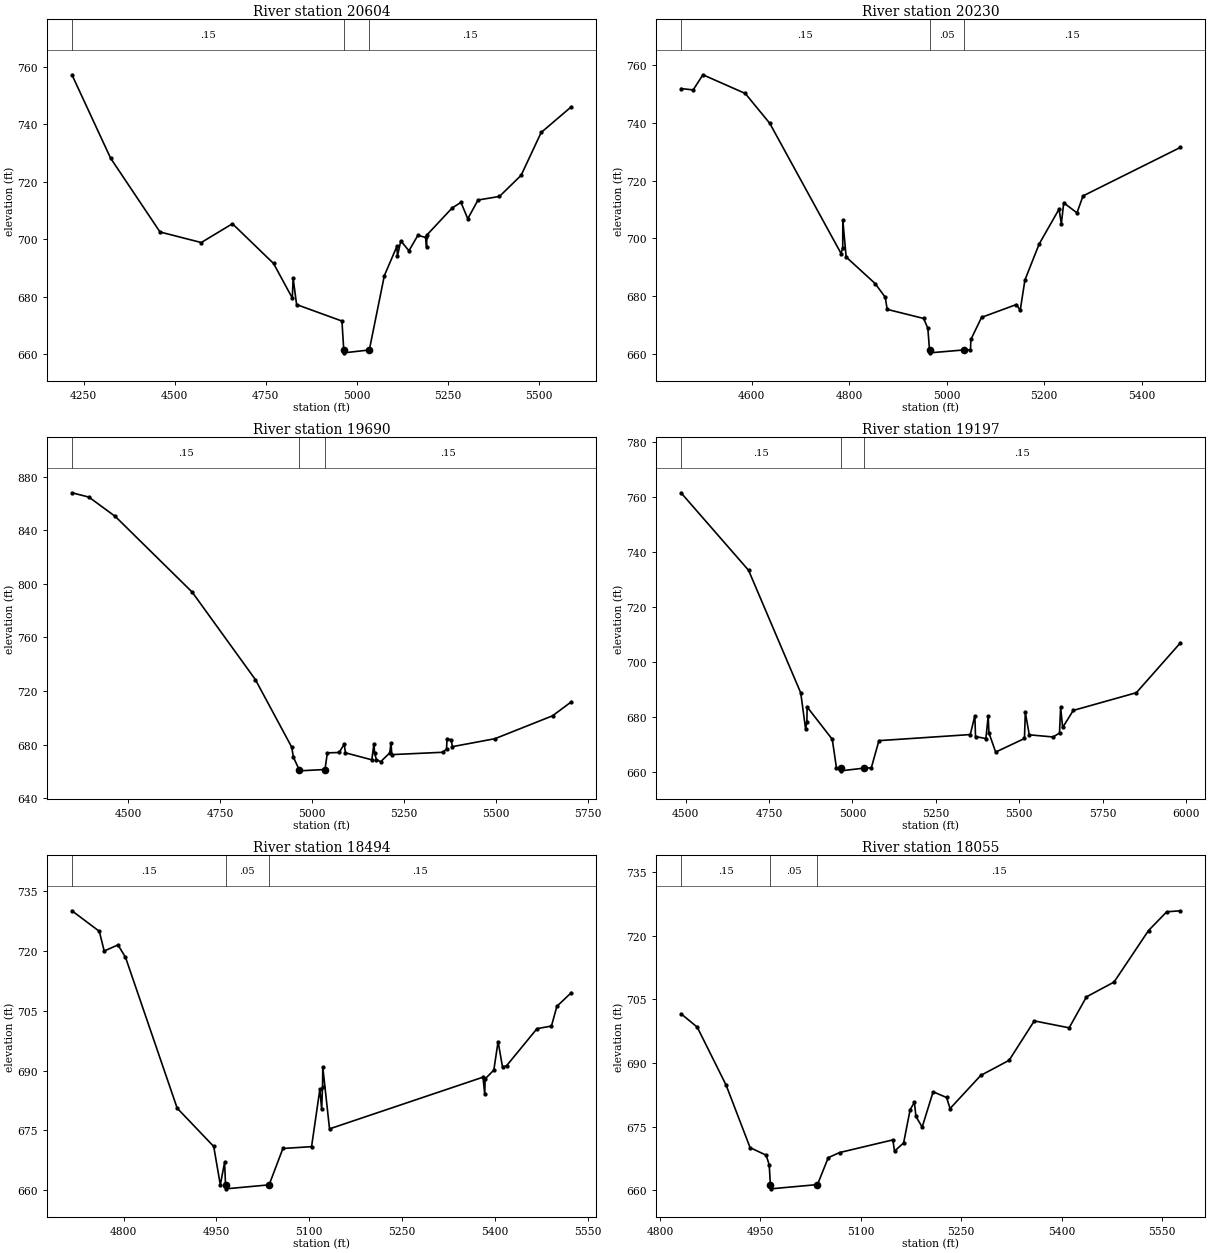
Type RM Length L Ch R = 1,20604,374,374,374
BEGIN DESCRIPTION:
Chauga River 41.0
END DESCRIPTION:
XS GIS Cut Line= 4
      1348542.25      1029994.49      1348250.05      1030324.64
      1347913.48      1030270.40      1347324.20      1030237.36
#Sta/Elev= 30
  4218.2  757.32  4324.3  728.26  4460.1  702.51  4573.4  698.83  4659.1  705.38
  4772.0  691.53  4823.6  679.47  4825.8  686.41  4835.3  677.20  4959.9  671.45
  4964.9  661.37  4965.4  660.37  5035.1  661.37  5076.4  687.28  5110.9  697.51
  5112.3  694.03  5121.6  699.44  5143.9  695.95  5168.4  701.32  5189.8  700.62
  5192.4  697.24  5193.3  701.46  5262.4  710.85  5286.8  712.84  5305.6  707.12
  5333.7  713.65  5392.6  714.90  5452.1  722.26  5507.2  737.20  5590.2  746.18
#Mann=3,-1,0
  4218.2    0.15       0  4964.9    0.05       0  5035.1    0.15       0
Bank Sta=4964.9,5035.1
XS Rating Curve= 0
Exp/Cntr=0.3,0.1

Type RM Length L Ch R = 1,20230,540,540,540
BEGIN DESCRIPTION:
Chauga River 40.0
END DESCRIPTION:
XS GIS Cut Line= 3
      1348648.53      1029956.56      1348103.97      1029949.33
      1347627.69      1030002.10
#Sta/Elev= 30
  4455.4  751.87  4480.3  751.40  4500.3  756.64  4587.1  750.17  4637.3  739.84
  4783.5  694.76  4786.9  696.84  4787.1  706.32  4793.9  693.55  4853.4  684.35
  4874.1  679.60  4878.0  675.42  4952.8  672.27  4961.4  668.85  4964.8  661.37
  4965.3  660.37  5035.2  661.37  5048.8  661.37  5049.6  664.99  5071.5  672.65
  5143.0  677.10  5150.7  675.06  5160.4  685.59  5189.4  697.98  5230.3  710.12
  5235.1  705.06  5239.9  712.31  5267.1  708.84  5279.5  714.70  5479.2  731.50
#Mann=3,-1,0
  4455.4    0.15       0  4964.8    0.05       0  5035.2    0.15       0
Bank Sta=4964.8,5035.2
XS Rating Curve= 0
Exp/Cntr=0.3,0.1

Type RM Length L Ch R = 1,19690,493,493,493
BEGIN DESCRIPTION:
Chauga River 39.0
END DESCRIPTION:
XS GIS Cut Line= 4
      1348891.36      1029394.96      1348239.40      1029436.77
      1348039.55      1029463.26      1347702.61      1029838.08
#Sta/Elev= 30
  4346.7  868.07  4392.8  864.85  4464.6  850.40  4674.0  793.83  4845.8  728.52
  4944.7  678.04  4949.3  670.49  4964.8  661.37  4965.3  660.37  5035.2  661.37
  5041.6  673.79  5073.6  674.08  5087.5  680.26  5090.9  673.83  5162.6  668.60
  5168.4  680.67  5170.2  673.68  5175.0  668.84  5186.6  667.16  5211.3  673.73
  5214.8  681.19  5217.0  672.49  5356.0  674.24  5365.9  676.70  5367.3  684.27
  5378.8  683.49  5381.7  678.42  5497.4  684.36  5654.3  701.47  5705.6  711.94
#Mann=3,-1,0
  4346.7    0.15       0  4964.8    0.05       0  5035.2    0.15       0
Bank Sta=4964.8,5035.2
XS Rating Curve= 0
Exp/Cntr=0.3,0.1

Type RM Length L Ch R = 1,19197,703,703,703
BEGIN DESCRIPTION:
Chauga River 38.0
END DESCRIPTION:
XS GIS Cut Line= 4
      1348201.30      1028459.04      1348179.45      1028972.37
      1348081.42      1029341.63      1347710.53      1029814.22
#Sta/Elev= 30
  4486.2  761.39  4688.6  733.24  4845.0  688.68  4859.6  675.49  4863.3  678.20
  4864.2  683.56  4939.4  671.84  4952.1  661.37  4964.8  661.37  4965.3  660.37
  5035.2  661.37  5056.4  661.44  5079.3  671.34  5353.0  673.55  5366.7  680.39
  5368.7  672.84  5399.8  672.09  5406.7  680.35  5408.9  674.16  5429.1  667.18
  5515.4  672.12  5517.9  681.61  5529.8  673.46  5601.2  672.67  5620.4  674.10
  5623.8  683.48  5629.8  676.12  5661.7  682.32  5850.7  688.76  5982.8  706.88
#Mann=3,-1,0
  4486.2    0.15       0  4964.8    0.05       0  5035.2    0.15       0
Bank Sta=4964.8,5035.2
XS Rating Curve= 0
Exp/Cntr=0.3,0.1

Type RM Length L Ch R = 1,18494,439,439,439
BEGIN DESCRIPTION:
Chauga River 37.0
END DESCRIPTION:
XS GIS Cut Line= 3
      1347691.60      1029000.97      1347690.64      1029284.27
      1347640.79      1029805.39
#Sta/Elev= 30
  4716.7  730.02  4760.9  724.88  4768.8  719.94  4791.0  721.47  4803.2  718.37
  4886.7  680.57  4945.7  670.99  4956.4  661.37  4963.3  667.01  4964.8  661.37
  4965.3  660.37  5035.2  661.37  5057.5  670.48  5103.8  670.94  5117.2  685.33
  5120.1  680.28  5121.5  685.96  5121.9  690.90  5132.8  675.39  5380.7  688.34
  5383.6  684.02  5384.1  687.90  5398.2  690.11  5405.1  697.25  5412.3  690.84
  5418.9  691.22  5468.0  700.50  5491.3  701.14  5500.1  706.09  5523.5  709.52
#Mann=3,-1,0
  4716.7    0.15       0  4964.8    0.05       0  5035.2    0.15       0
Bank Sta=4964.8,5035.2
XS Rating Curve= 0
Exp/Cntr=0.3,0.1

Type RM Length L Ch R = 1,18055,328,328,328
BEGIN DESCRIPTION:
Chauga River 36.0
END DESCRIPTION:
XS GIS Cut Line= 3
      1347289.39      1029221.10      1347270.47      1029388.73
      1347340.19      1029962.01
#Sta/Elev= 30
  4831.3  701.58  4855.5  698.44  4898.6  684.81  4934.5  670.07  4958.5  668.29
  4963.1  666.00  4964.8  661.37  4965.3  660.37  5035.2  661.37  5051.3  667.71
  5068.2  668.91  5147.8  671.89  5150.3  669.24  5163.9  671.18  5173.6  678.99
  5180.0  680.75  5182.3  677.41  5191.6  674.90  5208.0  683.22  5228.0  681.87
  5233.3  679.27  5279.1  687.06  5321.5  690.62  5359.1  699.90  5411.2  698.27
  5437.1  705.56  5478.3  709.04  5529.8  721.17  5557.0  725.58  5577.5  725.82
#Mann=3,-1,0
  4831.3    0.15       0  4964.8    0.05       0  5035.2    0.15       0
Bank Sta=4964.8,5035.2
XS Rating Curve= 0
Exp/Cntr=0.3,0.1

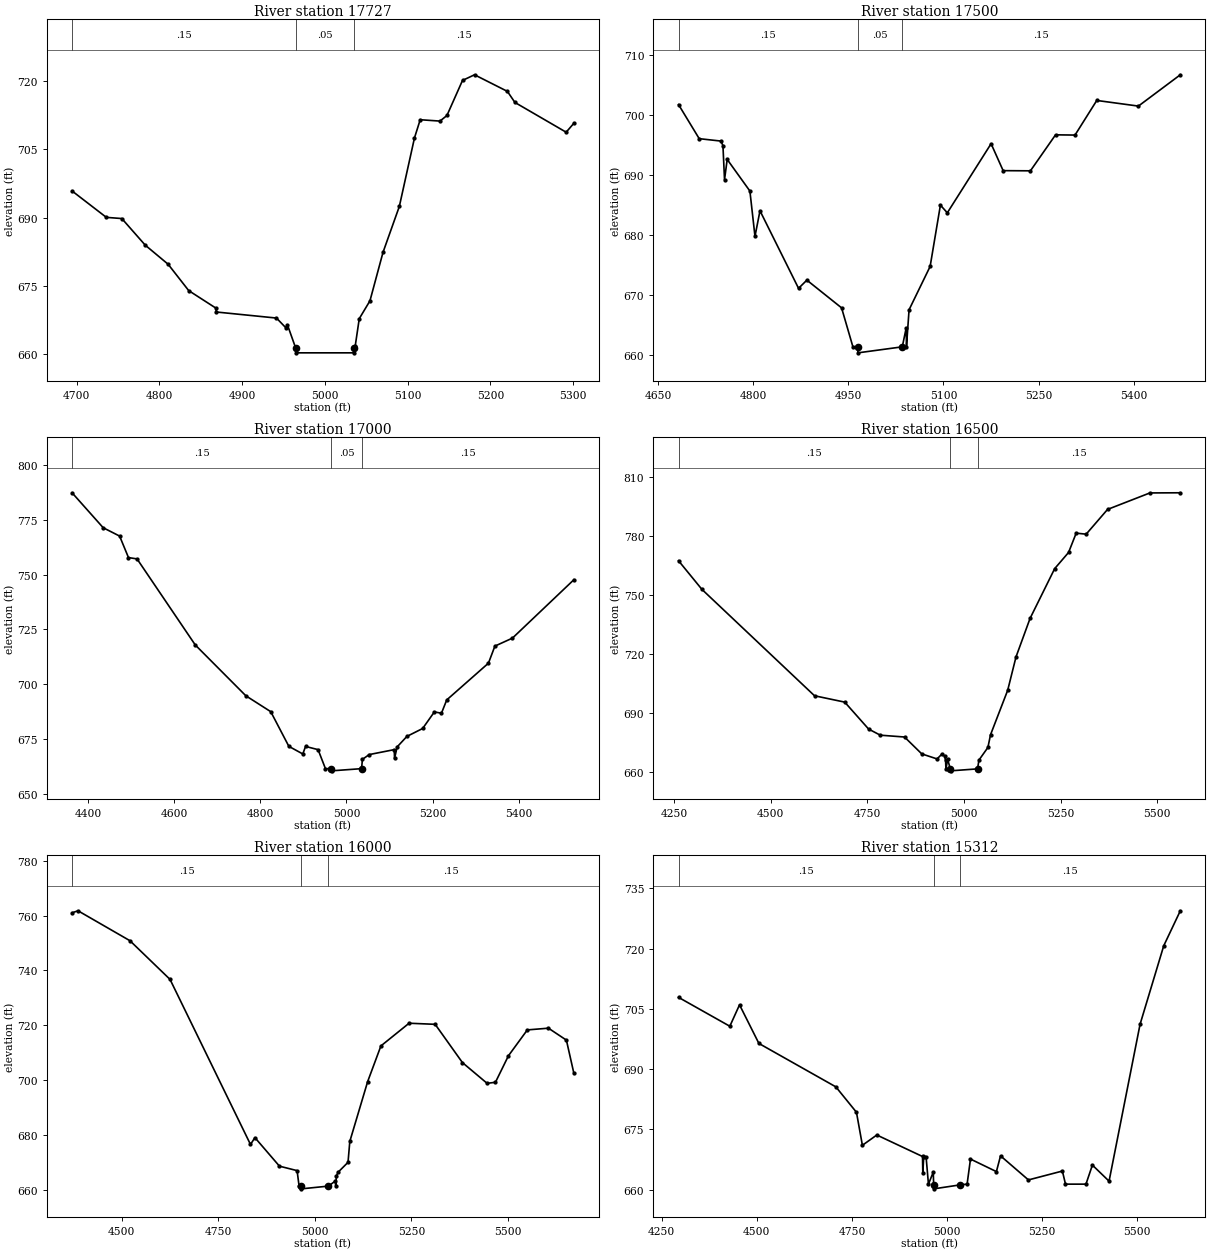
Type RM Length L Ch R = 1,17727,227,227,227
BEGIN DESCRIPTION:
Chauga River 35.5
END DESCRIPTION:
XS GIS Cut Line= 3
      1347225.91      1029212.64      1346962.36      1029366.95
      1346739.01      1029568.28
#Sta/Elev= 30
  4694.6  695.82  4736.0  690.03  4754.7  689.77  4783.0  683.93  4810.6  679.75
  4835.5  673.96  4868.5  670.10  4868.7  669.27  4941.5  667.94  4952.6  665.85
  4954.8  666.42  4964.8  661.31  4965.3  660.31  5034.7  660.31  5035.2  661.31
  5036.7  661.92  5041.5  667.81  5054.4  671.72  5070.2  682.37  5089.9  692.43
  5108.2  707.47  5115.1  711.45  5139.0  711.15  5147.4  712.38  5166.2  720.07
  5180.7  721.31  5220.4  717.67  5229.5  715.24  5291.4  708.71  5300.7  710.67
#Mann=3,-1,0
  4694.6    0.15       0  4964.8    0.05       0  5035.2    0.15       0
Bank Sta=4964.8,5035.2
XS Rating Curve= 0
Exp/Cntr=0.3,0.1

Type RM Length L Ch R = 1,17500,500,500,500
BEGIN DESCRIPTION:
Chauga River 35.0
END DESCRIPTION:
XS GIS Cut Line= 3
      1347263.98      1029140.68      1346947.67      1029168.16
      1346480.70      1029246.53
#Sta/Elev= 30
  4682.5  701.75  4715.1  696.07  4749.3  695.67  4752.5  694.92  4755.0  689.23
  4759.2  692.61  4795.0  687.34  4803.0  679.79  4810.9  684.05  4871.7  671.12
  4884.8  672.49  4939.5  667.87  4957.4  661.37  4964.8  661.37  4965.3  660.37
  5035.2  661.37  5041.4  664.53  5041.8  661.37  5045.9  667.55  5079.1  674.77
  5095.3  684.99  5106.2  683.71  5175.2  695.23  5194.2  690.74  5237.2  690.71
  5276.8  696.71  5307.5  696.67  5341.8  702.44  5407.4  701.50  5473.5  706.72
#Mann=3,-1,0
  4682.5    0.15       0  4964.8    0.05       0  5035.2    0.15       0
Bank Sta=4964.8,5035.2
XS Rating Curve= 0
Exp/Cntr=0.3,0.1

Type RM Length L Ch R = 1,17000,500,500,500
BEGIN DESCRIPTION:
Chauga River 34.0
END DESCRIPTION:
XS GIS Cut Line= 3
      1347500.28      1028363.58      1346967.92      1028714.47
      1346493.70      1028947.76
#Sta/Elev= 30
  4362.4  787.43  4434.7  771.46  4472.9  767.64  4493.5  757.82  4513.4  757.21
  4648.7  717.89  4766.3  694.66  4824.1  687.41  4866.2  671.56  4898.6  668.08
  4905.0  671.52  4934.1  670.06  4951.2  661.37  4964.8  661.37  4965.3  660.37
  5035.2  661.37  5037.1  665.61  5052.9  667.80  5111.1  670.06  5111.8  666.02
  5117.8  671.30  5140.5  676.10  5177.1  679.72  5204.3  687.29  5220.8  686.70
  5233.1  692.78  5330.0  709.57  5345.0  717.37  5385.8  721.02  5528.5  747.69
#Mann=3,-1,0
  4362.4    0.15       0  4964.8    0.05       0  5035.2    0.15       0
Bank Sta=4964.8,5035.2
XS Rating Curve= 0
Exp/Cntr=0.3,0.1

Type RM Length L Ch R = 1,16500,500,500,500
BEGIN DESCRIPTION:
Chauga River 33.0
END DESCRIPTION:
XS GIS Cut Line= 3
      1347257.58      1028156.91      1346569.52      1028423.51
      1346071.32      1028678.15
#Sta/Elev= 30
  4262.1  767.38  4322.5  752.81  4613.7  698.61  4691.8  695.37  4753.6  681.64
  4783.8  678.53  4846.4  677.60  4891.0  669.00  4930.5  666.44  4943.0  668.88
  4950.1  667.91  4952.5  665.82  4953.5  661.37  4957.9  666.22  4964.8  661.37
  4965.3  660.37  5035.2  661.37  5038.8  665.84  5062.0  672.28  5068.7  678.71
  5113.1  701.38  5134.7  718.42  5171.0  738.02  5234.6  763.35  5270.6  771.62
  5290.2  781.43  5316.1  780.92  5371.3  793.52  5480.8  801.92  5559.5  802.00
#Mann=3,-1,0
  4262.1    0.15       0  4964.8    0.05       0  5035.2    0.15       0
Bank Sta=4964.8,5035.2
XS Rating Curve= 0
Exp/Cntr=0.3,0.1

Type RM Length L Ch R = 1,16000,688,688,688
BEGIN DESCRIPTION:
Chauga River 32.0
END DESCRIPTION:
XS GIS Cut Line= 3
      1347149.73      1027923.25      1346521.45      1027927.90
      1345891.59      1028156.91
#Sta/Elev= 30
  4371.7  761.06  4387.1  761.80  4521.5  750.87  4625.2  736.75  4833.4  676.49
  4844.9  678.98  4908.4  668.56  4954.0  666.94  4959.1  661.37  4964.8  661.29
  4965.3  660.29  5035.2  661.29  5052.4  663.09  5054.1  661.37  5055.7  664.96
  5059.9  666.32  5085.8  669.98  5090.4  677.59  5136.6  699.44  5170.9  712.46
  5243.8  720.75  5311.3  720.35  5381.9  706.37  5445.7  698.81  5467.3  699.19
  5501.0  708.89  5549.8  718.31  5604.4  718.94  5650.9  714.58  5670.2  702.49
#Mann=3,-1,0
  4371.7    0.15       0  4964.8    0.05       0  5035.2    0.15       0
Bank Sta=4964.8,5035.2
XS Rating Curve= 0
Exp/Cntr=0.3,0.1

Type RM Length L Ch R = 1,15312,312,312,312
BEGIN DESCRIPTION:
Chauga River 31.0
END DESCRIPTION:
XS GIS Cut Line= 4
      1347068.86      1027581.74      1346744.40      1027291.84
      1346478.30      1027242.72      1345903.72      1027028.83
#Sta/Elev= 30
  4294.3  707.86  4429.1  700.67  4454.6  706.00  4505.5  696.39  4707.8  685.58
  4761.9  679.26  4777.5  671.04  4815.4  673.60  4935.5  668.25  4936.3  664.05
  4938.6  668.02  4945.0  668.09  4951.1  661.37  4963.8  664.36  4964.8  661.20
  4965.3  660.20  5035.2  661.20  5052.7  661.37  5061.6  667.61  5129.7  664.49
  5140.6  668.41  5213.9  662.42  5303.1  664.63  5311.3  661.37  5365.1  661.37
  5382.0  666.11  5425.8  662.11  5507.3  701.16  5569.5  720.70  5613.1  729.41
#Mann=3,-1,0
  4294.3    0.15       0  4964.8    0.05       0  5035.2    0.15       0
Bank Sta=4964.8,5035.2
XS Rating Curve= 0
Exp/Cntr=0.3,0.1

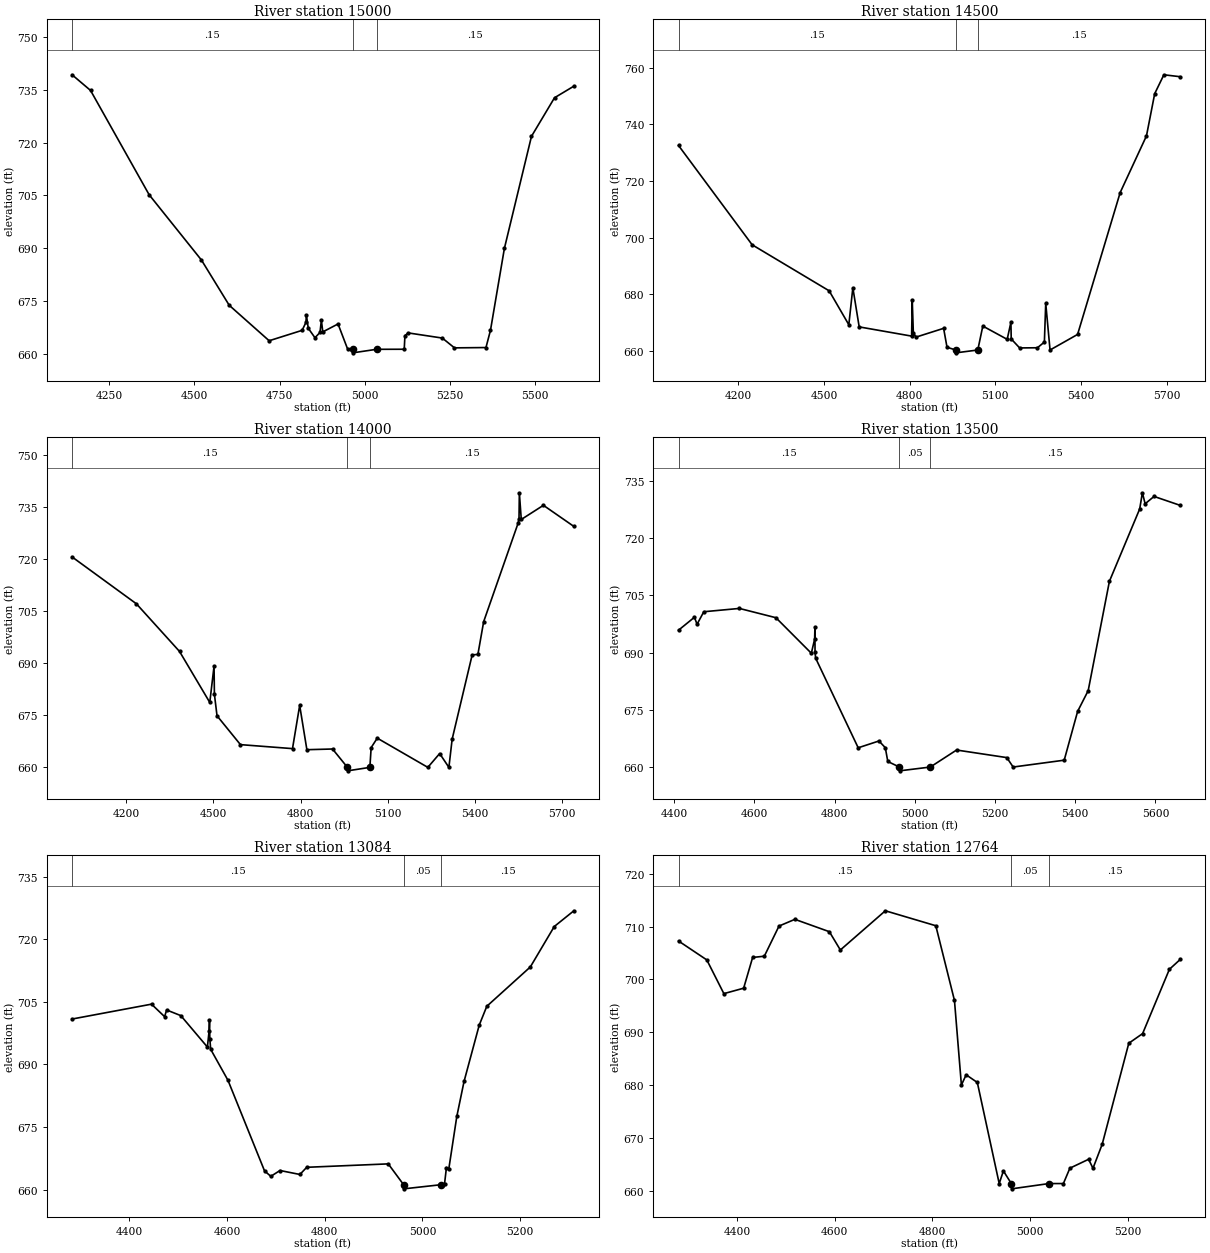
Type RM Length L Ch R = 1,15000,500,500,500
BEGIN DESCRIPTION:
Chauga River 30.0
END DESCRIPTION:
XS GIS Cut Line= 3
      1347293.56      1026891.55      1346434.67      1026933.29
      1345819.74      1026954.46
#Sta/Elev= 30
  4140.1  739.22  4194.4  734.78  4366.7  705.19  4520.6  686.65  4602.1  673.84
  4719.5  663.78  4816.4  666.73  4827.7  669.00  4828.9  671.12  4834.5  667.32
  4854.2  664.63  4869.0  666.14  4873.0  669.59  4877.2  666.29  4922.0  668.54
  4950.4  661.37  4964.8  661.35  4965.3  660.35  5035.2  661.35  5116.6  661.37
  5118.7  665.23  5128.4  666.00  5228.6  664.54  5264.3  661.76  5356.9  661.85
  5370.2  666.76  5411.1  689.99  5490.7  721.76  5558.4  732.70  5615.3  735.99
#Mann=3,-1,0
  4140.1    0.15       0  4964.8    0.05       0  5035.2    0.15       0
Bank Sta=4964.8,5035.2
XS Rating Curve= 0
Exp/Cntr=0.3,0.1

Type RM Length L Ch R = 1,14500,500,500,500
BEGIN DESCRIPTION:
Chauga River 29.0
END DESCRIPTION:
XS GIS Cut Line= 3
      1347365.41      1026559.03      1346363.85      1026438.35
      1345624.99      1026325.00
#Sta/Elev= 30
  3991.2  732.52  4248.8  697.51  4518.4  681.27  4587.2  669.31  4601.3  682.35
  4623.5  668.55  4807.0  665.30  4809.2  677.94  4813.0  666.49  4822.2  664.94
  4919.0  668.04  4930.9  661.37  4961.4  660.40  4961.9  659.40  5038.6  660.40
  5056.2  668.84  5141.5  664.16  5154.6  670.22  5155.6  664.30  5185.1  661.13
  5247.3  661.19  5271.7  663.20  5276.4  676.88  5291.5  660.40  5387.9  665.89
  5537.0  715.93  5629.0  735.91  5657.8  750.80  5689.9  757.46  5747.5  756.77
#Mann=3,-1,0
  3991.2    0.15       0  4961.4    0.05       0  5038.6    0.15       0
Bank Sta=4961.4,5038.6
XS Rating Curve= 0
Exp/Cntr=0.3,0.1

Type RM Length L Ch R = 1,14000,500,500,500
BEGIN DESCRIPTION:
Chauga River 28.0
END DESCRIPTION:
XS GIS Cut Line= 3
      1347437.30      1026280.43      1346500.13      1025972.71
      1345765.77      1025876.03
#Sta/Elev= 30
  4013.6  720.53  4235.0  707.03  4383.5  693.30  4487.6  678.61  4502.3  689.09
  4503.5  680.98  4512.5  674.77  4593.1  666.46  4772.3  665.31  4797.0  677.76
  4821.8  665.00  4910.1  665.20  4961.4  659.91  4961.9  658.91  5038.6  659.91
  5043.0  665.60  5064.0  668.33  5238.1  659.91  5278.8  663.89  5310.6  659.91
  5321.8  668.04  5390.7  692.31  5410.4  692.45  5430.3  701.90  5549.3  730.37
  5551.9  731.58  5553.1  739.01  5559.7  731.32  5635.9  735.40  5740.7  729.32
#Mann=3,-1,0
  4013.6    0.15       0  4961.4    0.05       0  5038.6    0.15       0
Bank Sta=4961.4,5038.6
XS Rating Curve= 0
Exp/Cntr=0.3,0.1

Type RM Length L Ch R = 1,13500,416,416,416
BEGIN DESCRIPTION:
Chauga River 27.0
END DESCRIPTION:
XS GIS Cut Line= 3
      1347077.88      1025202.00      1346588.41      1025529.80
      1345945.52      1025687.30
#Sta/Elev= 30
  4410.9  695.88  4450.5  699.28  4457.1  697.44  4473.9  700.73  4562.6  701.60
  4653.7  699.16  4742.0  689.82  4750.2  693.52  4750.9  696.61  4751.2  690.22
  4752.6  688.55  4858.8  664.97  4910.6  666.76  4926.4  664.99  4932.6  661.37
  4961.4  659.91  4961.9  658.91  5038.6  659.91  5104.1  664.38  5229.3  662.39
  5245.1  659.91  5372.4  661.71  5405.9  674.55  5432.2  679.99  5485.1  708.73
  5560.6  727.75  5567.3  732.00  5574.2  729.11  5596.4  731.04  5661.9  728.68
#Mann=3,-1,0
  4410.9    0.15       0  4961.4    0.05       0  5038.6    0.15       0
Bank Sta=4961.4,5038.6
XS Rating Curve= 0
Exp/Cntr=0.3,0.1

Type RM Length L Ch R = 1,13084,320,320,320
BEGIN DESCRIPTION:
Chauga River 26.0
END DESCRIPTION:
XS GIS Cut Line= 3
      1346991.35      1025223.62      1346279.01      1025306.92
      1345981.22      1025392.70
#Sta/Elev= 30
  4282.8  700.91  4445.4  704.48  4472.2  701.48  4476.4  703.08  4505.4  701.73
  4559.8  694.19  4563.2  697.93  4564.1  700.68  4564.8  696.14  4566.5  693.65
  4601.9  686.21  4676.7  664.48  4689.6  663.16  4708.4  664.56  4749.1  663.61
  4763.1  665.33  4930.0  666.15  4961.4  661.16  4961.9  660.16  5038.6  661.16
  5045.2  661.37  5049.1  665.28  5054.0  665.00  5070.3  677.53  5085.1  685.92
  5116.2  699.45  5131.7  703.97  5220.8  713.41  5269.8  723.11  5309.9  726.89
#Mann=3,-1,0
  4282.8    0.15       0  4961.4    0.05       0  5038.6    0.15       0
Bank Sta=4961.4,5038.6
XS Rating Curve= 0
Exp/Cntr=0.3,0.1

Type RM Length L Ch R = 1,12764,181,181,181
BEGIN DESCRIPTION:
Chauga River 25.5
END DESCRIPTION:
XS GIS Cut Line= 4
      1346729.14      1024696.86      1346226.21      1024833.43
      1346160.46      1025020.99      1346093.99      1025321.12
#Sta/Elev= 30
  4280.1  707.27  4338.0  703.69  4372.9  697.31  4413.4  698.34  4431.8  704.16
  4455.7  704.39  4485.8  710.10  4518.3  711.37  4588.9  709.03  4611.4  705.57
  4703.5  712.99  4806.8  710.16  4845.0  696.02  4859.2  680.01  4868.9  681.95
  4891.8  680.50  4936.6  661.37  4945.2  663.76  4961.4  661.37  4961.9  660.37
  5038.6  661.37  5068.0  661.37  5081.3  664.28  5119.6  665.96  5128.6  664.26
  5147.5  668.82  5201.9  687.92  5230.2  689.75  5285.0  701.91  5307.4  703.80
#Mann=3,-1,0
  4280.1    0.15       0  4961.4    0.05       0  5038.6    0.15       0
Bank Sta=4961.4,5038.6
XS Rating Curve= 0
Exp/Cntr=0.3,0.1

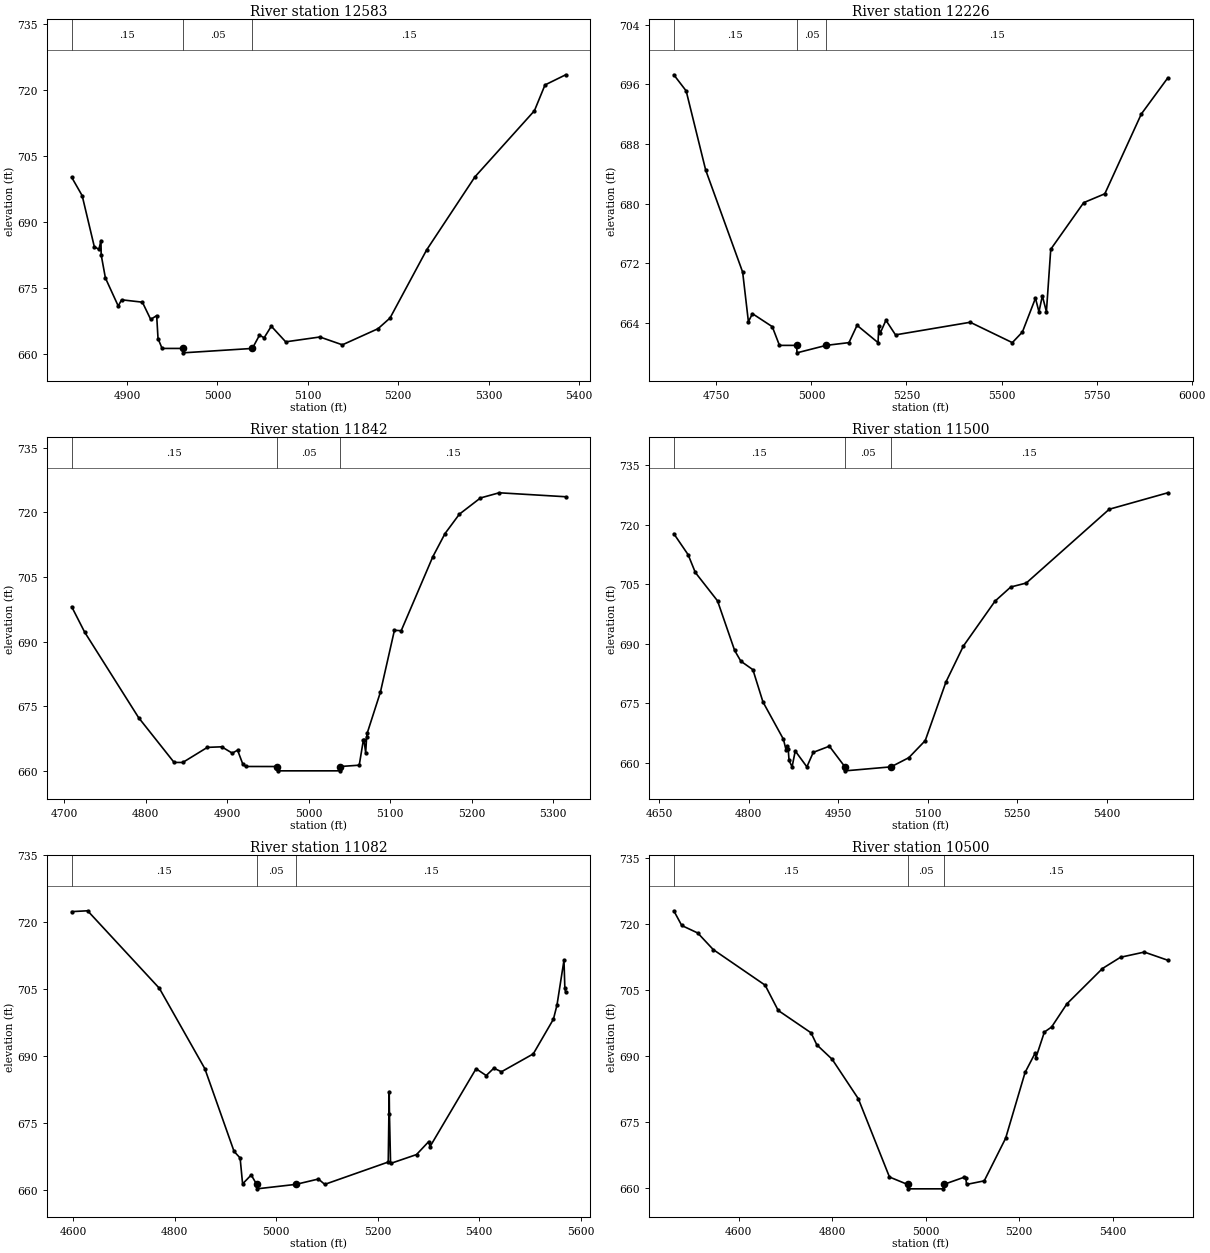
Type RM Length L Ch R = 1,12583,357,357,357
BEGIN DESCRIPTION:
Chauga River 25.0
END DESCRIPTION:
XS GIS Cut Line= 3
      1346026.38      1024823.68      1345989.27      1024980.55
      1345937.91      1025362.31
#Sta/Elev= 30
  4838.8  700.25  4850.4  696.08  4863.8  684.50  4868.9  683.88  4871.2  685.89
  4871.4  682.66  4876.1  677.38  4890.3  671.00  4894.0  672.42  4917.0  671.88
  4926.2  667.96  4932.8  668.83  4934.3  663.62  4938.8  661.37  4961.4  661.37
  4961.9  660.37  5038.6  661.37  5046.5  664.37  5051.7  663.80  5059.6  666.42
  5075.5  662.87  5113.3  663.97  5138.2  662.19  5177.6  665.85  5190.9  668.28
  5231.3  683.72  5284.8  700.35  5350.6  715.37  5362.3  721.23  5385.2  723.54
#Mann=3,-1,0
  4838.8    0.15       0  4961.4    0.05       0  5038.6    0.15       0
Bank Sta=4961.4,5038.6
XS Rating Curve= 0
Exp/Cntr=0.3,0.1

Type RM Length L Ch R = 1,12226,384,384,384
BEGIN DESCRIPTION:
Chauga River 24.5
END DESCRIPTION:
XS GIS Cut Line= 4
      1346002.93      1024803.08      1345654.97      1024902.90
      1345044.83      1025243.12      1344893.07      1025427.39
#Sta/Elev= 30
  4638.0  697.29  4670.5  695.13  4721.8  684.52  4819.1  670.82  4834.2  664.18
  4844.9  665.25  4897.0  663.51  4915.9  661.00  4961.4  661.00  4961.9  660.00
  5038.6  661.00  5098.7  661.37  5120.0  663.69  5175.2  661.37  5177.0  663.60
  5180.6  662.61  5195.9  664.37  5221.1  662.41  5417.6  664.10  5528.3  661.37
  5554.8  662.79  5589.2  667.33  5598.4  665.50  5607.3  667.64  5618.0  665.52
  5629.4  673.89  5716.0  680.14  5771.6  681.33  5867.6  692.03  5937.3  696.88
#Mann=3,-1,0
  4638.0    0.15       0  4961.4    0.05       0  5038.6    0.15       0
Bank Sta=4961.4,5038.6
XS Rating Curve= 0
Exp/Cntr=0.3,0.1

Type RM Length L Ch R = 1,11842,342,342,342
BEGIN DESCRIPTION:
Chauga River 24.0
END DESCRIPTION:
XS GIS Cut Line= 3
      1346036.29      1024773.84      1345802.06      1024601.67
      1345536.17      1024431.65
#Sta/Elev= 30
  4709.3  698.11  4725.2  692.22  4791.4  672.40  4835.0  662.01  4845.6  662.00
  4875.8  665.50  4893.4  665.63  4906.4  664.16  4912.9  664.85  4919.4  661.58
  4923.0  661.07  4961.4  661.06  4961.9  660.06  5038.1  660.06  5038.6  661.06
  5062.2  661.37  5067.3  667.22  5068.1  667.13  5070.1  664.28  5071.3  667.87
  5071.9  668.74  5088.2  678.31  5105.4  692.65  5113.7  692.54  5152.5  709.69
  5167.5  715.07  5185.1  719.56  5211.0  723.32  5234.0  724.52  5315.6  723.60
#Mann=3,-1,0
  4709.3    0.15       0  4961.4    0.05       0  5038.6    0.15       0
Bank Sta=4961.4,5038.6
XS Rating Curve= 0
Exp/Cntr=0.3,0.1

Type RM Length L Ch R = 1,11500,418,418,418
BEGIN DESCRIPTION:
Chauga River 23.0
END DESCRIPTION:
XS GIS Cut Line= 3
      1346251.05      1024733.78      1346102.68      1024444.06
      1345825.01      1024025.01
#Sta/Elev= 30
  4674.5  717.71  4698.5  712.43  4710.6  707.95  4747.8  700.82  4776.5  688.34
  4786.9  685.64  4807.1  683.50  4824.0  675.38  4858.3  666.00  4862.9  663.19
  4864.6  664.27  4866.3  663.56  4867.7  660.68  4872.8  659.06  4878.1  663.06
  4897.6  659.06  4908.3  662.71  4935.3  664.26  4961.4  659.06  4961.9  658.06
  5038.6  659.06  5068.5  661.37  5096.0  665.66  5130.8  680.43  5159.9  689.43
  5213.0  700.74  5239.4  704.30  5265.4  705.30  5404.5  723.86  5502.7  728.00
#Mann=3,-1,0
  4674.5    0.15       0  4961.4    0.05       0  5038.6    0.15       0
Bank Sta=4961.4,5038.6
XS Rating Curve= 0
Exp/Cntr=0.3,0.1

Type RM Length L Ch R = 1,11082,582,582,582
BEGIN DESCRIPTION:
Chauga River 22.0
END DESCRIPTION:
XS GIS Cut Line= 3
      1346764.54      1024580.85      1346487.60      1024288.08
      1346089.31      1023880.05
#Sta/Elev= 30
  4597.0  722.40  4628.4  722.59  4769.7  705.22  4859.3  687.20  4916.9  668.65
  4928.8  667.18  4933.7  661.37  4950.7  663.37  4961.4  661.26  4961.9  660.26
  5038.6  661.26  5083.1  662.46  5095.5  661.26  5220.6  666.27  5222.5  682.07
  5223.0  677.04  5225.2  665.95  5276.3  667.94  5300.4  670.86  5302.9  669.72
  5393.6  687.18  5413.6  685.66  5428.7  687.31  5443.6  686.50  5506.3  690.51
  5546.0  698.29  5553.0  701.44  5566.8  711.50  5568.5  705.34  5570.2  704.28
#Mann=3,-1,0
  4597.0    0.15       0  4961.4    0.05       0  5038.6    0.15       0
Bank Sta=4961.4,5038.6
XS Rating Curve= 0
Exp/Cntr=0.3,0.1

Type RM Length L Ch R = 1,10500,500,500,500
BEGIN DESCRIPTION:
Chauga River 21.0
END DESCRIPTION:
XS GIS Cut Line= 3
      1347266.61      1023933.97      1346751.73      1023776.89
      1346275.02      1023575.01
#Sta/Elev= 30
  4461.7  723.07  4478.7  719.72  4512.9  718.01  4546.1  714.23  4656.9  706.14
  4684.8  700.39  4755.1  695.29  4767.4  692.56  4800.2  689.27  4856.1  680.29
  4922.7  662.47  4961.4  660.78  4961.9  659.78  5038.1  659.78  5038.6  660.78
  5081.5  662.39  5086.0  662.20  5087.4  660.78  5125.3  661.60  5171.0  671.29
  5212.6  686.28  5234.5  690.76  5235.8  689.64  5253.8  695.46  5269.3  696.62
  5302.0  701.89  5378.0  709.93  5416.6  712.49  5467.4  713.67  5517.7  711.81
#Mann=3,-1,0
  4461.7    0.15       0  4961.4    0.05       0  5038.6    0.15       0
Bank Sta=4961.4,5038.6
XS Rating Curve= 0
Exp/Cntr=0.3,0.1

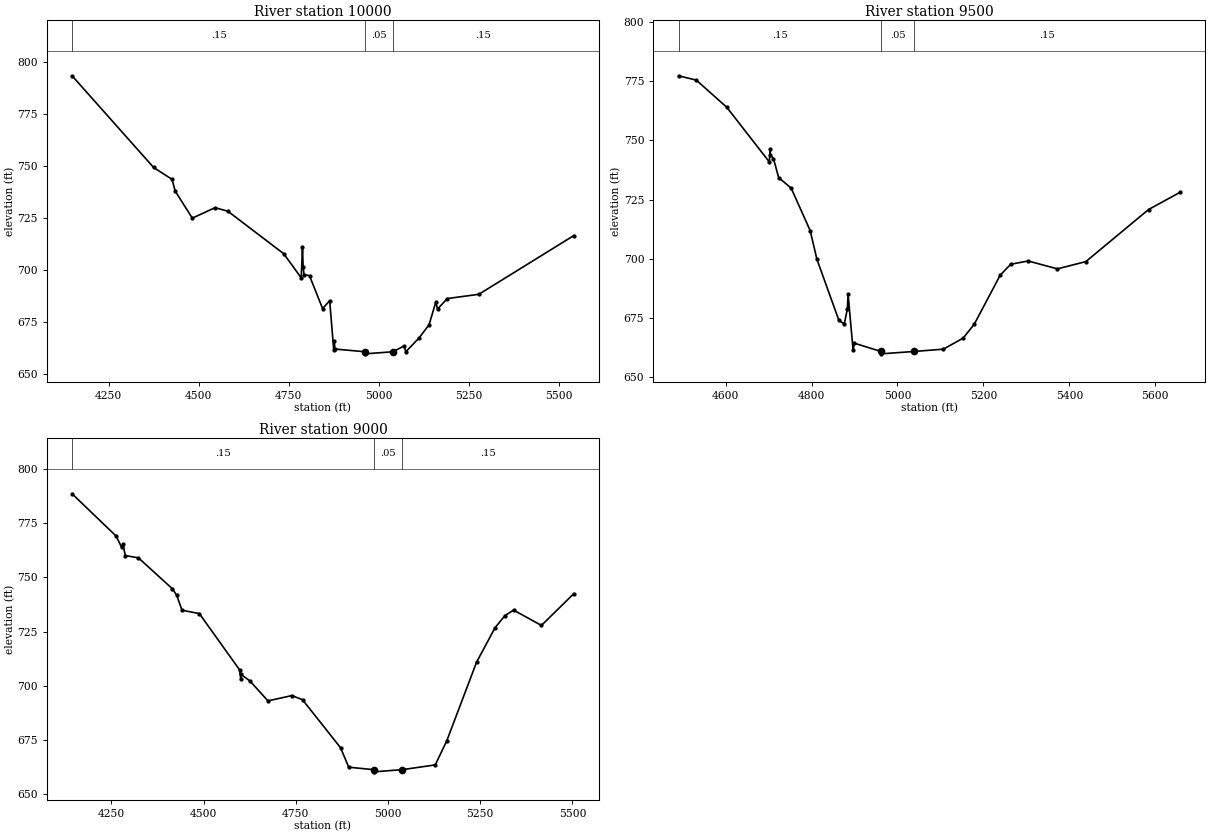
Type RM Length L Ch R = 1,10000,500,500,500
BEGIN DESCRIPTION:
Chauga River 20.0
END DESCRIPTION:
XS GIS Cut Line= 3
      1347425.00      1022675.00      1346833.86      1023288.14
      1346374.96      1023575.03
#Sta/Elev= 30
  4148.3  793.38  4374.6  749.26  4425.7  743.54  4434.9  737.77  4482.1  724.87
  4545.2  729.89  4580.8  728.19  4735.9  707.72  4784.4  696.13  4787.9  710.77
  4789.7  701.41  4792.1  697.73  4807.4  697.14  4843.7  681.34  4863.4  685.13
  4874.7  661.37  4875.9  665.81  4878.2  661.86  4961.3  660.55  4961.8  659.55
  5038.7  660.55  5070.1  663.36  5074.7  660.55  5110.9  667.08  5139.2  673.52
  5158.0  684.46  5162.8  681.07  5189.6  686.15  5277.5  688.21  5541.2  716.49
#Mann=3,-1,0
  4148.3    0.15       0  4961.3    0.05       0  5038.7    0.15       0
Bank Sta=4961.3,5038.7
XS Rating Curve= 0
Exp/Cntr=0.3,0.1

Type RM Length L Ch R = 1,9500,500,500,500
BEGIN DESCRIPTION:
Chauga River 19.0
END DESCRIPTION:
XS GIS Cut Line= 3
      1346775.02      1022624.98      1346439.98      1023008.96
      1345975.02      1023474.98
#Sta/Elev= 30
  4490.4  777.27  4531.7  775.44  4602.6  763.99  4701.8  740.87  4703.5  746.48
  4704.2  743.84  4711.3  742.34  4723.5  734.26  4752.5  729.86  4796.7  711.94
  4812.5  699.80  4863.7  673.98  4876.2  672.50  4883.5  678.97  4885.0  685.11
  4896.7  661.37  4899.4  664.39  4961.3  660.88  4961.8  659.88  5038.7  660.88
  5106.6  661.85  5152.6  666.49  5178.5  672.32  5239.2  693.13  5263.6  697.71
  5304.2  699.08  5372.3  695.75  5438.4  698.82  5584.4  720.81  5658.3  728.13
#Mann=3,-1,0
  4490.4    0.15       0  4961.3    0.05       0  5038.7    0.15       0
Bank Sta=4961.3,5038.7
XS Rating Curve= 0
Exp/Cntr=0.3,0.1

Type RM Length L Ch R = 1,9000,500,500,500
BEGIN DESCRIPTION:
Chauga River 18.0
END DESCRIPTION:
XS GIS Cut Line= 3
      1346824.99      1022525.00      1346004.22      1022769.46
      1345525.03      1022924.99
#Sta/Elev= 30
  4143.6  788.44  4263.1  768.95  4278.0  763.75  4281.5  765.12  4287.9  759.99
  4323.5  758.93  4415.3  744.72  4427.3  741.67  4441.6  734.80  4488.6  733.26
  4597.5  707.38  4601.0  703.12  4601.4  705.25  4625.3  702.30  4674.6  693.05
  4739.6  695.50  4768.3  693.58  4871.7  671.40  4893.5  662.50  4961.3  661.37
  4961.8  660.37  5038.7  661.37  5128.1  663.57  5159.1  674.57  5240.0  710.84
  5289.8  726.64  5317.0  732.35  5340.4  734.86  5415.9  727.81  5503.8  742.46
#Mann=3,-1,0
  4143.6    0.15       0  4961.3    0.05       0  5038.7    0.15       0
Bank Sta=4961.3,5038.7
XS Rating Curve= 0
Exp/Cntr=0.3,0.1