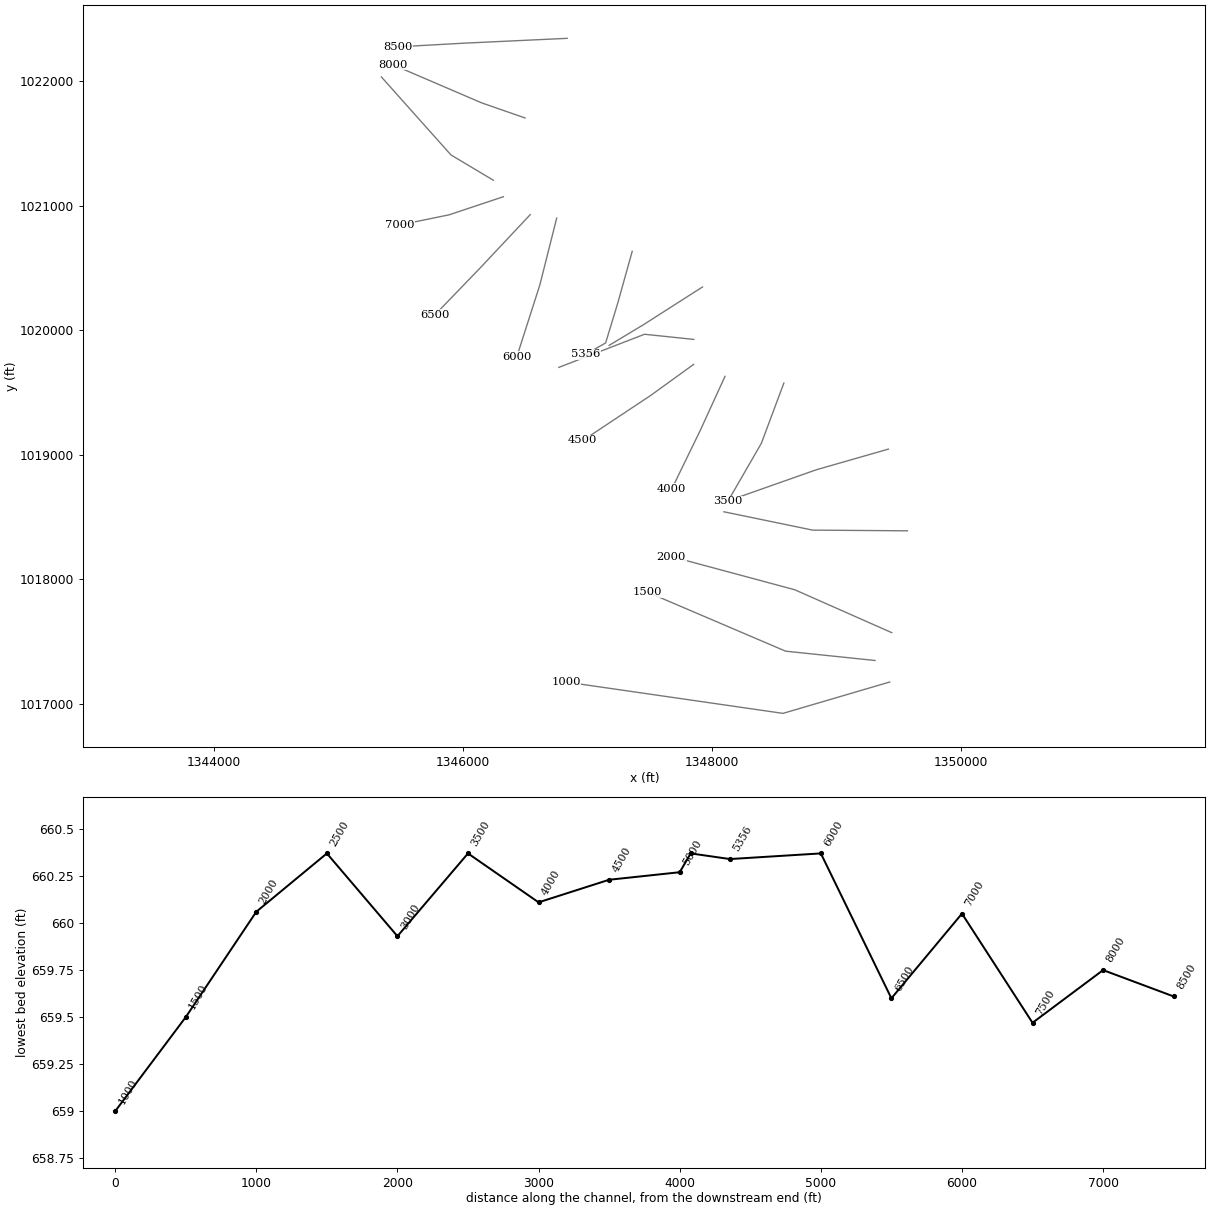
HEC-RAS study Chauga River.prj: Chauga River Limited Detail Study

--- Chauga River.g01 (geometry) --- (continued)

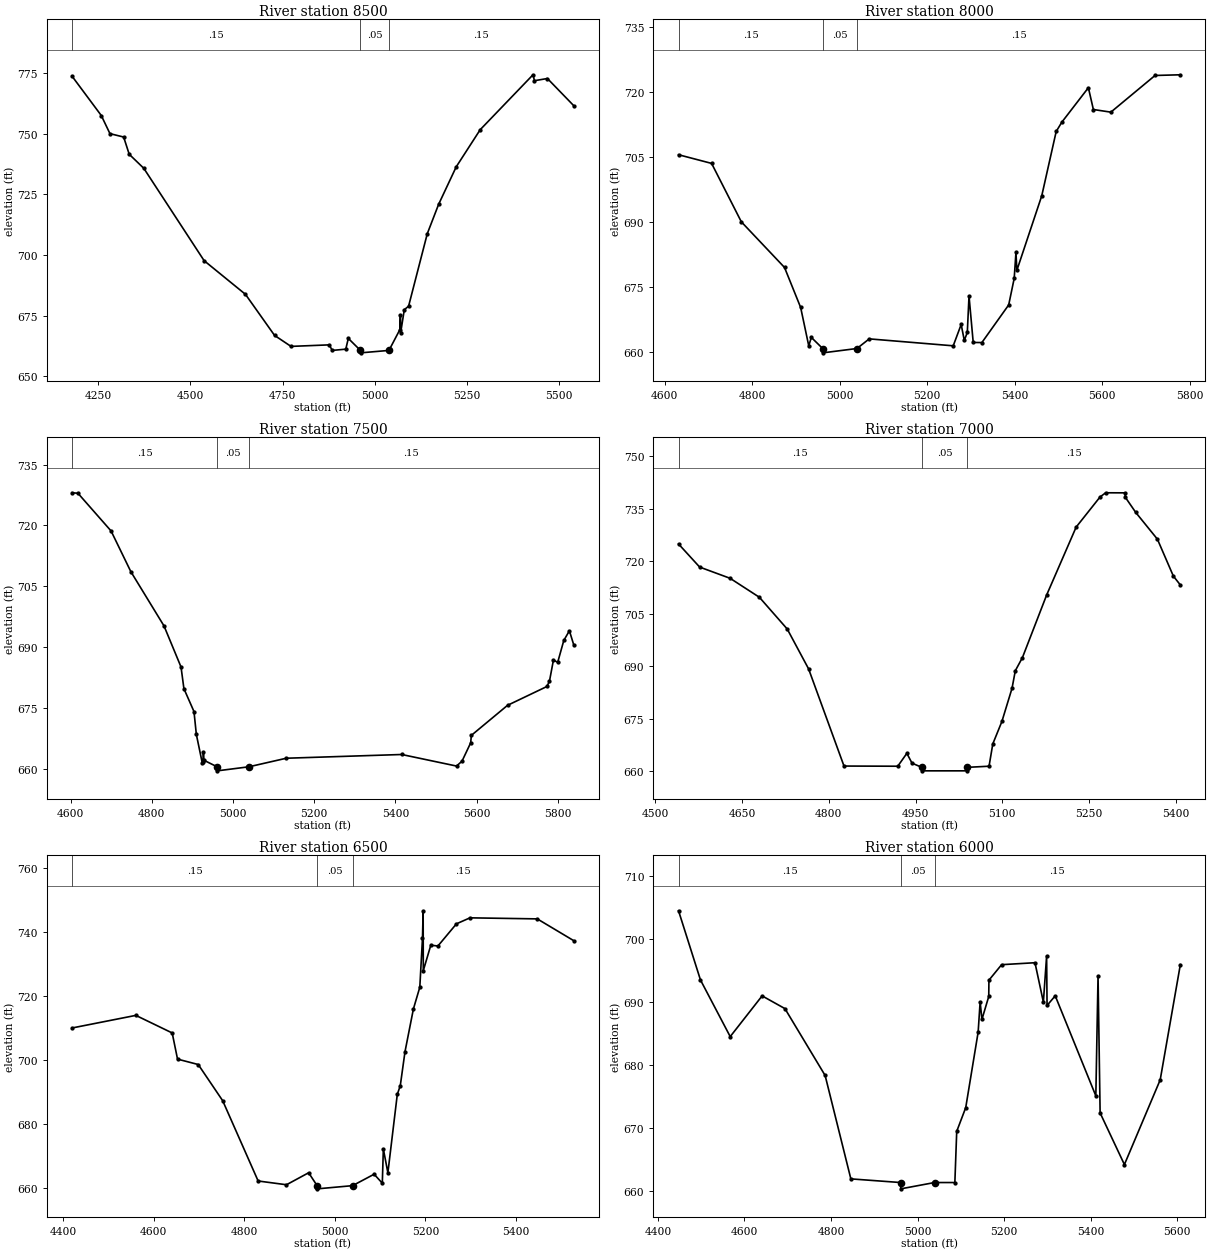
Type RM Length L Ch R = 1,8500,500,500,500
BEGIN DESCRIPTION:
Chauga River 17.0
END DESCRIPTION:
XS GIS Cut Line= 3
      1346835.22      1022343.28      1346014.72      1022304.85
      1345475.05      1022275.00
#Sta/Elev= 30
  4178.6  773.75  4257.9  757.54  4281.4  750.06  4318.6  748.66  4333.7  741.55
  4373.3  735.75  4537.0  697.64  4649.2  683.75  4728.2  666.80  4772.8  662.27
  4876.3  662.90  4885.0  660.61  4921.5  661.13  4928.3  665.57  4961.3  660.61
  4961.8  659.61  5038.7  660.61  5068.1  669.14  5069.8  675.10  5070.4  667.88
  5080.3  677.42  5091.9  678.84  5142.7  708.78  5173.5  720.91  5221.3  736.39
  5286.3  751.69  5429.6  774.35  5433.6  771.91  5468.7  772.81  5540.5  761.55
#Mann=3,-1,0
  4178.6    0.15       0  4961.3    0.05       0  5038.7    0.15       0
Bank Sta=4961.3,5038.7
XS Rating Curve= 0
Exp/Cntr=0.3,0.1

Type RM Length L Ch R = 1,8000,500,500,500
BEGIN DESCRIPTION:
Chauga River 16.0
END DESCRIPTION:
XS GIS Cut Line= 3
      1346496.87      1021703.94      1346148.65      1021825.10
      1345433.23      1022132.09
#Sta/Elev= 30
  4631.3  705.44  4706.9  703.44  4774.9  689.96  4873.6  679.44  4910.5  670.21
  4929.0  661.37  4934.9  663.31  4960.8  660.75  4961.3  659.75  5039.2  660.75
  5067.3  662.97  5259.3  661.37  5277.5  666.29  5284.6  662.61  5291.5  664.46
  5295.4  672.87  5305.0  662.14  5324.8  662.12  5386.1  670.80  5398.7  676.92
  5402.7  682.90  5404.8  678.78  5461.7  695.97  5494.7  710.80  5507.6  712.95
  5568.3  720.90  5579.7  715.87  5619.7  715.26  5720.7  723.72  5778.5  723.88
#Mann=3,-1,0
  4631.3    0.15       0  4960.8    0.05       0  5039.2    0.15       0
Bank Sta=4960.8,5039.2
XS Rating Curve= 0
Exp/Cntr=0.3,0.1

Type RM Length L Ch R = 1,7500,500,500,500
BEGIN DESCRIPTION:
Chauga River 15.0
END DESCRIPTION:
XS GIS Cut Line= 3
      1346242.48      1021203.83      1345902.19      1021406.94
      1345343.41      1022033.19
#Sta/Elev= 30
  4603.7  728.05  4618.1  727.94  4699.7  718.64  4748.4  708.60  4830.1  695.21
  4872.0  685.08  4879.1  679.74  4903.9  674.09  4909.7  668.46  4924.4  661.37
  4926.0  661.62  4927.1  664.02  4928.5  662.07  4960.8  660.47  4961.3  659.47
  5039.2  660.47  5131.3  662.58  5415.4  663.50  5550.4  660.65  5563.9  661.86
  5585.3  666.39  5586.8  668.21  5676.0  675.63  5773.1  680.28  5779.3  681.62
  5789.0  686.80  5799.5  686.23  5814.5  691.62  5828.3  694.02  5839.3  690.45
#Mann=3,-1,0
  4603.7    0.15       0  4960.8    0.05       0  5039.2    0.15       0
Bank Sta=4960.8,5039.2
XS Rating Curve= 0
Exp/Cntr=0.3,0.1

Type RM Length L Ch R = 1,7000,500,500,500
BEGIN DESCRIPTION:
Chauga River 14.0
END DESCRIPTION:
XS GIS Cut Line= 3
      1346322.92      1021071.62      1345887.03      1020926.21
      1345487.89      1020844.10
#Sta/Elev= 30
  4540.5  724.96  4577.0  718.35  4629.6  715.14  4680.2  709.71  4728.3  700.63
  4765.2  689.23  4826.4  661.42  4919.3  661.37  4935.0  665.06  4943.9  662.25
  4960.8  661.05  4961.3  660.05  5038.7  660.05  5039.2  661.05  5077.0  661.37
  5083.5  667.76  5099.2  674.17  5116.7  683.66  5122.4  688.70  5134.7  692.46
  5176.6  710.39  5227.5  729.79  5268.8  738.41  5278.5  739.61  5312.1  739.59
  5312.4  738.34  5330.5  733.98  5367.9  726.33  5395.5  715.76  5407.5  713.24
#Mann=3,-1,0
  4540.5    0.15       0  4960.8    0.05       0  5039.2    0.15       0
Bank Sta=4960.8,5039.2
XS Rating Curve= 0
Exp/Cntr=0.3,0.1

Type RM Length L Ch R = 1,6500,500,500,500
BEGIN DESCRIPTION:
Chauga River 13.0
END DESCRIPTION:
XS GIS Cut Line= 3
      1346538.65      1020927.85      1346141.46      1020504.79
      1345774.97      1020124.97
#Sta/Elev= 30
  4419.7  710.01  4560.5  713.96  4640.8  708.45  4652.6  700.25  4698.3  698.56
  4752.3  687.22  4830.6  662.06  4893.2  660.88  4942.1  664.64  4960.8  660.60
  4961.3  659.60  5039.2  660.60  5086.7  664.18  5104.8  661.37  5107.1  672.11
  5117.1  664.63  5137.9  689.20  5144.5  691.94  5154.9  702.58  5173.5  715.99
  5187.6  722.78  5193.5  738.06  5195.0  746.74  5195.3  727.97  5211.9  735.96
  5227.6  735.70  5268.5  742.65  5298.4  744.53  5447.0  744.20  5527.8  737.35
#Mann=3,-1,0
  4419.7    0.15       0  4960.8    0.05       0  5039.2    0.15       0
Bank Sta=4960.8,5039.2
XS Rating Curve= 0
Exp/Cntr=0.3,0.1

Type RM Length L Ch R = 1,6000,644,644,644
BEGIN DESCRIPTION:
Chauga River 12.0
END DESCRIPTION:
XS GIS Cut Line= 3
      1346751.01      1020900.12      1346616.10      1020364.65
      1346430.81      1019786.52
#Sta/Elev= 30
  4447.8  704.48  4498.5  693.50  4567.2  684.52  4640.9  690.98  4693.6  688.96
  4786.5  678.35  4845.9  661.95  4960.8  661.37  4961.3  660.37  5039.2  661.37
  5086.2  661.37  5090.5  669.49  5111.3  673.25  5140.0  685.23  5144.6  690.05
  5148.7  687.24  5164.5  690.89  5164.9  693.47  5194.2  695.93  5271.3  696.24
  5290.7  690.00  5298.2  697.32  5299.2  689.46  5318.1  690.99  5411.9  675.12
  5417.0  694.16  5421.8  672.41  5477.9  664.22  5560.6  677.66  5607.1  695.93
#Mann=3,-1,0
  4447.8    0.15       0  4960.8    0.05       0  5039.2    0.15       0
Bank Sta=4960.8,5039.2
XS Rating Curve= 0
Exp/Cntr=0.3,0.1

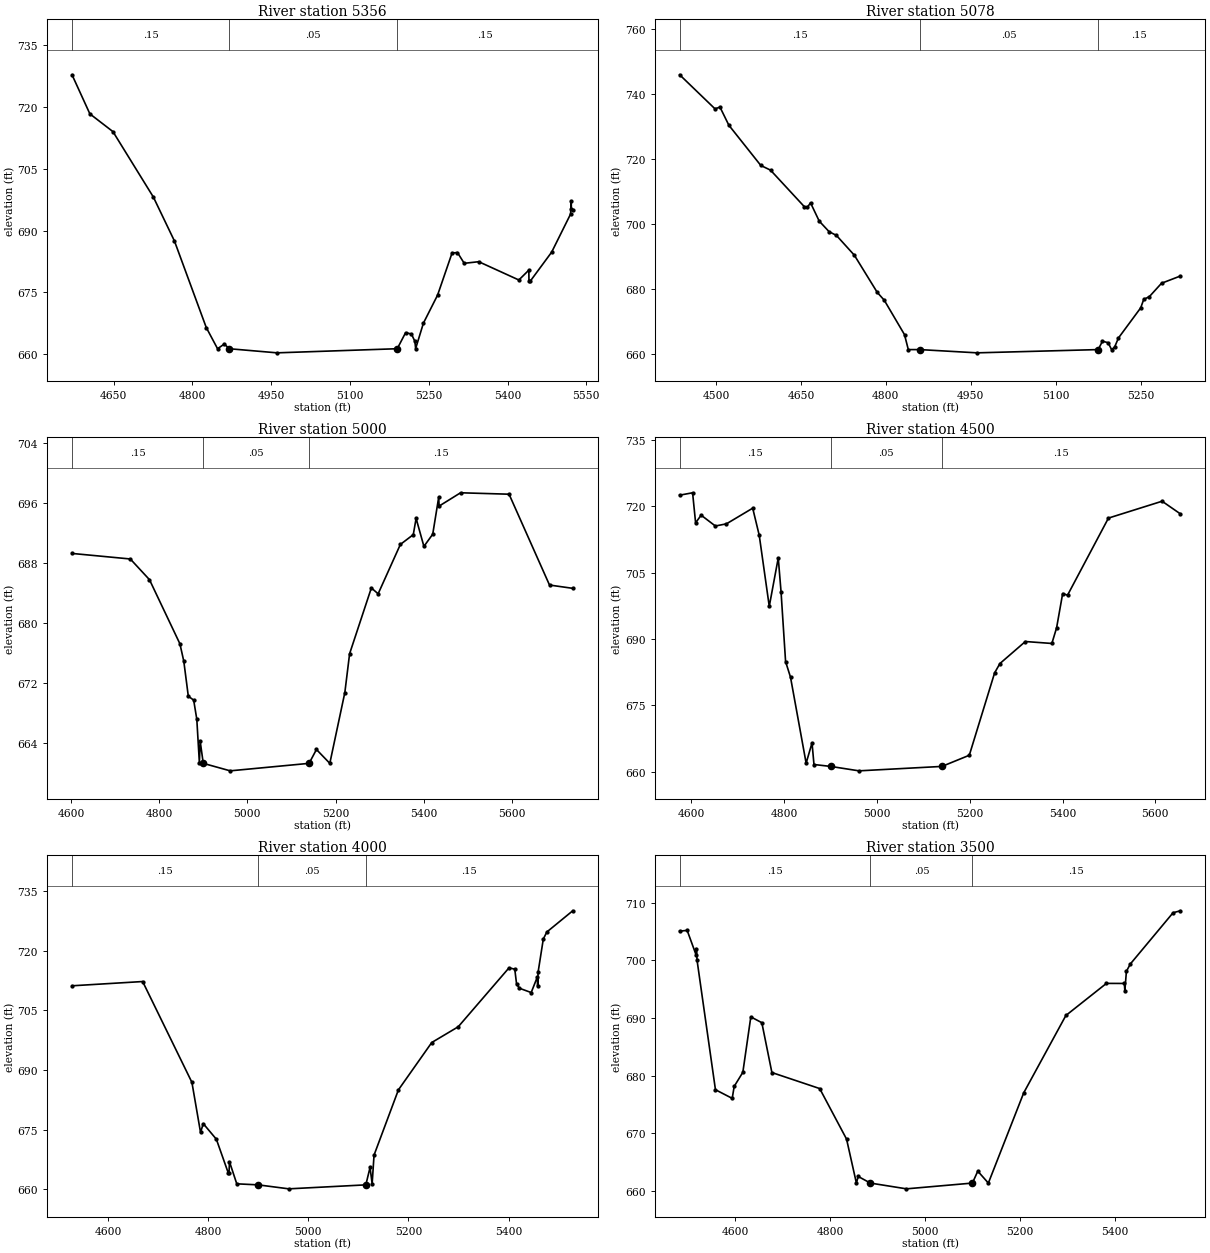
Type RM Length L Ch R = 1,5356,278,278,278
BEGIN DESCRIPTION:
Chauga River 11.5
END DESCRIPTION:
XS GIS Cut Line= 4
      1347357.45      1020633.40      1347241.98      1020220.03
      1347144.06      1019897.78      1346981.26      1019805.15
#Sta/Elev= 30
  4570.8  727.86  4604.8  718.37  4648.7  714.06  4725.7  698.16  4765.8  687.50
  4826.4  666.48  4847.9  661.34  4860.8  662.48  4870.0  661.34  4961.1  660.34
  5190.0  661.34  5205.9  665.24  5217.0  664.91  5223.6  663.12  5225.0  661.37
  5239.8  667.55  5266.8  674.36  5294.3  684.57  5304.6  684.70  5317.5  682.08
  5345.1  682.47  5421.5  678.03  5440.5  680.42  5440.8  677.68  5442.9  677.69
  5484.0  684.80  5520.0  694.04  5521.2  697.09  5521.5  695.35  5524.1  695.05
#Mann=3,-1,0
  4570.8    0.15       0  4870.0    0.05       0  5190.0    0.15       0
Bank Sta=4870,5190
XS Rating Curve= 0
Exp/Cntr=0.3,0.1

Type RM Length L Ch R = 1,5078,78,78,78
BEGIN DESCRIPTION:
Chauga River 11.0
END DESCRIPTION:
XS GIS Cut Line= 3
      1347921.76      1020346.99      1347446.49      1020043.14
      1347172.10      1019878.10
#Sta/Elev= 30
  4435.9  745.97  4498.3  735.49  4507.1  736.02  4522.8  730.44  4579.2  718.06
  4596.4  716.61  4655.9  705.40  4661.6  705.20  4667.0  706.56  4682.4  700.92
  4699.9  697.66  4712.7  696.53  4744.4  690.43  4784.9  678.97  4797.2  676.58
  4833.0  665.97  4839.7  661.37  4860.0  661.37  4961.1  660.37  5175.0  661.37
  5182.6  663.95  5192.6  663.49  5198.7  661.37  5204.1  662.17  5210.9  664.96
  5250.2  674.24  5255.5  676.84  5265.3  677.65  5286.9  681.79  5320.2  684.02
#Mann=3,-1,0
  4435.9    0.15       0  4860.0    0.05       0  5175.0    0.15       0
Bank Sta=4860,5175
XS Rating Curve= 0
Exp/Cntr=0.3,0.1

Type RM Length L Ch R = 1,5000,500,500,500
BEGIN DESCRIPTION:
Chauga River 10.0
END DESCRIPTION:
XS GIS Cut Line= 3
      1347851.58      1019925.85      1347456.13      1019967.15
      1346767.81      1019701.23
#Sta/Elev= 30
  4602.4  689.30  4734.6  688.56  4778.0  685.80  4847.1  677.23  4855.9  674.90
  4866.1  670.24  4878.3  669.71  4885.4  667.15  4891.2  661.37  4893.1  664.21
  4900.0  661.27  4961.1  660.27  5140.0  661.27  5156.7  663.12  5187.0  661.27
  5221.1  670.73  5231.9  675.91  5281.2  684.69  5296.6  683.91  5347.0  690.50
  5376.3  691.81  5382.7  693.98  5400.4  690.24  5420.4  691.87  5434.0  696.82
  5434.8  695.62  5483.5  697.40  5593.5  697.21  5685.2  685.08  5737.9  684.64
#Mann=3,-1,0
  4602.4    0.15       0  4900.0    0.05       0  5140.0    0.15       0
Bank Sta=4900,5140
XS Rating Curve= 0
Exp/Cntr=0.3,0.1

Type RM Length L Ch R = 1,4500,500,500,500
BEGIN DESCRIPTION:
Chauga River 9.0
END DESCRIPTION:
XS GIS Cut Line= 3
      1347850.72      1019725.38      1347505.88      1019476.10
      1346960.99      1019114.25
#Sta/Elev= 30
  4574.5  722.54  4602.4  723.08  4608.9  716.28  4620.8  718.02  4651.5  715.57
  4675.4  716.06  4732.0  719.60  4746.1  713.46  4767.7  697.41  4787.1  708.36
  4793.1  700.71  4802.9  684.92  4813.5  681.40  4847.2  661.96  4859.9  666.55
  4864.1  661.66  4900.0  661.23  4961.1  660.23  5140.0  661.23  5199.0  663.75
  5253.6  682.38  5265.0  684.48  5319.9  689.46  5377.0  689.02  5387.2  692.55
  5400.3  700.31  5410.8  699.93  5499.0  717.36  5614.7  721.17  5654.1  718.31
#Mann=3,-1,0
  4574.5    0.15       0  4900.0    0.05       0  5140.0    0.15       0
Bank Sta=4900,5140
XS Rating Curve= 0
Exp/Cntr=0.3,0.1

Type RM Length L Ch R = 1,4000,500,500,500
BEGIN DESCRIPTION:
Chauga River 8.0
END DESCRIPTION:
XS GIS Cut Line= 3
      1348102.35      1019629.20      1347906.04      1019200.07
      1347674.99      1018724.97
#Sta/Elev= 30
  4528.1  711.16  4669.2  712.23  4767.6  686.88  4784.8  674.31  4790.3  676.50
  4816.4  672.59  4840.0  664.18  4841.7  664.05  4842.6  666.94  4857.2  661.37
  4900.0  661.11  4961.1  660.11  5115.0  661.11  5123.4  665.48  5127.6  661.40
  5131.4  668.59  5180.1  685.00  5246.7  696.90  5299.6  700.86  5401.0  715.67
  5412.5  715.34  5416.1  711.62  5421.9  710.54  5445.3  709.46  5457.7  713.41
  5458.2  711.05  5459.1  714.58  5469.5  722.91  5476.5  724.68  5528.3  730.02
#Mann=3,-1,0
  4528.1    0.15       0  4900.0    0.05       0  5115.0    0.15       0
Bank Sta=4900,5115
XS Rating Curve= 0
Exp/Cntr=0.3,0.1

Type RM Length L Ch R = 1,3500,500,500,500
BEGIN DESCRIPTION:
Chauga River 7.0
END DESCRIPTION:
XS GIS Cut Line= 3
      1348574.99      1019574.97      1348393.96      1019091.02
      1348124.98      1018624.97
#Sta/Elev= 30
  4483.3  705.08  4499.1  705.22  4518.1  700.92  4518.7  702.06  4519.9  700.07
  4558.7  677.57  4594.0  676.07  4598.2  678.15  4616.4  680.59  4633.2  690.21
  4656.4  689.20  4677.6  680.55  4778.3  677.77  4834.9  669.00  4855.6  661.37
  4859.4  662.52  4885.0  661.37  4961.1  660.37  5100.0  661.37  5111.3  663.44
  5133.6  661.37  5208.1  677.03  5296.9  690.45  5382.3  696.02  5420.1  696.01
  5421.1  694.69  5424.4  698.11  5432.6  699.38  5522.7  708.28  5538.1  708.62
#Mann=3,-1,0
  4483.3    0.15       0  4885.0    0.05       0  5100.0    0.15       0
Bank Sta=4885,5100
XS Rating Curve= 0
Exp/Cntr=0.3,0.1

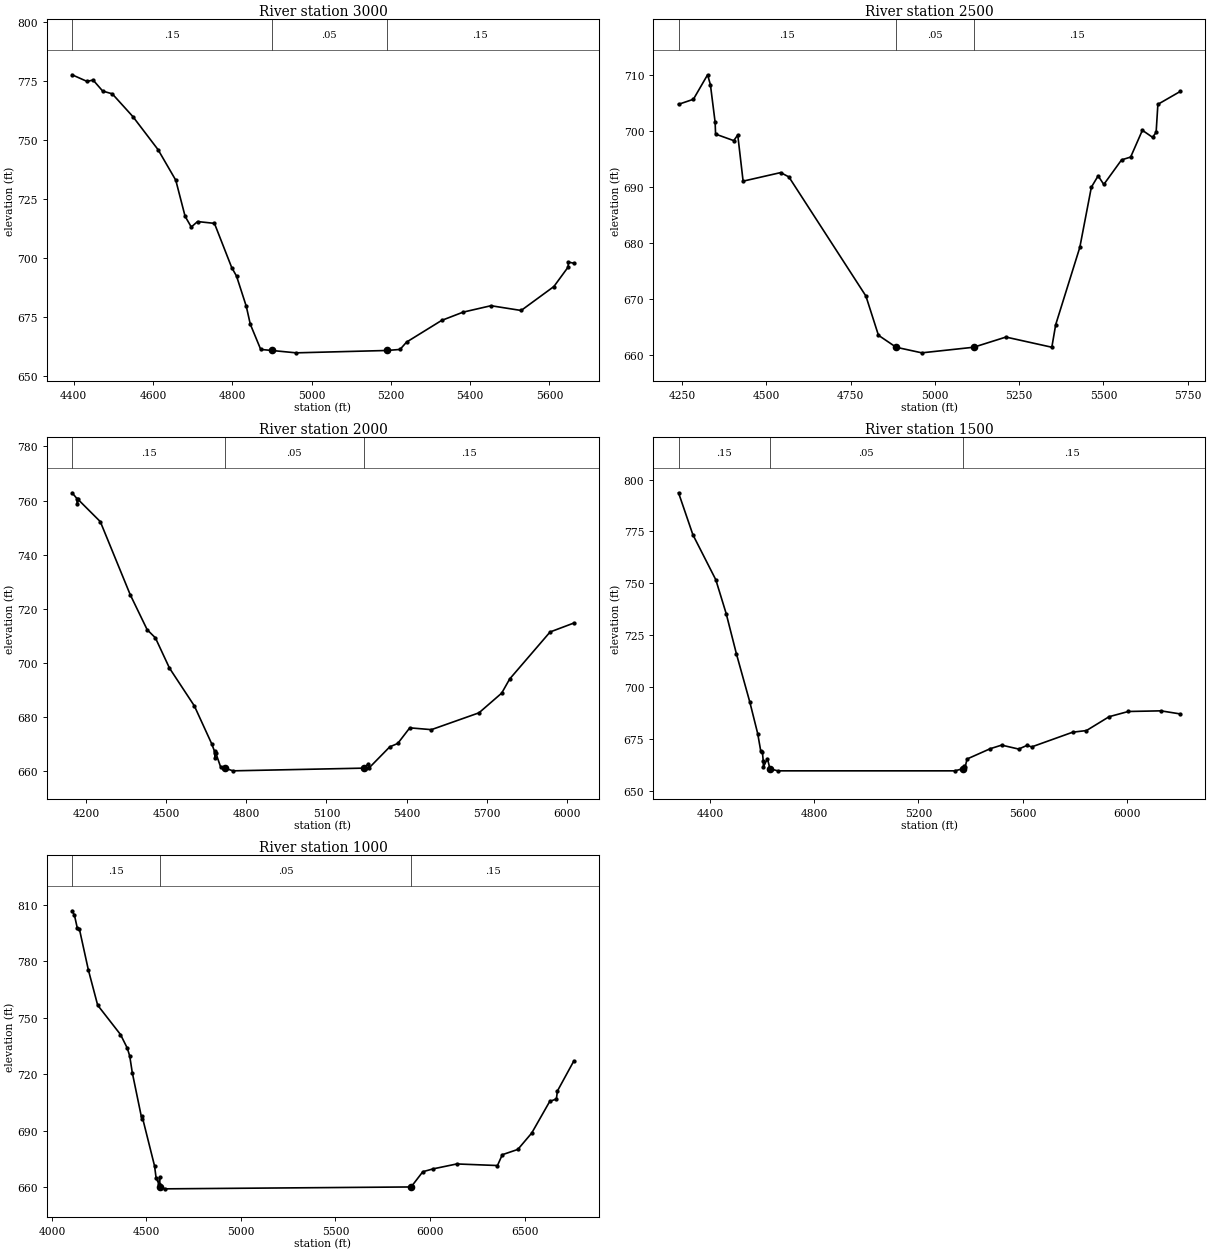
Type RM Length L Ch R = 1,3000,500,500,500
BEGIN DESCRIPTION:
Chauga River 6.0
END DESCRIPTION:
XS GIS Cut Line= 3
      1349414.42      1019045.07      1348834.01      1018878.64
      1348210.17      1018658.63
#Sta/Elev= 30
  4396.2  777.77  4434.1  774.95  4449.2  775.55  4473.4  770.87  4497.6  769.69
  4549.6  760.04  4613.1  746.02  4657.7  733.09  4681.2  717.80  4696.8  713.24
  4712.6  715.57  4755.2  714.80  4798.7  696.09  4810.9  692.46  4835.5  679.64
  4845.6  672.07  4871.9  661.37  4900.0  660.93  4961.1  659.93  5190.0  660.93
  5223.2  661.37  5239.6  664.48  5328.1  673.67  5382.3  677.18  5452.5  679.90
  5528.6  677.88  5611.2  688.04  5646.9  696.25  5647.8  698.38  5661.5  697.91
#Mann=3,-1,0
  4396.2    0.15       0  4900.0    0.05       0  5190.0    0.15       0
Bank Sta=4900,5190
XS Rating Curve= 0
Exp/Cntr=0.3,0.1

Type RM Length L Ch R = 1,2500,500,500,500
BEGIN DESCRIPTION:
Chauga River 5.0
END DESCRIPTION:
XS GIS Cut Line= 3
      1349567.26      1018389.04      1348806.58      1018394.51
      1348093.34      1018541.82
#Sta/Elev= 30
  4239.3  704.78  4283.4  705.68  4325.5  710.06  4333.9  708.28  4347.9  701.56
  4349.2  699.46  4403.2  698.29  4415.0  699.31  4430.9  691.05  4542.3  692.58
  4566.7  691.81  4795.3  670.52  4832.5  663.51  4885.0  661.37  4961.1  660.37
  5115.0  661.37  5210.8  663.19  5347.0  661.37  5358.5  665.41  5430.0  679.21
  5464.3  689.97  5484.4  692.00  5501.2  690.46  5553.9  694.85  5580.9  695.36
  5615.7  700.14  5645.8  698.89  5656.5  699.77  5661.7  704.78  5728.3  707.09
#Mann=3,-1,0
  4239.3    0.15       0  4885.0    0.05       0  5115.0    0.15       0
Bank Sta=4885,5115
XS Rating Curve= 0
Exp/Cntr=0.3,0.1

Type RM Length L Ch R = 1,2000,500,500,500
BEGIN DESCRIPTION:
Chauga River 4.0
END DESCRIPTION:
XS GIS Cut Line= 3
      1349441.46      1017571.21      1348662.06      1017915.85
      1347670.96      1018182.35
#Sta/Elev= 30
  4147.8  762.87  4166.7  760.65  4168.0  758.82  4168.6  760.57  4253.5  752.20
  4365.5  725.19  4429.0  712.23  4459.7  709.24  4512.5  698.04  4605.7  684.05
  4670.2  670.13  4681.3  667.23  4683.1  664.65  4684.1  666.76  4685.5  666.76
  4704.4  661.35  4720.0  661.06  4750.0  660.06  5240.0  661.06  5256.9  662.66
  5259.4  661.11  5337.0  668.92  5367.1  670.19  5412.0  675.96  5493.0  675.29
  5671.1  681.51  5756.1  688.79  5786.0  694.02  5937.3  711.40  6026.3  714.71
#Mann=3,-1,0
  4147.8    0.15       0  4720.0    0.05       0  5240.0    0.15       0
Bank Sta=4720,5240
XS Rating Curve= 0
Exp/Cntr=0.3,0.1

Type RM Length L Ch R = 1,1500,500,500,500
BEGIN DESCRIPTION:
Chauga River 3.0
END DESCRIPTION:
XS GIS Cut Line= 3
      1349306.61      1017347.77      1348589.39      1017422.48
      1347480.31      1017896.14
#Sta/Elev= 30
  4278.9  793.67  4334.0  773.43  4422.0  751.71  4461.8  735.41  4501.5  715.80
  4552.7  692.67  4583.0  677.43  4594.5  669.14  4601.1  668.43  4604.2  664.23
  4604.8  661.37  4620.3  665.37  4630.0  660.50  4660.0  659.50  5340.0  659.50
  5370.0  660.50  5376.0  662.03  5379.7  661.37  5387.1  665.22  5476.2  670.19
  5519.7  671.91  5585.2  670.01  5617.3  671.79  5635.1  671.05  5792.8  678.15
  5845.5  678.94  5932.5  685.62  6006.3  688.14  6131.4  688.45  6206.0  686.95
#Mann=3,-1,0
  4278.9    0.15       0  4630.0    0.05       0  5370.0    0.15       0
Bank Sta=4630,5370
XS Rating Curve= 0
Exp/Cntr=0.3,0.1

Type RM Length L Ch R = 1,1000,0,0,0
BEGIN DESCRIPTION:
Chauga River 2.0
END DESCRIPTION:
XS GIS Cut Line= 3
      1349425.01      1017175.00      1348567.85      1016923.14
      1346824.95      1017175.01
#Sta/Elev= 30
  4106.6  806.81  4119.0  804.53  4134.6  797.46  4145.7  796.95  4192.9  775.32
  4242.1  756.60  4362.7  741.04  4398.8  733.78  4411.7  729.54  4425.0  720.83
  4475.5  696.22  4477.2  697.56  4543.0  671.13  4551.4  664.60  4567.2  661.37
  4569.6  665.09  4570.0  660.00  4600.0  659.00  5900.0  660.00  5962.0  668.10
  6016.7  669.62  6141.8  672.23  6356.9  671.39  6382.5  677.14  6464.6  679.95
  6538.1  688.66  6633.2  705.45  6668.7  706.80  6673.8  710.97  6761.0  727.00
#Mann=3,-1,0
  4106.6    0.15       0  4570.0    0.05       0  5900.0    0.15       0
Bank Sta=4570,5900
XS Rating Curve= 0
Exp/Cntr=0.3,0.1

Chan Stop Cuts=-1